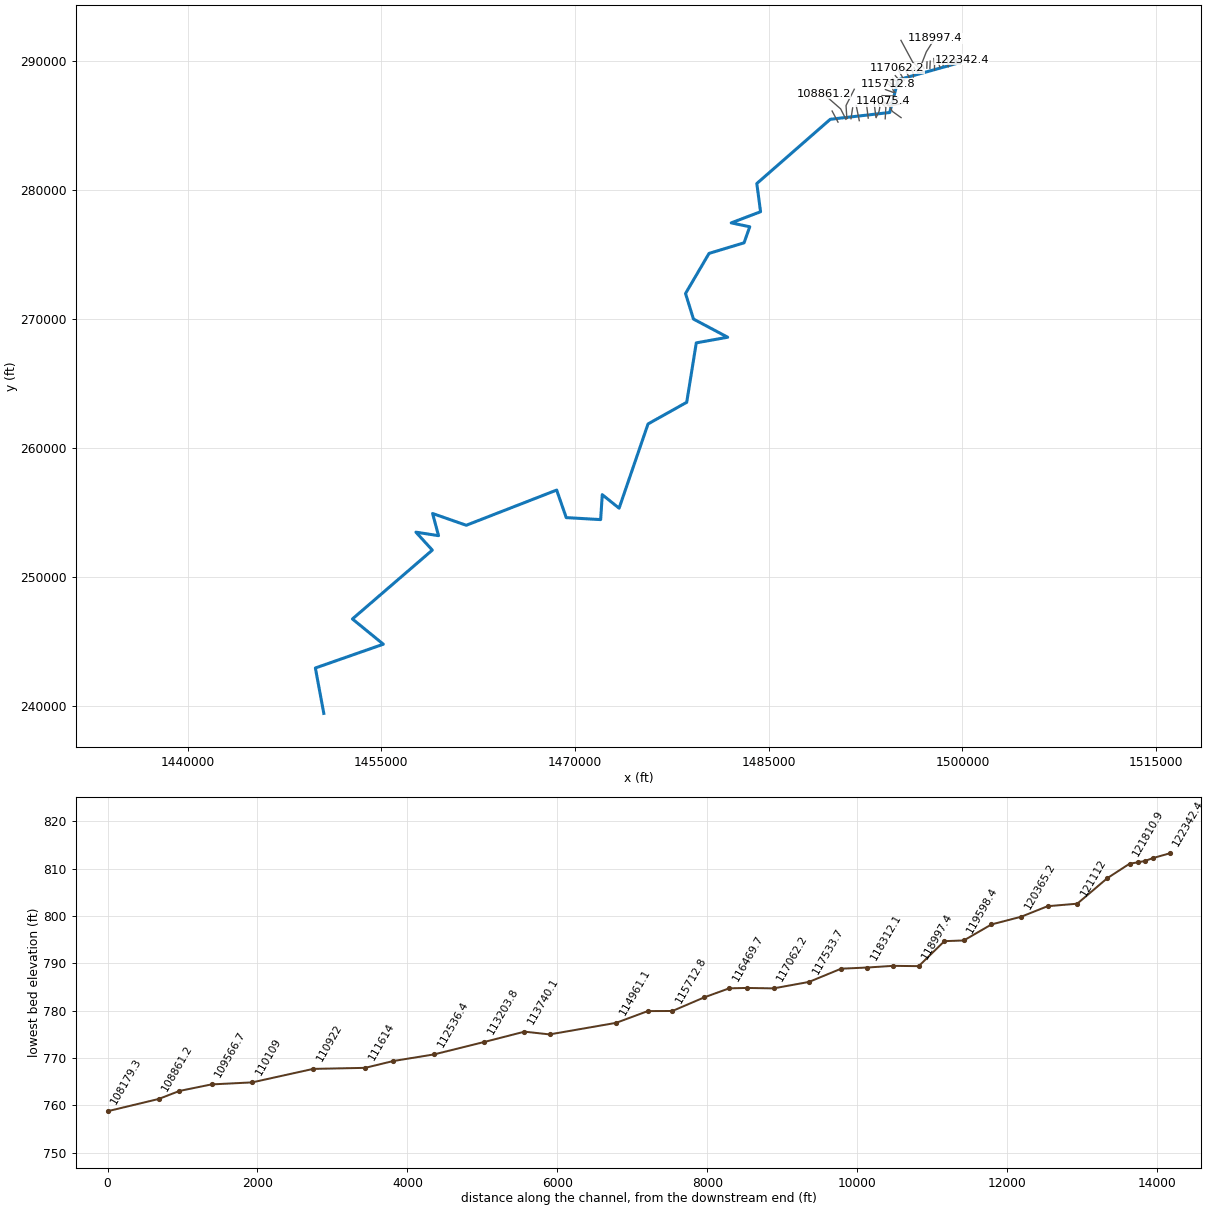
--- GSCR.prj (project) ---

Proj Title=GSCR
Current Plan=p01
Default Exp/Contr=0,0
English Units
Geom File=g01
Flow File=f01
Plan File=p01
BEGIN DESCRIPTION:
END DESCRIPTION:
DSS Export Rating Curves= 0
DSS Export Rating Curve Sorted= 0
DSS Export Volume Flow Curves= 0
DXF OffsetX= 0
DXF OffsetY= 0
DXF ScaleX= 0
DXF ScaleY= 0

--- GSCR.p01 (plan) ---

Plan Title=Floodplain
Program Version=4.00
Geom File=g01
Flow File=f01
K Sum by GR=0
Std Step Tol=0.01
Critical Tol=0.01
Num of Std Step Trials=20
Max Error Tol=0.3
Flow Tol Ratio=0.001
Split Flow NTrial=30
Split Flow Tol=0.02
Split Flow Ratio=0.02
Log Output Level=0
Friction Slope Method=1
Unsteady Friction Slope Method=2
Unsteady Bridges Friction Slope Method=1
Global Log Level=0
CheckData=False
Run HTab=0
Run UNet=0
Run PostProcess=0
UNET Theta=0
UNET Theta Warmup=0
UNET ZTol=0
UNET ZSATol=0
UNET MxIter=0
UNET MaxInSteps=0
UNET DtIC=0
UNET DtMin=0
UNET MaxCRTS=0
UNET WFStab=0
UNET SFStab=0
UNET WFX=0
UNET SFX=0
UNET DSS MLevel=0
UNET DZMax Abort=0
UNET Convert EG Bridges=0
UNET Use Existing IB Tables=0
UNET Froude Limit=0
UNET Froude Power=0
Write IC File=0
Echo Input=False
Echo Output=False
Write Detailed=0

--- GSCR.f01 (steady flow) ---

Flow Title=NFF Regression Equation
Program Version=4.10
Number of Profiles= 1
Profile Names=P100yr
River Rch & RM=GSCR,Main            ,122342.4
851.1692
River Rch & RM=GSCR,Main            ,122122.8
851.1692
River Rch & RM=GSCR,Main            ,122012.9
 952.843
River Rch & RM=GSCR,Main            ,118997.4
 1021.59
River Rch & RM=GSCR,Main            ,118655.4
1687.089
River Rch & RM=GSCR,Main            ,114075.4
1829.364
River Rch & RM=GSCR,Main            ,113203.8
2032.185
River Rch & RM=GSCR,Main            ,109138.4
2169.313
River Rch & RM=GSCR,Main            ,108861.2
2611.638
River Rch & RM=GSCR,Main            ,102187.7
2790.402
River Rch & RM=GSCR,Main            ,101860.9
3319.665
River Rch & RM=GSCR,Main            ,85893.6
3675.052
River Rch & RM=GSCR,Main            ,85686.6
 4171.24
River Rch & RM=GSCR,Main            ,85054.4
4626.642
River Rch & RM=GSCR,Main            ,82643.2
4745.893
River Rch & RM=GSCR,Main            ,68079.7
5267.929
River Rch & RM=GSCR,Main            ,56858.6
5694.695
River Rch & RM=GSCR,Main            ,52843
6278.901
River Rch & RM=GSCR,Main            ,37659.7
6802.677
River Rch & RM=GSCR,Main            ,21418.6
7557.464
River Rch & RM=GSCR,Main            ,1091.5
8332.661
River Rch & RM=GSCR,Main            ,440.7
8332.661
Boundary for River Rch & Prof#=GSCR,Main            , 1
Up Type= 0
Dn Type= 3
Dn Slope=0.0016
DSS Import GetInterval= 0
DSS Import GetPeak= 0
DSS Import FillOption= 0

--- GSCR.g01 (geometry) ---

Geom Title=USGS 10m DEM
Program Version=4.10

River Reach=GSCR            ,Main
Reach XY= 30
     1499856.341      289871.257     1495028.575      288523.329
     1494374.706      285991.207     1489774.666      285467.132
     1484081.266      280490.762     1484371.962      278305.369
     1482098.997      277442.585     1483534.241      277141.896
     1483094.471      275898.979     1480382.755      275079.164
      1478560.92      271972.353     1479176.408      269994.201
      1481825.47      268586.935     1479394.047      268151.171
     1478652.582      263548.173     1475657.067      261870.789
     1473416.956      255346.979     1472112.353      256395.096
     1471988.476      254464.085     1469322.866      254617.317
     1468582.414      256750.998      1461579.81      254025.303
     1458972.171      254936.761     1459434.845      253219.747
     1457683.109      253491.449     1458951.447      252102.072
     1452764.916      246769.416       1455158.8      244813.935
     1449895.828      242971.944     1450548.125      239457.932

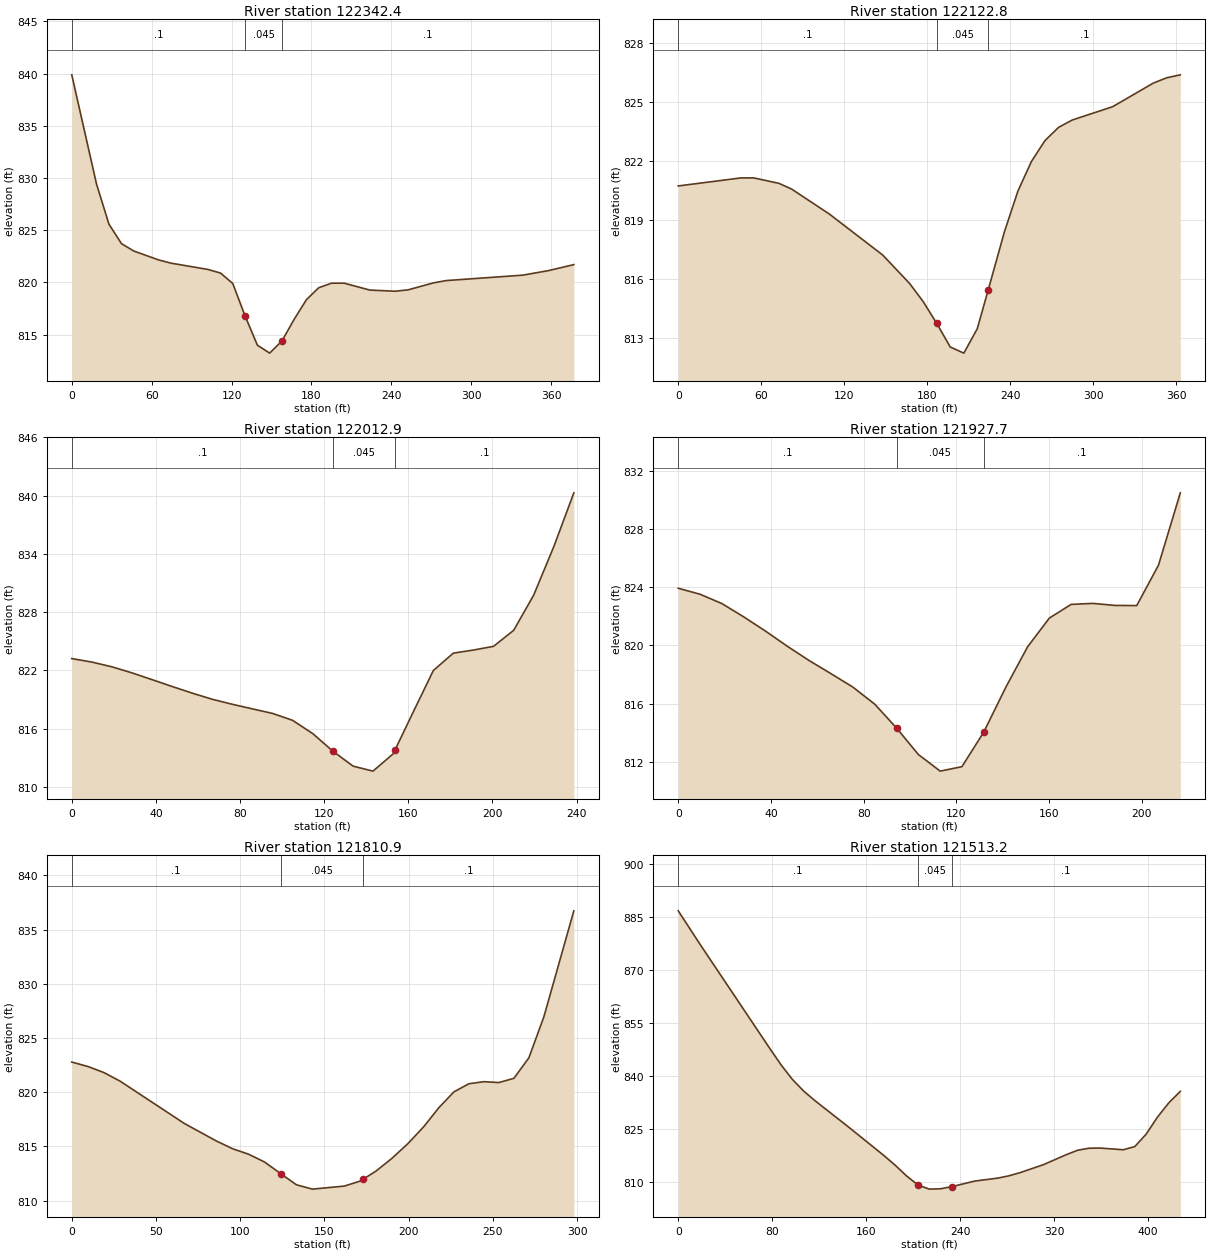
Type RM Length L Ch R = 1 ,122342.4,222.4,219.6,215
XS GIS Cut Line= 4
     1499824.691       289731.67     1499834.456      289833.667
     1499850.732      289915.047     1499946.218      290081.063
#Sta/Elev= 27
       0  839.89    18.6  829.42    27.9  825.59    37.3  823.72    46.6  823.01
    65.2  822.16    74.5  821.85   102.5  821.24   111.7   820.9   120.9   819.9
   130.1   816.8   139.4  813.99   148.6  813.23   157.8  814.39     167  816.47
   176.2  818.35   185.4  819.49     195  819.93   204.6  819.93   223.8  819.27
   242.9  819.16   252.5  819.29   271.6  819.96   281.2  820.18   338.7   820.7
   357.8  821.13     377  821.71
#Mann= 3 , 0 , 0
       0      .1       0   130.1    .045       0   157.8      .1       0
Bank Sta=130.1,157.8
XS Rating Curve= 0 ,0
Exp/Cntr=0.3,0.1

Type RM Length L Ch R = 1 ,122122.8,101,109.9,118.7
XS GIS Cut Line= 3
      1499609.63      289795.256     1499645.437      289908.103
     1499739.838      290133.797
#Sta/Elev= 24
       0  820.75    45.5  821.16    54.6  821.16    72.9  820.88      82  820.59
   109.3  819.32   147.8  817.24   167.3  815.79   177.1  814.87   186.9  813.76
   196.7  812.56   206.5  812.25   216.2  813.49   224.1815.4569   235.8  818.41
   245.6  820.49   255.4     822   265.2  823.06     275  823.73   284.8   824.1
   314.1  824.78   343.5  825.98   353.2  826.25     363   826.4
#Mann= 3 , 0 , 0
       0      .1       0   186.9    .045       0   224.1      .1       0
Bank Sta=186.9,224.1
XS Rating Curve= 0 ,0
Exp/Cntr=0.3,0.1

Type RM Length L Ch R = 1 ,122012.9,76.3,85.2,94.2
XS GIS Cut Line= 2
     1499570.784      289884.665     1499572.954      290123.381
#Sta/Elev= 29
       0  823.22     9.6  822.86    19.1  822.37    28.6  821.75    38.2  821.05
    47.8  820.34    57.3  819.66    66.8  819.03    76.4  818.51    85.9  818.04
    95.5  817.57     105  816.86   114.6  815.49   121.2  814.24   124.1  813.69
   133.7  812.15   136.2  812.01   143.2  811.63   152.8  813.41   153.7813.8164
   162.3   817.7   171.9  821.99   181.4  823.78     191   824.1   200.5  824.48
   210.1  826.13   219.6  829.75   229.2  834.76   238.7  840.29
#Mann= 3 , 0 , 0
       0      .1       0   124.1    .045       0   153.7      .1       0
Bank Sta=124.1,153.7
XS Rating Curve= 0 ,0
Exp/Cntr=0.3,0.1

Type RM Length L Ch R = 1 ,121927.7,120.6,116.8,112.9
XS GIS Cut Line= 2
     1499533.892      289884.665     1499452.512      290085.403
#Sta/Elev= 26
       0  823.93     9.4  823.52    18.8  822.88    28.2  821.97    37.7  820.98
    47.1  819.94    56.5  818.96    65.9  818.06    75.3  817.14    84.8  815.96
    94.2  814.32   103.6   812.5   106.6  812.14     113  811.36   121.6  811.64
   122.4  811.67   131.8  814.04   141.3  817.12   150.7   819.9   160.1  821.88
   169.5  822.82   178.9  822.89   188.4  822.75   197.8  822.74   207.2  825.52
   216.6  830.49
#Mann= 3 , 0 , 0
       0      .1       0    94.2    .045       0   131.8      .1       0
Bank Sta=94.2,131.8
XS Rating Curve= 0 ,0
Exp/Cntr=0.3,0.1

Type RM Length L Ch R = 1 ,121810.9,259.2,297.7,279.6
XS GIS Cut Line= 4
     1499457.937      289815.221     1499397.173      289889.006
     1499372.217      289999.683     1499376.557      290088.658
#Sta/Elev= 28
       0  822.78     9.6  822.37    19.1  821.81    28.7  821.02    66.9  817.11
      86  815.49    95.6  814.78     105  814.28   114.5  813.56     124  812.49
   133.4  811.46   142.9  811.06   161.8  811.34   171.2   811.8     173811.9762
   180.7  812.73   190.1   813.9   199.6  815.26     209  816.82     218  818.58
   226.9  820.03   235.8  820.78   244.7  820.97   253.6  820.89   262.5  821.28
   271.4  823.17   280.3  826.95   298.1  836.73
#Mann= 3 , 0 , 0
       0      .1       0     124    .045       0     173      .1       0
Bank Sta=124,173
XS Rating Curve= 0 ,0
Exp/Cntr=0.3,0.1

Type RM Length L Ch R = 1 ,121513.2,399.3,401.2,399.1
XS GIS Cut Line= 2
     1499210.107      289661.141     1499166.053      290086.488
#Sta/Elev= 30
       0  886.77    19.4  876.88    77.8  847.91    87.5  843.21    97.2  839.06
   106.9  835.73   116.6     833   145.8  825.38   174.9  817.58   184.7  814.79
   194.4  811.76   204.1  809.19   213.8     808   223.5   808.1   233.2  808.72
   252.7  810.29   272.1  811.11   281.8  811.78   291.6  812.71     311  814.92
   330.4  817.74   340.2  819.01   349.9  819.58   359.6  819.62     379  819.14
   388.8  820.04   398.5  823.55   408.2  828.41   417.9  832.46   427.6  835.67
#Mann= 3 , 0 , 0
       0      .1       0   204.1    .045       0   233.2      .1       0
Bank Sta=204.1,233.2
XS Rating Curve= 0 ,0
Exp/Cntr=0.3,0.1

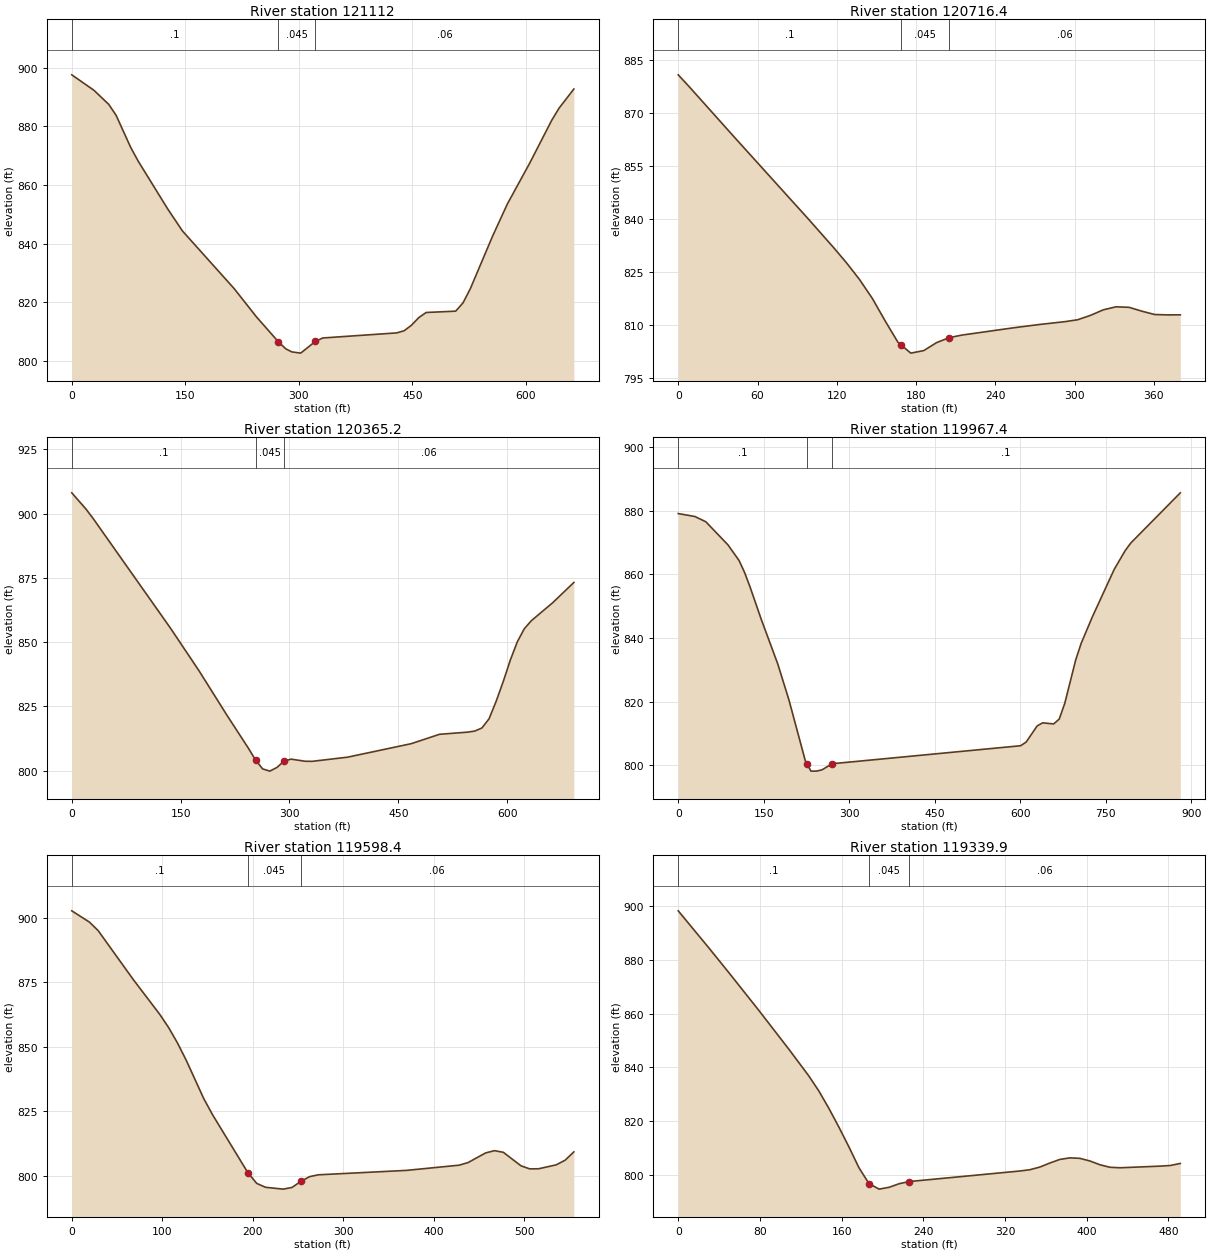
Type RM Length L Ch R = 1 ,121112  ,396.2,395.6,394
XS GIS Cut Line= 2
     1498902.816      289520.516     1498853.336      290181.974
#Sta/Elev= 30
       0  897.57    29.3   892.3    48.8   887.5    58.5   883.8      78  872.73
    87.8   868.1   126.8  851.78   146.3  844.27   214.6   824.6   243.9     815
   273.1  806.43   282.9  804.04   290.6  803.03   302.4   802.6   321.9  806.61
   331.6  807.77   429.2   809.5     439  810.22   448.7   812.1   458.5  814.73
   468.2  816.47   507.2  816.92     517  819.79   526.7  824.68     556  842.55
   575.5  853.51   604.8  867.34     634  882.02   643.8   886.2   663.3  892.72
#Mann= 3 , 0 , 0
       0      .1       0   273.1    .045       0   321.9     .06       0
Bank Sta=273.1,321.9
XS Rating Curve= 0 ,0
Exp/Cntr=0.3,0.1

Type RM Length L Ch R = 1 ,120716.4,342.2,351.2,358.6
XS GIS Cut Line= 3
     1498510.454       289639.44     1498500.038      289698.033
     1498489.621      290018.346
#Sta/Elev= 28
       0  880.88     8.5  877.44    42.5  863.22    98.4  840.09   117.8  831.87
   127.5  827.58   137.2  822.92   146.9  817.57   156.6   811.2   166.3  805.14
  168.47804.4532     176  802.07   185.8  802.78   195.5  805.04   205.2  806.46
   214.9  807.19   253.7  809.24   273.2  810.17   292.6  810.98   302.3  811.52
     312  812.76   321.7  814.33   331.4  815.19   341.2  815.04   350.9  813.95
   360.6     813   370.3   812.9     380  812.91
#Mann= 3 , 0 , 0
       0      .1       0  168.47    .045       0   205.2     .06       0
Bank Sta=168.47,205.2
XS Rating Curve= 0 ,0
Exp/Cntr=0.3,0.1

Type RM Length L Ch R = 1 ,120365.2,405.8,397.8,389.1
XS GIS Cut Line= 2
     1498275.211      289468.433     1498040.836      290119.474
#Sta/Elev= 30
       0  908.14    19.5  901.85    29.2  898.25   136.4  855.33   175.4  838.88
   214.4  821.36   243.6  808.69   253.4  804.08   263.1  800.71   272.9  799.85
   282.6  801.26   292.4  803.69   302.1  804.52   321.6  803.69   331.4  803.66
   380.1  805.28   467.8  810.53   506.8  814.18   545.8  815.03   555.5  815.45
   565.2  816.64     575  820.19   584.7  826.92   594.5  834.62   604.2  842.93
     614  850.17   623.7  855.28   633.5  858.43   662.7  865.36   691.9  873.26
#Mann= 3 , 0 , 0
       0      .1       0   253.4    .045       0   292.4     .06       0
Bank Sta=253.4,292.4
XS Rating Curve= 0 ,0
Exp/Cntr=0.3,0.1

Type RM Length L Ch R = 1 ,119967.4,369.5,369,367.4
XS GIS Cut Line= 3
     1497837.711      289293.953      1497845.09      289730.585
     1497790.836      290171.558
#Sta/Elev= 30
       0  879.13    29.1  878.22    48.5  876.55    87.3  869.29   106.8  864.37
   116.4  860.64   126.2  855.99   145.6  845.94   174.7  831.86   194.1  820.68
   223.2  801.33  226.12800.3938   232.9  798.22   242.6  798.21   252.3  798.62
     270 800.531   600.9  806.19   610.6  807.36   629.9  812.44   639.5  813.38
   658.8  813.04   668.5  814.55   678.2  819.47   697.5  833.18   707.1  838.39
   726.4  846.57   765.1  861.63   784.4  867.53   794.1  869.88     881  885.65
#Mann= 3 , 0 , 0
       0      .1       0  226.12    .045       0     270      .1       0
Bank Sta=226.12,270
XS Rating Curve= 0 ,0
Exp/Cntr=0.3,0.1

Type RM Length L Ch R = 1 ,119598.4,258.2,258.5,257.6
XS GIS Cut Line= 2
     1497483.545      289411.141     1497510.454       289964.96
#Sta/Elev= 30
       0   902.7    19.5  898.34    29.2  895.01    68.1  875.98    97.3  862.52
     107  857.43   116.7  851.52   126.5  844.71   145.9  829.82   155.6   823.6
   194.6  801.15   204.3  797.05     214  795.54   233.5  794.83   243.2  795.48
   252.9   797.8   262.6  799.67   272.4  800.38   369.6  802.09     428  804.12
   437.7  805.13   457.2  808.88   466.9  809.74   476.6  809.11   496.1  803.87
   505.8  802.68   515.6  802.72     535  804.24   544.8  806.02   554.5  809.26
#Mann= 3 , 0 , 0
       0      .1       0   194.6    .045       0   252.9     .06       0
Bank Sta=194.6,252.9
XS Rating Curve= 0 ,0
Exp/Cntr=0.3,0.1

Type RM Length L Ch R = 1 ,119339.9,329,342.4,354.9
XS GIS Cut Line= 2
     1497244.829      289424.162     1497263.059      289915.481
#Sta/Elev= 30
       0  898.29    29.5  884.72    49.2  875.46    78.7  861.34   108.2  846.84
   127.8  836.87   137.7  831.23   147.5  824.78   157.3   817.8   167.2  810.38
     177  802.64   186.8  796.75   196.7  794.68   206.5  795.36   216.3  796.69
   226.2   797.5   334.3  801.42   344.2  801.89     354  802.87   363.8  804.38
   373.7  805.73   383.5  806.32   393.3  806.14   403.2  805.16     413  803.75
   422.8  802.82   432.7  802.63     472  803.24   481.8  803.47   491.7  804.24
#Mann= 3 , 0 , 0
       0      .1       0   186.8    .045       0   226.2     .06       0
Bank Sta=186.8,226.2
XS Rating Curve= 0 ,0
Exp/Cntr=0.3,0.1

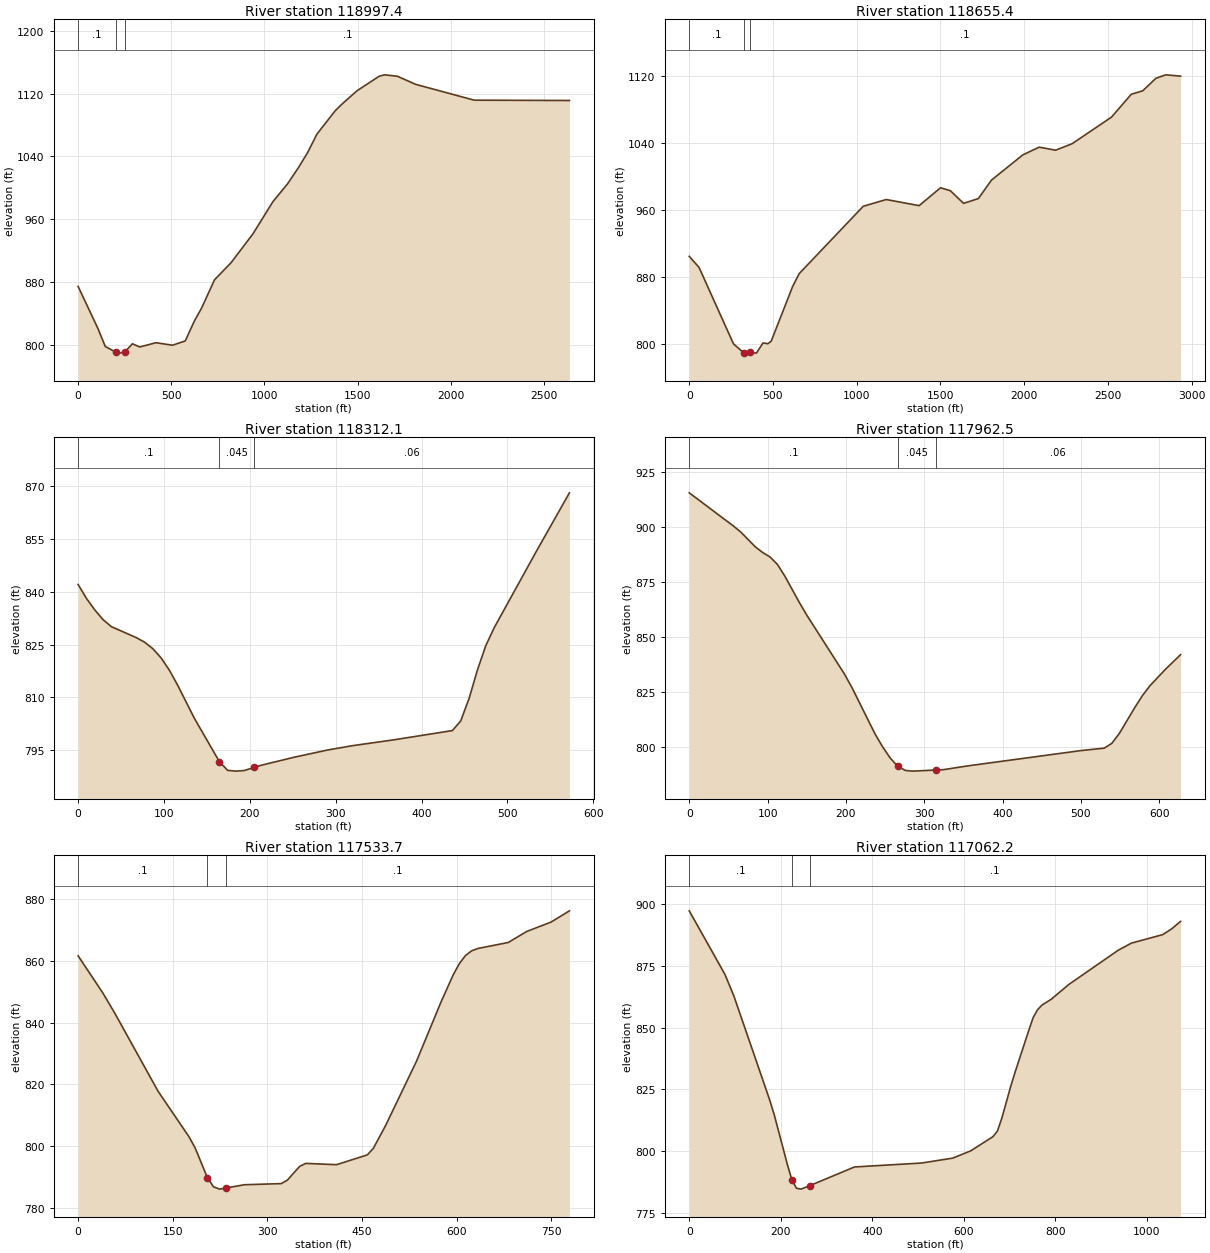
Type RM Length L Ch R = 1 ,118997.4,335.6,342,347.6
XS GIS Cut Line= 4
     1497029.986      289405.065     1496841.955      289745.311
      1497207.54      290687.185     1497868.999       291734.06
#Sta/Elev= 30
       0  874.39   106.9  820.59   145.8  797.91   204.1  790.43   223.5   789.4
   252.7  791.41   291.6  801.33   330.4   797.2   418.2  802.67   506.5  799.48
   575.1  804.93   624.2  830.32   663.4  847.03   732.1  882.78   820.4  904.42
   938.1  941.21    1046  982.48  1124.4 1005.12  1183.3 1025.93  1232.3    1045
  1281.4 1068.24  1379.5 1098.05  1418.7 1107.21  1497.4 1123.71  1615.3 1142.08
  1644.8 1143.98  1713.6 1142.19  1811.9 1131.86  2126.4 1111.68  2637.4 1111.28
#Mann= 3 , 0 , 0
       0      .1       0   204.1    .045       0   252.7      .1       0
Bank Sta=204.1,252.7
XS Rating Curve= 0 ,0
Exp/Cntr=0.3,0.1

Type RM Length L Ch R = 1 ,118655.4,342,343.4,343.7
XS GIS Cut Line= 4
     1496888.927      289189.787      1496570.35      289507.929
     1496161.286      289874.778     1495243.999       291577.81
#Sta/Elev= 30
       0   905.1    58.7  891.76   264.3   800.5   324.4  789.94   332.8  789.46
   362.1  790.24   401.3  789.49   440.4  801.61   469.8  800.72   489.5  803.77
     617  868.82   656.3  884.34    1039  964.84  1176.4   972.9  1372.8  965.61
  1500.5  986.94  1559.4  983.45  1637.9  968.35  1726.3  974.02  1804.9  996.12
  1991.4 1026.16  2089.6 1035.45  2187.8 1031.82    2286 1039.53  2521.6 1071.33
  2639.5 1098.62  2708.2 1102.81  2786.8 1117.72  2845.7 1121.84    2934 1120.26
#Mann= 3 , 0 , 0
       0      .1       0   324.4    .045       0   362.1      .1       0
Bank Sta=324.4,362.1
XS Rating Curve= 0 ,0
Exp/Cntr=0.3,0.1

Type RM Length L Ch R = 1 ,118312.1,361.5,349.6,335.9
XS GIS Cut Line= 3
     1496625.038       289058.71     1496343.788       289295.69
      1496251.34      289477.981
#Sta/Elev= 30
       0  842.04     9.7  838.11    19.4  834.84      29  832.09    38.7  830.08
    67.8  826.97    77.4  825.68    87.1  823.82    96.8  821.17   106.5  817.66
   116.1   813.4   135.5  804.05   164.5  791.81   174.2  789.32   183.9  789.11
   193.6  789.28   205.1 790.163   212.9  790.75   251.6  793.05   290.4  795.09
   319.4  796.32   367.8  797.99   435.9  800.61   445.6  803.35   455.4  809.77
   465.1  817.83   474.8   824.7   484.6  829.79   533.2  851.24   572.2  868.03
#Mann= 3 , 0 , 0
       0      .1       0   164.5    .045       0   205.1     .06       0
Bank Sta=164.5,205.1
XS Rating Curve= 0 ,0
Exp/Cntr=0.3,0.1

Type RM Length L Ch R = 1 ,117962.5,424.1,428.8,431.5
XS GIS Cut Line= 3
     1496205.767      288737.964     1496216.618      288915.915
     1496079.899      289343.433
#Sta/Elev= 30
       0  915.57    56.3  900.48    65.7  897.75    84.4  890.95    93.8  888.37
   103.2  886.34   112.6  882.96     122  877.66   140.8  865.47   150.1  859.84
   197.8  833.23   207.6  826.96   236.8  806.02   246.6  800.04   256.3  794.92
   266.1  791.05   275.9  789.16   285.6  788.86   314.9  789.37   324.6  789.53
   353.9  791.17   500.3  798.23   529.6  799.32   539.3  801.49   549.1  806.11
   568.6  817.77   578.3   823.2   588.1  827.78   607.6  835.15   627.1  841.89
#Mann= 3 , 0 , 0
       0      .1       0   266.1    .045       0   314.9     .06       0
Bank Sta=266.1,314.9
XS Rating Curve= 0 ,0
Exp/Cntr=0.3,0.1

Type RM Length L Ch R = 1 ,117533.7,469.7,471.5,472.7
XS GIS Cut Line= 3
     1495878.076      288709.752      1495632.85      289208.884
       1495539.1      289411.141
#Sta/Elev= 30
       0  861.73      39  849.75    58.5  843.01   126.8   817.8   175.6  803.12
   185.4   799.5   204.9  789.83   214.6  786.83   224.4  786.06   234.2  786.41
   263.4  787.48     322  787.85   331.7  788.96   351.2  793.42     361  794.41
   409.8  793.99   458.6  797.17   468.3  799.35   487.8   806.8   536.6  827.58
   575.5   846.8   594.9  855.64   604.6  859.24   614.3  861.85     624  863.35
   633.7   864.1   682.1  866.06   711.2  869.62     750  872.68     779  876.32
#Mann= 3 , 0 , 0
       0      .1       0   204.9    .045       0   234.2      .1       0
Bank Sta=204.9,234.2
XS Rating Curve= 0 ,0
Exp/Cntr=0.3,0.1

Type RM Length L Ch R = 1 ,117062.2,349.8,358,367.9
XS GIS Cut Line= 2
     1495495.698      288491.002     1494957.503      289419.821
#Sta/Elev= 30
       0  897.24    78.1   871.5    97.6  862.76   175.7   820.8   185.4  814.98
   214.7  794.48   224.4  788.32   234.2  785.08     244   784.7   263.5  786.12
   361.1  793.66   507.5  795.25   575.8  797.24   614.8  800.16   663.6  805.92
   673.4  808.21   683.1  813.45   702.6  826.41   712.4  832.26   741.7  848.81
   751.4  854.07   761.2  857.29     771  859.17   790.5  861.43   829.5  867.48
   936.9  881.26   966.1  884.18  1034.4  887.61    1054  889.94  1073.5  892.97
#Mann= 3 , 0 , 0
       0      .1       0   224.4    .045       0   263.5      .1       0
Bank Sta=224.4,263.5
XS Rating Curve= 0 ,0
Exp/Cntr=0.3,0.1

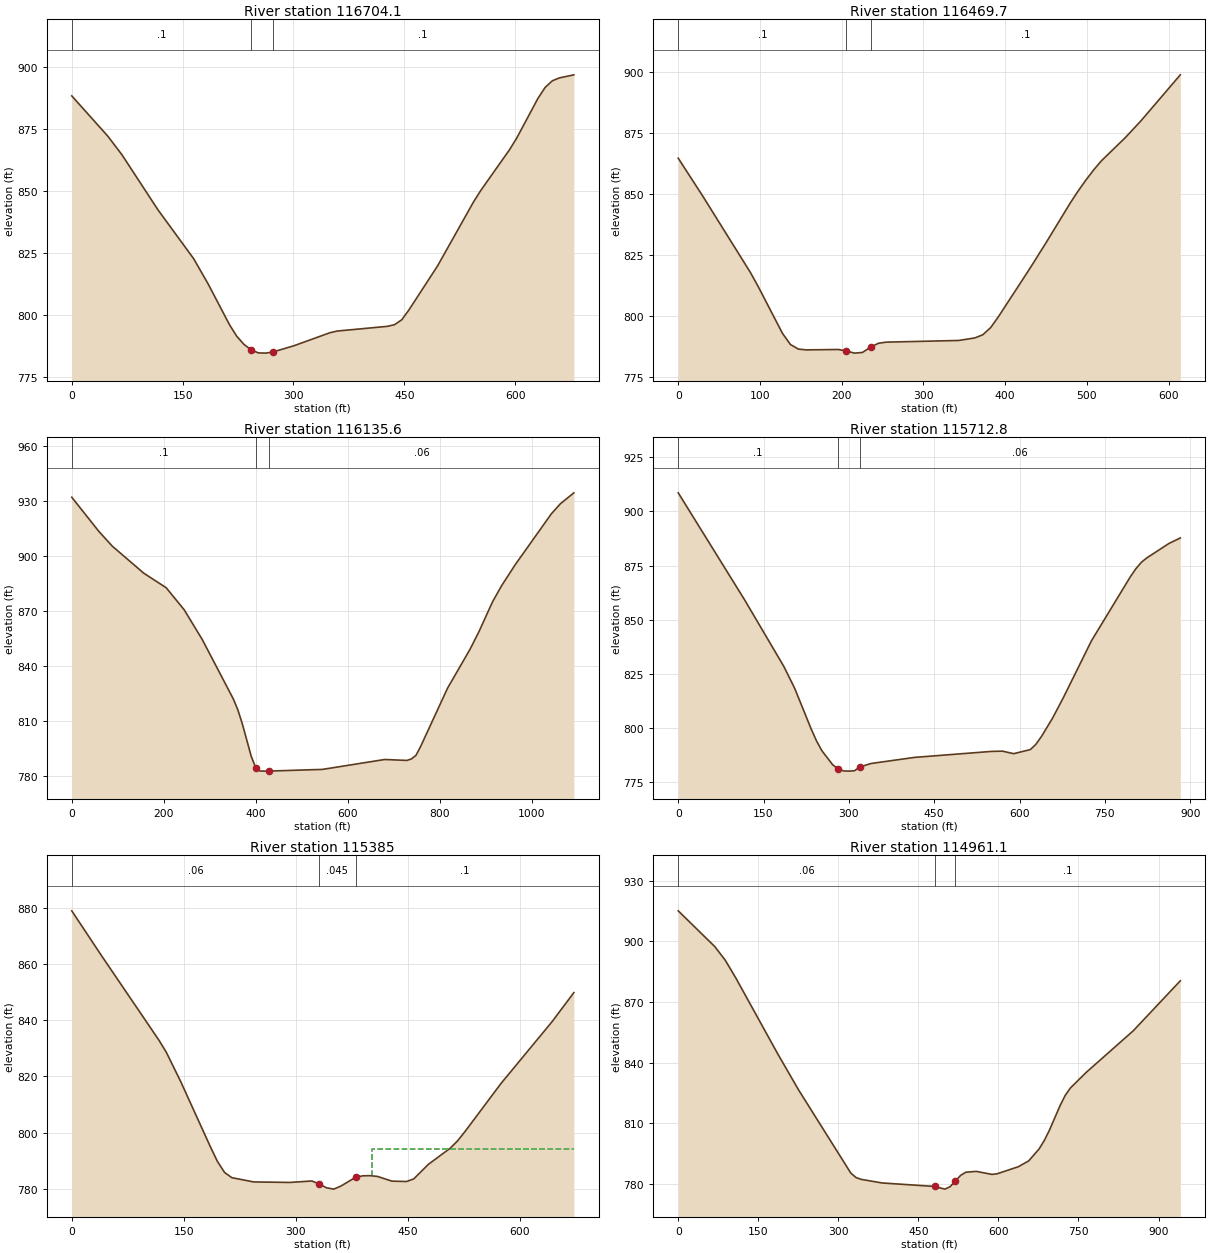
Type RM Length L Ch R = 1 ,116704.1,232.2,234.5,233.3
XS GIS Cut Line= 2
     1495256.982      288334.752     1494805.593      288842.565
#Sta/Elev= 30
       0   888.4    48.5  872.28    67.9  864.69   116.5  842.57     165   822.8
   184.4  812.74   213.5  796.21   223.2  791.61     233  788.32   242.6  786.13
   252.4  784.89   262.1  784.79   271.8  785.21   300.9  787.79   349.4  793.01
   359.1  793.68   427.1  795.58   436.8  796.26   446.5  798.21   456.2  802.16
     495  819.92   543.5  845.61   553.2  850.19   592.1   866.6   601.8  871.24
   630.9  887.44   640.6  891.82   650.3  894.48     660  895.65   679.4  896.88
#Mann= 3 , 0 , 0
       0      .1       0   242.6    .045       0   271.8      .1       0
Bank Sta=242.6,271.8
XS Rating Curve= 0 ,0
Exp/Cntr=0.3,0.1

Type RM Length L Ch R = 1 ,116469.7,326.5,334.1,341.5
XS GIS Cut Line= 3
     1495103.336      288251.853     1494762.191      288499.683
     1494605.941       288612.53
#Sta/Elev= 30
       0  864.64    29.4  849.42    88.3   817.8    98.1  811.86   127.5  792.86
   137.3  788.24   147.1  786.36   156.9  786.04   196.1   786.2   205.9  785.56
   215.7  784.71   225.5  784.99   235.4   787.2   245.2  788.78     255  789.22
   343.2   789.9   362.8  790.93   372.6  792.22   382.4   795.2   392.2  799.83
   431.3  819.94   450.6  830.25   479.5  846.15   489.1  851.06   498.8  855.65
   508.4  859.85     518  863.63   546.9  873.01   566.2  879.95   614.4  898.83
#Mann= 3 , 0 , 0
       0      .1       0   205.9    .045       0   235.4      .1       0
Bank Sta=205.9,235.4
XS Rating Curve= 0 ,0
Exp/Cntr=0.3,0.1

Type RM Length L Ch R = 1 ,116135.6,443.6,422.8,401.9
XS GIS Cut Line= 4
     1495256.982       287983.19     1494961.843      288052.634
     1494553.857      288174.162      1494280.42      288412.877
#Sta/Elev= 30
       0  932.28    58.7   913.7      88  905.61   156.5  890.84   205.4  882.87
   244.5  870.85   283.6   854.7   351.6  822.06   361.2  816.24   370.9  808.63
   390.3  790.86     400  784.72   409.6  782.85   419.3  782.79     429  782.82
   545.1  783.73   680.5  789.14   728.9  788.63   738.7  789.45   748.5  791.39
   758.3  796.03   817.2  828.04   866.2  849.32   885.9  859.11   915.3  875.31
   934.9  884.02   964.4  895.46  1042.8  923.16  1062.4  928.65  1091.9  934.68
#Mann= 3 , 0 , 0
       0      .1       0     400    .045       0     429     .06       0
Bank Sta=400,429
XS Rating Curve= 0 ,0
Exp/Cntr=0.3,0.1

Type RM Length L Ch R = 1 ,115712.8,307.5,327.8,346.7
XS GIS Cut Line= 4
     1494777.816      287550.898     1494662.364       287670.69
     1494545.177      287974.509     1494232.677      288208.884
#Sta/Elev= 30
       0  908.63   117.4  858.82   185.5  828.41   204.7  818.22   233.4   799.6
     243  793.95   252.6  789.34   271.7   782.8   281.3  780.93   290.9  780.01
   300.5  779.92     310  780.12   319.6  781.88   338.8  783.44   415.4  786.27
   550.6  789.04   570.1  789.16   589.7  787.99     619  789.89   628.7  792.32
   638.5  795.94     658  804.41   677.6  814.21   726.4  840.19   794.7  869.77
   804.5  873.54   814.3  876.54     824  878.59   863.1  885.28   882.6  887.75
#Mann= 3 , 0 , 0
       0      .1       0   281.3    .045       0   319.6     .06       0
Bank Sta=281.3,319.6
XS Rating Curve= 0 ,0
Exp/Cntr=0.3,0.1

Type RM Length L Ch R = 1 ,115385  ,415.8,423.9,429.7
XS GIS Cut Line= 2
     1494675.385      287535.707     1494043.875      287767.912
#Sta/Elev= 30
       0  878.92      39  863.31     117  832.82   126.8  828.54   146.3  817.99
   185.3  795.23     195  789.84   204.8  785.82   214.5  783.98   243.8  782.46
   292.5  782.28   321.8   782.8   331.6  781.75   341.3  780.38     351   779.9
   360.8  781.01   380.3   784.1   390.1  784.64   399.8  784.69   409.6  784.42
   429.1  782.74   448.6  782.61   458.3  783.54   477.8   788.7   507.1  794.45
   516.8  797.03   526.6  800.26   575.3  817.53   643.6  839.47   672.8  849.82
#Mann= 3 , 0 , 0
       0     .06       0   331.6    .045       0   380.3      .1       0
#XS Ineff= 2 , 0
                          402.46             794
Permanent Ineff=
       F       F
Bank Sta=331.6,380.3
XS Rating Curve= 0 ,0
Exp/Cntr=0.3,0.1

Type RM Length L Ch R = 1 ,114961.1,872.6,885.7,897.9
XS GIS Cut Line= 2
     1494727.468      287262.703     1493787.328      287298.728
#Sta/Elev= 30
       0  915.13    68.6  897.41    88.2  890.65   107.8  881.95   186.2  844.47
   225.4  826.56   323.4  785.35   333.2  783.14     343  782.23   382.2  780.46
   480.2  778.74   499.8  777.41   509.6  778.65   519.4  781.45   529.2  784.22
     539  785.79   558.6  786.18     588  784.69   597.8  785.02     637  788.47
   656.6  791.36   676.2   797.3     686  801.51   695.8  806.71   715.4  818.67
   725.2  823.82     735   827.5   764.4  835.16   852.6  855.76   940.8  880.51
#Mann= 3 , 0 , 0
       0     .06       0   480.2    .045       0   519.4      .1       0
Bank Sta=480.2,519.4
XS Rating Curve= 0 ,0
Exp/Cntr=0.3,0.1

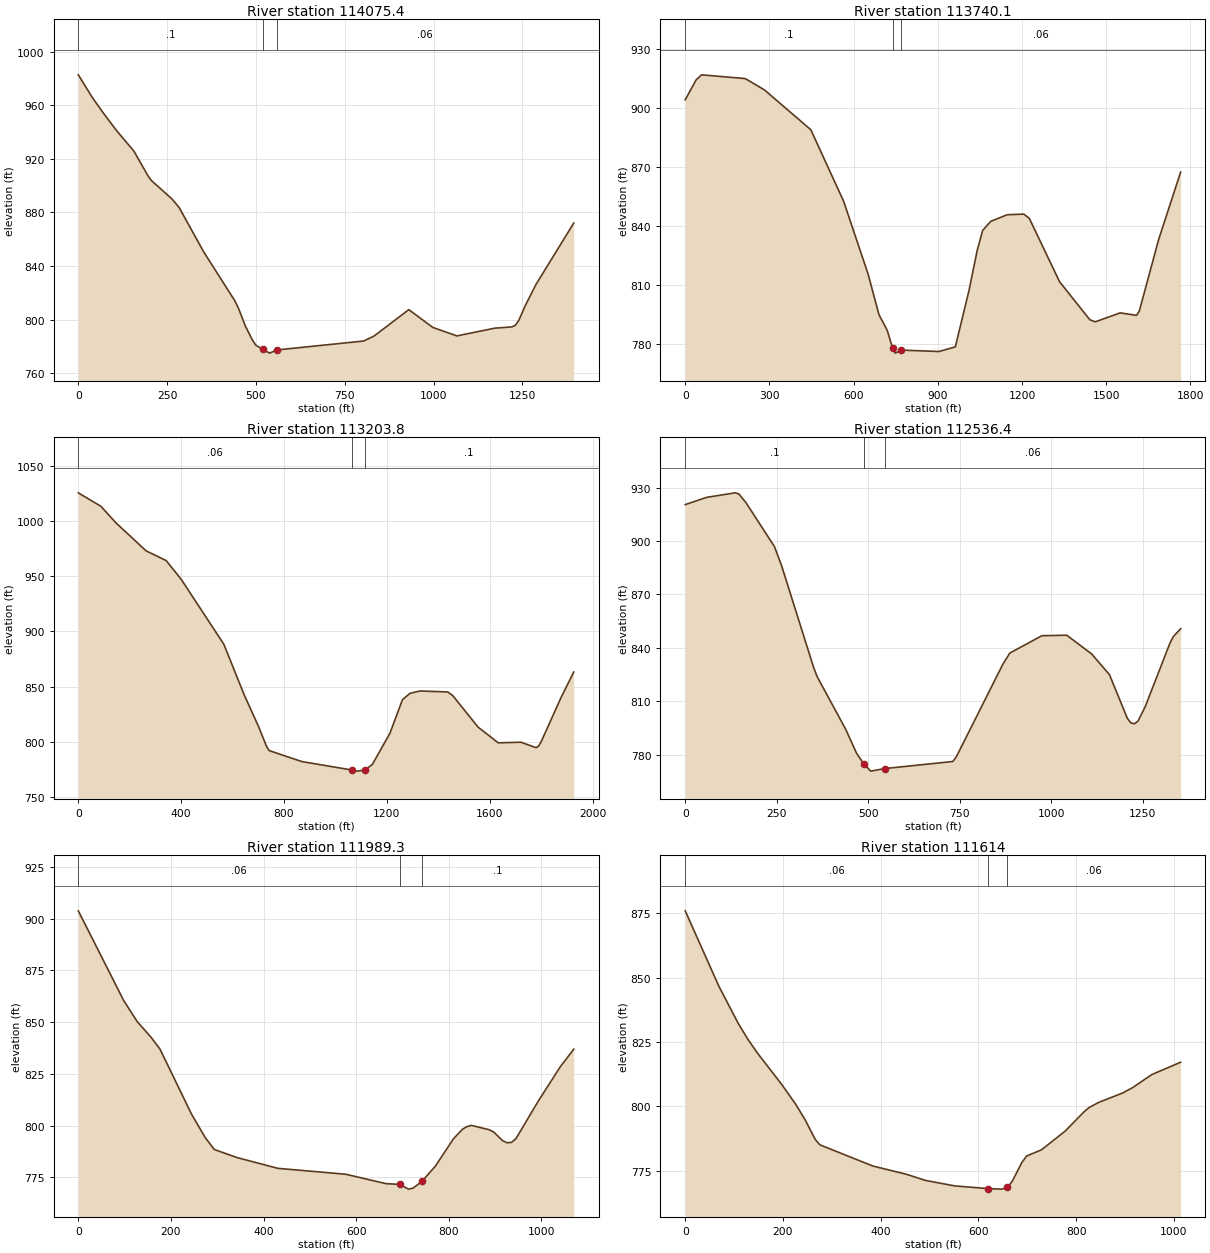
Type RM Length L Ch R = 1 ,114075.4,342.9,335.4,327.8
XS GIS Cut Line= 3
     1495019.099      287113.832     1494224.828      286629.457
     1493821.182      286858.624
#Sta/Elev= 30
       0  982.65    39.2  965.83    68.6  954.79   107.7  941.02   156.7  925.63
   195.9  907.37   205.6   903.8   264.4  889.82     284  883.57   352.5  850.71
   440.7  813.98   450.5  808.67     470  795.35   489.6  784.96   499.4  780.99
     519  777.76   538.6  774.97   558.2  777.32     803     784   832.4   787.7
   930.3  807.44     998  794.12  1065.7  787.82  1172.1  793.59  1220.4  794.54
  1230.1  795.77  1239.8  799.39  1259.1  810.99  1288.1  826.15  1394.5  872.03
#Mann= 3 , 0 , 0
       0      .1       0     519    .045       0   558.2     .06       0
Bank Sta=519,558.2
XS Rating Curve= 0 ,0
Exp/Cntr=0.3,0.1

Type RM Length L Ch R = 1 ,113740.1,571.4,536.3,501.5
XS GIS Cut Line= 4
     1495467.486      286731.887     1494946.652      286609.492
     1494394.569      286497.512     1493821.652      286838.658
#Sta/Elev= 30
       0   904.2    38.9  914.32    58.4  916.88     214  914.97   282.1  909.24
   447.5  888.99   564.2  852.74   651.6  815.68   690.4  795.04   719.6  787.16
     739  778.03   748.7  775.55   768.1  777.09   904.1  776.37   962.4  778.73
  1010.9  807.26  1040.1   827.6  1059.5  837.79  1088.6  842.48  1147.4  845.84
  1206.2  846.14  1225.8  844.03  1333.7  811.82  1441.6  792.49  1461.2  791.45
  1549.4  795.99  1608.2  794.74    1618  796.96  1686.7  833.22  1765.1   867.5
#Mann= 3 , 0 , 0
       0      .1       0     739    .045       0   768.1     .06       0
Bank Sta=739,768.1
XS Rating Curve= 0 ,0
Exp/Cntr=0.3,0.1

Type RM Length L Ch R = 1 ,113203.8,674.6,667.3,659.1
XS GIS Cut Line= 4
     1495253.944      285593.867     1494571.182      286082.582
     1494373.266      286465.394     1493815.974      286811.749
#Sta/Elev= 30
       0 1025.48    87.9 1013.28   146.4  998.29   263.6  972.92   341.7  964.12
   400.3  947.09   566.3  888.18   644.4  842.89     703  812.72   732.2  795.63
     742  792.01     869  782.05  1064.9  774.35  1084.5  773.37  1113.9  774.23
  1143.3  779.34  1211.8  807.58  1260.8  838.14  1290.2  843.88  1329.4  845.98
  1437.1  845.08  1456.7  841.71  1554.6  813.28    1633     799  1721.1  799.56
  1779.8  794.66  1789.6  795.87  1799.4  799.62  1877.8  840.21  1926.8  863.12
#Mann= 3 , 0 , 0
       0     .06       0  1064.9    .045       0  1113.9      .1       0
Bank Sta=1064.9,1113.9
XS Rating Curve= 0 ,0
Exp/Cntr=0.3,0.1

Type RM Length L Ch R = 1 ,112536.4,549.6,547.1,544
XS GIS Cut Line= 3
     1494024.307      285504.457     1494073.786       286400.29
     1493746.132      286718.867
#Sta/Elev= 30
       0   920.5    58.5  924.57   136.5  927.12   146.3  926.55   165.8  921.69
   243.8  896.95   263.3   886.3   351.1  828.94   360.8  823.78   438.8   794.2
   468.1   780.9   487.6  774.93   507.1  770.75   546.1  772.21   731.4  776.16
   741.2  778.83   867.9  830.68   887.4   837.1     975  846.84    1043  847.11
  1111.1  836.56  1159.7  824.96  1208.4  800.48  1218.1  797.86  1227.8  797.37
  1237.5  798.82    1257  806.81    1325  842.68  1334.8  846.51  1354.2  850.75
#Mann= 3 , 0 , 0
       0      .1       0   487.6    .045       0   546.1     .06       0
Bank Sta=487.6,546.1
XS Rating Curve= 0 ,0
Exp/Cntr=0.3,0.1

Type RM Length L Ch R = 1 ,111989.3,368.4,375.3,382.3
XS GIS Cut Line= 4
     1493319.048      285599.075     1493548.215      286075.637
     1493605.507      286390.742     1493524.777      286596.471
#Sta/Elev= 30
       0  903.77    97.9  860.49   127.3  850.24   156.7  842.82   176.3  837.03
   244.8  805.46   274.2   794.2   293.8  788.48   342.7  784.59   430.9  779.38
   577.3  776.54   664.7  771.99   693.8  771.63   713.2  769.34   722.9  769.79
   742.3  773.08   771.4  780.49   810.2  793.63   829.7  798.26   839.4  799.52
   849.1  800.12   887.5  798.03   897.1  796.95   916.3  792.79   925.9  791.73
   935.6  791.91   945.2   793.7   993.2  811.75  1041.2   828.5  1070.1  836.93
#Mann= 3 , 0 , 0
       0     .06       0   693.8    .045       0   742.3      .1       0
Bank Sta=693.8,742.3
XS Rating Curve= 0 ,0
Exp/Cntr=0.3,0.1

Type RM Length L Ch R = 1 ,111614  ,692.7,692,690.6
XS GIS Cut Line= 2
     1493300.819      285671.992     1493170.611        286677.2
#Sta/Elev= 30
       0  875.93    68.9  846.65   108.2  832.32   127.9  826.16   147.6  820.76
   196.8   808.7   226.3  800.79     246  794.57   265.7  787.29   275.5  785.09
   383.8  776.87   452.7  773.66     492  771.26   551.1  769.16     620   768.1
   647.7   767.9   659.3  768.55   669.2     771   688.9  778.28   698.7  780.77
   728.2   783.1   738.1  784.54   777.4  790.44   816.8  798.07   826.6  799.61
   846.3   801.6   895.5  805.26   915.2  807.29   954.6  812.37  1013.6  817.16
#Mann= 3 , 0 , 0
       0     .06       0     620    .045       0   659.3     .06       0
Bank Sta=620,659.3
XS Rating Curve= 0 ,0
Exp/Cntr=0.3,0.1

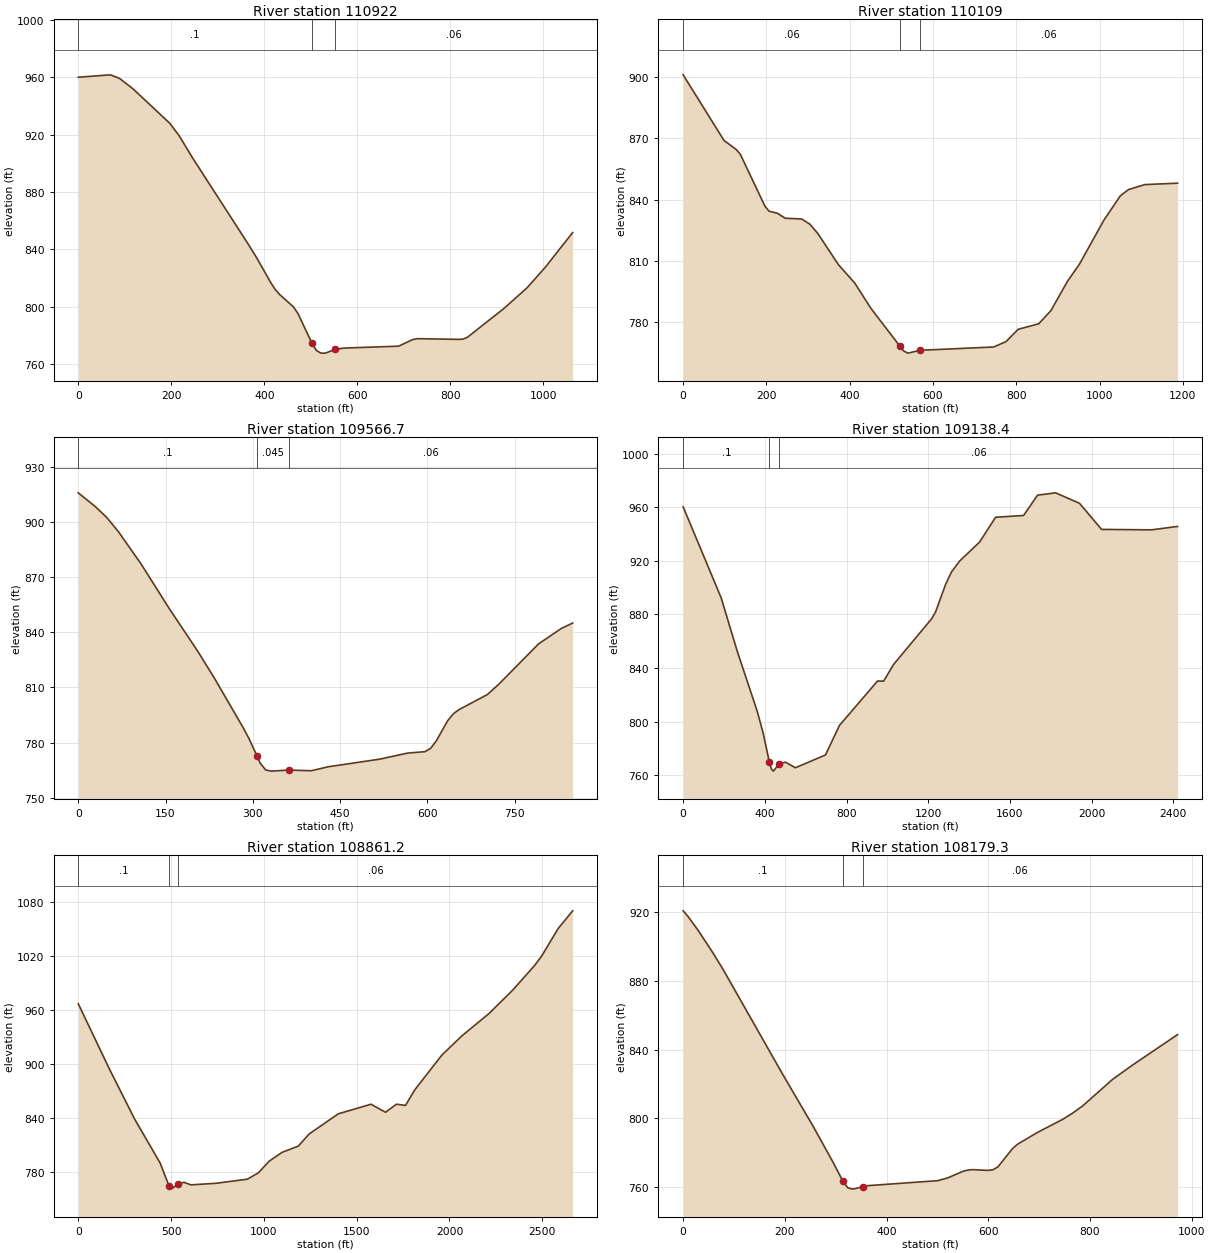
Type RM Length L Ch R = 1 ,110922  ,811.9,813,814
XS GIS Cut Line= 2
     1492709.239      285556.974     1492579.031      286611.662
#Sta/Elev= 30
       0  960.16    68.9  961.86    88.6   959.4   118.1  951.97   196.8  928.02
   216.5  919.58     246  903.74   364.1  844.38   383.8  834.07   413.3  817.14
   423.1  812.17     433  808.54   462.5  799.95   472.3   795.3   501.8  774.95
   511.7   769.6   521.5  767.68   531.4  767.68   551.3770.2245   570.7  771.19
   688.8  772.54   718.3  777.07   728.1  777.77   816.7  777.28   826.5  777.41
   836.4  778.71   915.1  798.88   964.3  813.13  1003.7  827.53  1062.7   851.8
#Mann= 3 , 0 , 0
       0      .1       0   501.8    .045       0   551.3     .06       0
Bank Sta=501.8,551.3
XS Rating Curve= 0 ,0
Exp/Cntr=0.3,0.1

Type RM Length L Ch R = 1 ,110109  ,547.2,542.3,532.7
XS GIS Cut Line= 2
     1492017.399       285358.19     1491778.684      286521.384
#Sta/Elev= 30
       0  901.05    98.1  868.92   127.6   864.5   137.4  862.11   196.3  836.82
   206.1  834.32   225.7  833.34   245.3  830.85   284.6   830.5   304.2  827.97
   323.8  823.28   372.9  808.13   412.2  799.11   451.4   786.6   520.1  768.37
   529.8  765.86   539.7  764.83   569.2  766.21   745.8  767.84   775.3  770.46
   804.7   776.5   853.8  779.18   883.2  785.62   922.5   799.8   951.9  808.44
  1010.8  830.02    1050  841.82  1069.7   844.9  1108.9  847.32  1187.4  848.01
#Mann= 3 , 0 , 0
       0     .06       0   520.1    .045       0   569.2     .06       0
Bank Sta=520.1,569.2
XS Rating Curve= 0 ,0
Exp/Cntr=0.3,0.1

Type RM Length L Ch R = 1 ,109566.7,424,428.3,433.1
XS GIS Cut Line= 2
      1491376.34      285507.929      1491501.34      286348.207
#Sta/Elev= 30
       0  916.12    29.3  908.61    48.8  902.74    68.4   895.2   107.4  877.61
   156.2   853.1   205.1  829.86   234.4  814.84   283.2  788.17   292.9  782.44
  307.13 772.675   312.5  768.79   322.2     765     332   764.4   361.3  764.99
   400.4  764.61   429.6  766.78   517.5   770.9   566.4  774.26   595.6     775
   605.4   776.8   615.2   780.9   634.7  791.86   644.5  795.68   654.2  797.92
     703  806.16   722.6  811.78   790.9  833.76     830  842.18   849.5  845.13
#Mann= 3 , 0 , 0
       0      .1       0  307.13    .045       0   361.3     .06       0
Bank Sta=307.13,361.3
XS Rating Curve= 0 ,0
Exp/Cntr=0.3,0.1

Type RM Length L Ch R = 1 ,109138.4,267.8,277.2,286.3
XS GIS Cut Line= 3
     1491053.423       285525.29     1490992.189      286533.971
     1491629.415      287791.351
#Sta/Elev= 30
       0  960.26   186.4  892.23   264.9  852.43     363   807.5   392.4  790.94
   421.9  769.84   431.7   764.7   441.5  763.02   470.9  768.54   500.4  769.73
   549.4  765.54   696.6  775.08   765.3  797.18   951.7   830.3   981.1  830.15
  1030.1  842.62  1216.1   876.7  1235.7  881.85  1284.6  902.36    1314  911.78
  1353.2  919.78    1451  933.95  1529.4   952.5  1666.4  953.82  1734.9  968.99
    1823  970.73  1940.5  962.89  2048.2  943.43  2292.9   943.1  2420.2  945.65
#Mann= 3 , 0 , 0
       0      .1       0   421.9    .045       0   470.9     .06       0
Bank Sta=421.9,470.9
XS Rating Curve= 0 ,0
Exp/Cntr=0.3,0.1

Type RM Length L Ch R = 1 ,108861.2,681.1,682,682
XS GIS Cut Line= 3
     1490981.809      285465.828     1490573.786      286270.082
     1489249.207      287431.976
#Sta/Elev= 30
       0  966.77   166.6  894.98   303.9  838.88   441.1  790.29   490.1  764.27
   499.9  761.32   539.1  767.04   568.6   768.9   607.8  766.04     745  767.83
   911.6  772.37   970.4  779.39  1029.1  792.35  1097.6  802.02  1185.7  809.02
  1244.4  822.52  1401.1  844.78  1577.2  855.41  1655.6   846.5  1714.3  855.43
  1763.2  854.09  1812.2  871.09    1959  909.87  2066.7  931.08  2213.5  955.96
  2340.8  981.88  2458.2 1009.02  2497.4 1019.78  2585.5 1050.07  2663.8 1069.73
#Mann= 3 , 0 , 0
       0      .1       0   490.1    .045       0   539.1     .06       0
Bank Sta=490.1,539.1
XS Rating Curve= 0 ,0
Exp/Cntr=0.3,0.1

Type RM Length L Ch R = 1 ,108179.3,476.6,479.9,482.8
XS GIS Cut Line= 2
     1490369.793      285244.908       1489914.1      286103.849
#Sta/Elev= 30
       0  920.91     9.8  917.54    29.5  909.52    58.9  896.25    78.6  886.73
   196.4   825.3   255.4  795.46   294.6   774.5   314.3  763.26   324.1  759.44
   333.9  758.73   353.6  760.14   363.4  760.76   500.9  763.66   520.5   765.3
     550  769.08   559.8  769.82   569.6   770.1   599.1  769.65   608.9     770
   618.8  771.63   648.2   782.5     658  784.97   697.3  791.86   746.4  799.38
   766.1  803.06   785.7  807.23   844.6  822.71   883.9  831.06   972.3  848.78
#Mann= 3 , 0 , 0
       0      .1       0   314.3    .045       0   353.6     .06       0
Bank Sta=314.3,353.6
XS Rating Curve= 0 ,0
Exp/Cntr=0.3,0.1