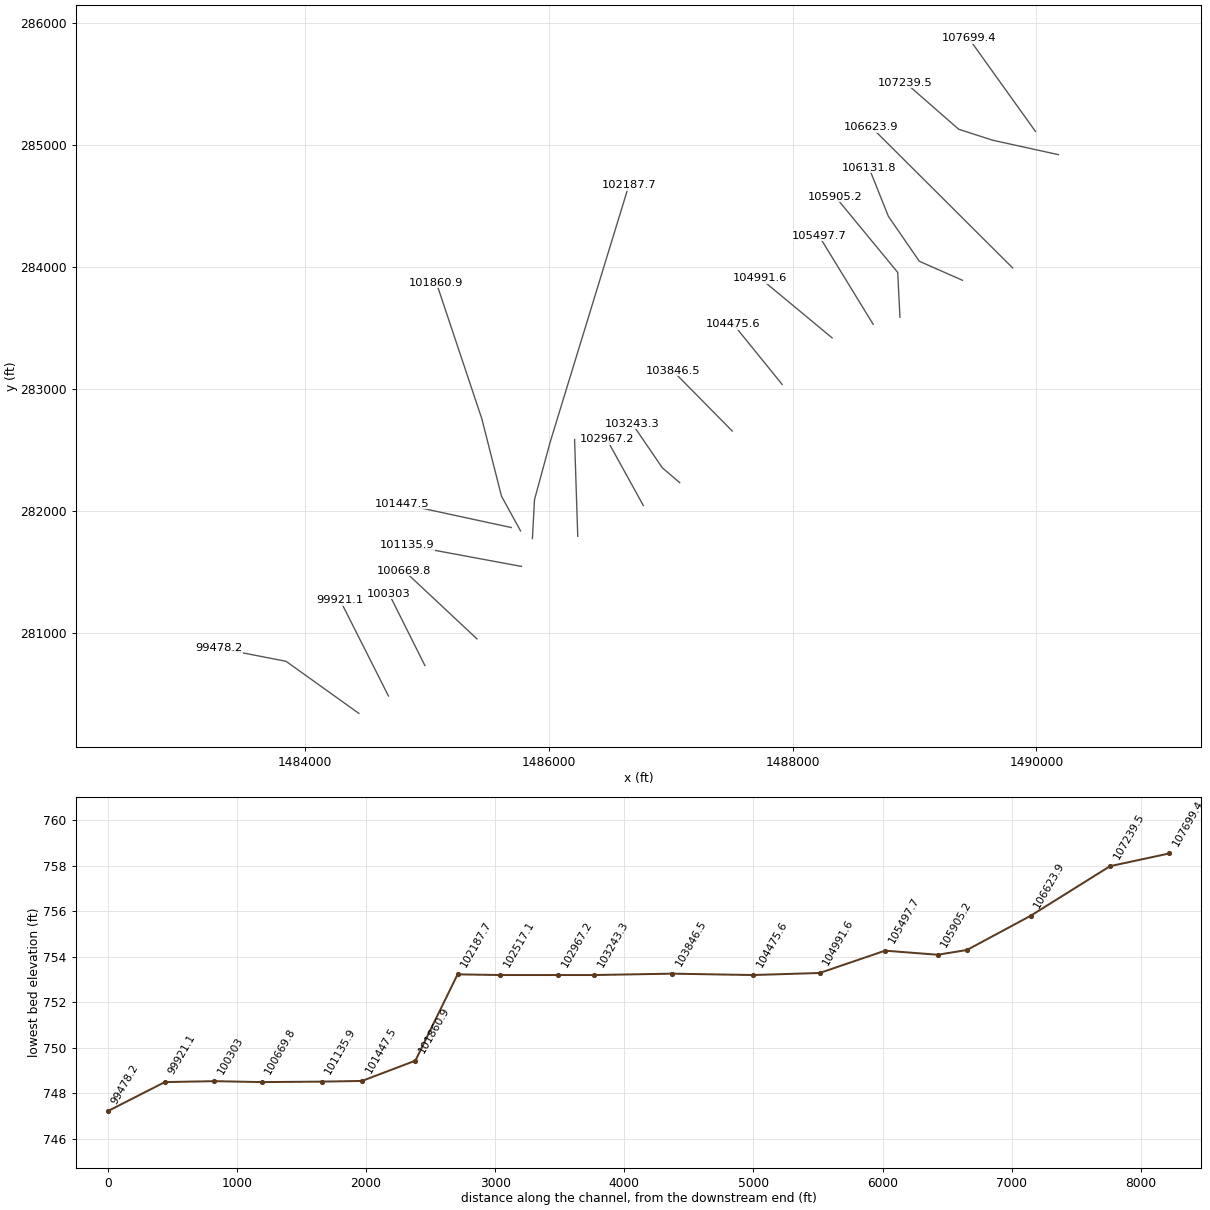
HEC-RAS study GSCR.prj: GSCR

--- GSCR.g01 (geometry) --- (continued)

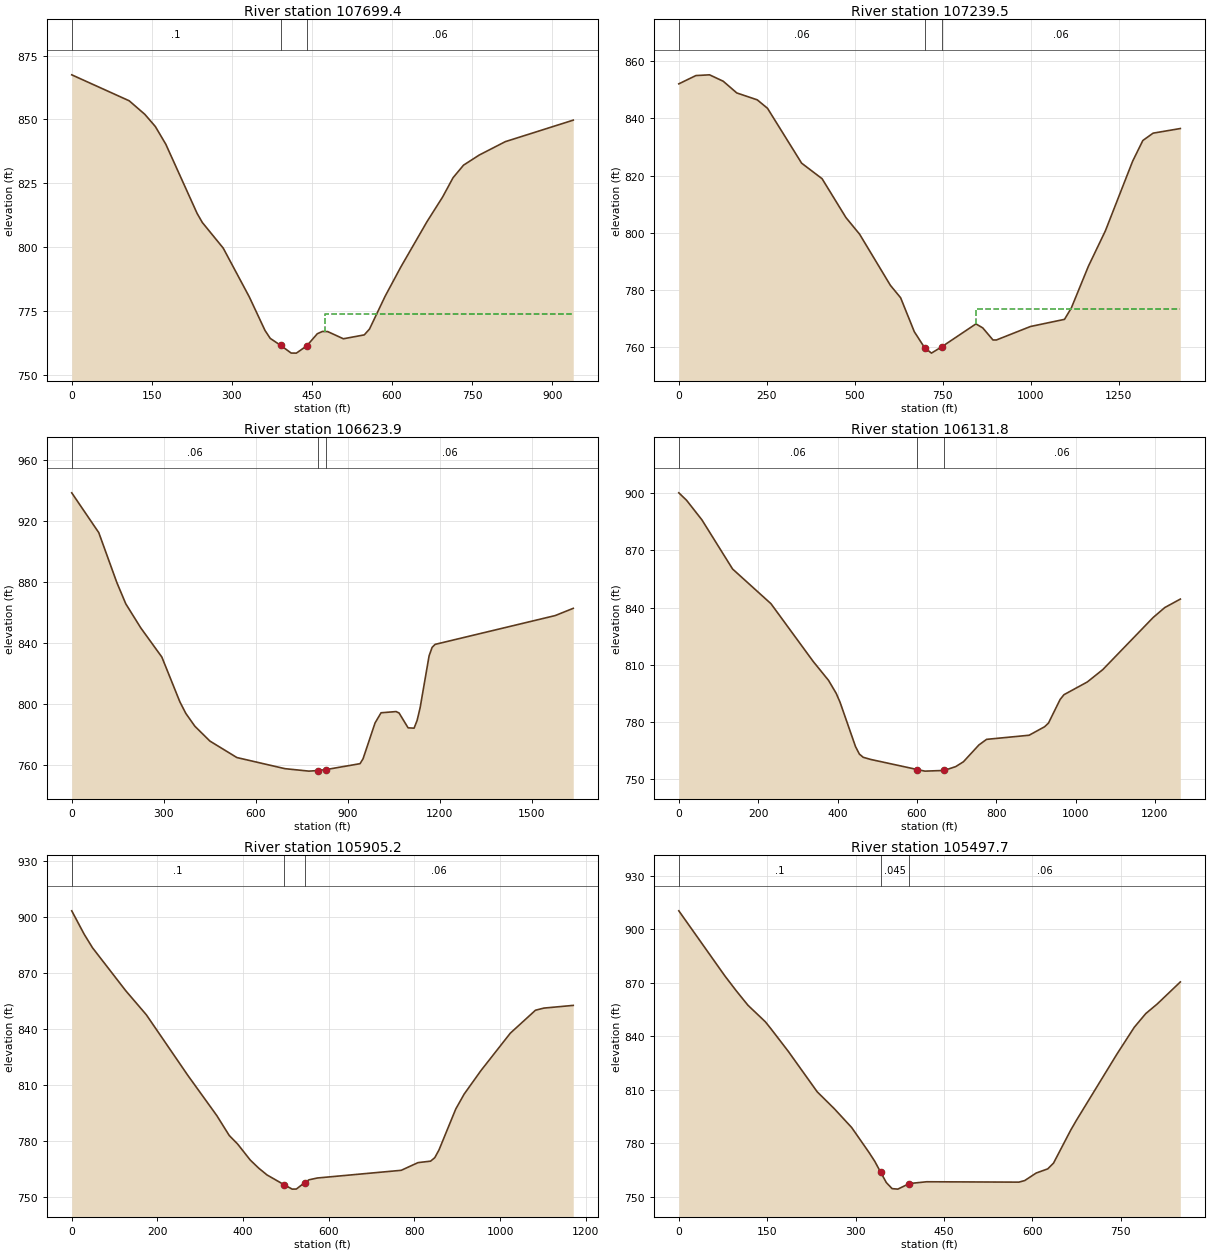
Type RM Length L Ch R = 1 ,107699.4,445.2,459.9,474
XS GIS Cut Line= 2
     1489992.225      285114.266      1489445.35      285878.155
#Sta/Elev= 30
       0  867.48   107.6  857.32     137     852   156.6  847.25   176.2  840.32
   234.9  813.22   244.6  809.69   283.8  799.64   332.7  780.52   362.1   767.4
   371.9   764.3   391.4  761.57     411  758.57   420.8  758.54   440.4   761.4
     460  766.13   469.7  767.03   479.5  766.97   508.9  764.16     548  765.68
   557.8  767.96   587.2  780.86   616.5  792.26   665.5     810   694.8  819.66
   714.4  827.23     734  832.13   763.3  836.07   812.2  841.32   939.5  849.74
#Mann= 3 , 0 , 0
       0      .1       0   391.4    .045       0   440.4     .06       0
#XS Ineff= 2 , 0
                          475.36          773.67
Permanent Ineff=
       F       F
Bank Sta=391.4,440.4
XS Rating Curve= 0 ,0
Exp/Cntr=0.3,0.1

Type RM Length L Ch R = 1 ,107239.5,625.3,615.5,603.5
XS GIS Cut Line= 4
     1490180.123      284924.162     1489640.229      285042.651
     1489362.415      285132.495     1488924.951      285514.874
#Sta/Elev= 30
       0  852.05    48.5  854.94    87.3   855.2   126.1  852.97   164.8  848.87
     223  846.46   252.1  843.51   349.1  824.34   407.3  818.91   475.2  805.32
     514  799.52   601.4  781.68   630.6  777.32   669.5  765.45   698.7  759.89
   718.2  757.98   747.4  760.18   844.7  768.19   864.1  766.79   893.1  762.58
   902.8  762.57   999.7  767.28  1096.5  769.78  1115.9  773.76  1164.3   788.3
  1212.7   800.7  1290.2  825.03  1319.2  832.26  1348.3  834.82  1425.8  836.44
#Mann= 3 , 0 , 0
       0     .06       0   698.7    .045       0   747.4     .06       0
#XS Ineff= 2 , 0
                          844.35          773.43
Permanent Ineff=
       F       F
Bank Sta=698.7,747.4
XS Rating Curve= 0 ,0
Exp/Cntr=0.3,0.1

Type RM Length L Ch R = 1 ,106623.9,498.2,492.2,485.6
XS GIS Cut Line= 2
     1489805.593      283994.474     1488646.739      285148.988
#Sta/Elev= 30
       0  938.37    88.2  912.25   146.9  879.63   176.3  865.55   225.3  849.73
   293.9  830.64   352.6  801.31   372.2  793.63   401.6  785.26   450.6  775.53
   538.7   764.7   695.5  757.41   773.8   755.8   803.2   756.2   829.9756.8273
   940.3  760.69   950.1  763.86   989.3  787.39  1008.9  794.08  1057.9  794.87
  1067.7  793.93  1097.1   784.2  1116.6  783.99  1126.4  788.98  1136.2  797.25
  1165.6  831.43  1175.4  836.97  1185.2  838.95    1577  857.85  1635.8   862.6
#Mann= 3 , 0 , 0
       0     .06       0   803.2    .045       0   829.9     .06       0
Bank Sta=803.2,829.9
XS Rating Curve= 0 ,0
Exp/Cntr=0.3,0.1

Type RM Length L Ch R = 1 ,106131.8,225.8,226.5,228.2
XS GIS Cut Line= 4
     1489393.701      283893.346     1489039.534      284049.596
     1488786.062      284417.651      1488626.34      284816.957
#Sta/Elev= 30
       0  900.18    19.4   896.3    58.1  886.04   135.5  860.25   232.3  842.05
   338.7  811.79   377.4  801.86   396.8  795.02   406.5  790.34   445.4  767.15
   455.1  763.24   464.8  761.54   484.2   760.4   600.8  755.14   620.3   754.3
   668.8  754.65     698  756.68   717.4  759.21   756.3     768   775.7  770.95
   882.9  773.11     922  777.57   931.7  779.48   961.1  791.86   970.8  794.37
  1029.5  801.02  1068.6  807.51  1195.6  834.83    1225  840.06  1264.1  844.48
#Mann= 3 , 0 , 0
       0     .06       0   600.8    .045       0   668.8     .06       0
Bank Sta=600.8,668.8
XS Rating Curve= 0 ,0
Exp/Cntr=0.3,0.1

Type RM Length L Ch R = 1 ,105905.2,406.8,407.6,405.9
XS GIS Cut Line= 3
     1488880.644      283590.828     1488862.415      283958.016
     1488351.998      284577.808
#Sta/Elev= 30
       0  903.33      29   890.8    48.4  883.55   125.8  860.56   174.2  847.56
   270.9  815.12   338.6  793.53   367.6  782.86   387.2  778.28   416.6  769.71
   436.2  765.38   455.8   761.7   494.9  756.55   514.5  754.09   524.3  754.14
   543.9  757.61   553.7  759.08   573.3  760.06   769.1  764.18   808.3  768.31
   837.6  769.09   847.4  770.96   857.2  775.09   896.4  797.08     916  805.06
   955.1  817.65  1023.7  837.72  1082.4  850.02    1102  851.17  1170.6  852.62
#Mann= 3 , 0 , 0
       0      .1       0   494.9    .045       0   543.9     .06       0
Bank Sta=494.9,543.9
XS Rating Curve= 0 ,0
Exp/Cntr=0.3,0.1

Type RM Length L Ch R = 1 ,105497.7,497.8,506.1,513.3
XS GIS Cut Line= 2
     1488661.062      283532.235     1488216.618      284257.929
#Sta/Elev= 30
       0  910.28    78.2  873.76    97.8  865.31   117.4  857.31   146.7  848.12
   156.5  844.09   185.8  831.48   234.8  808.83   264.1  799.26   293.4  788.76
   322.8   774.8   332.6   769.8   342.4  763.78   352.1  757.95   361.9  754.55
   371.6  754.27   391.2   757.4   420.6   758.4   577.1  758.19   586.9  759.07
   606.4   763.3     626  765.62   635.8  768.85   665.1  787.41   674.9  792.99
   743.4  829.97   772.7  844.94   792.3  852.67   811.8  858.06     851  870.42
#Mann= 3 , 0 , 0
       0      .1       0   342.4    .045       0   391.2     .06       0
Bank Sta=342.4,391.2
XS Rating Curve= 0 ,0
Exp/Cntr=0.3,0.1

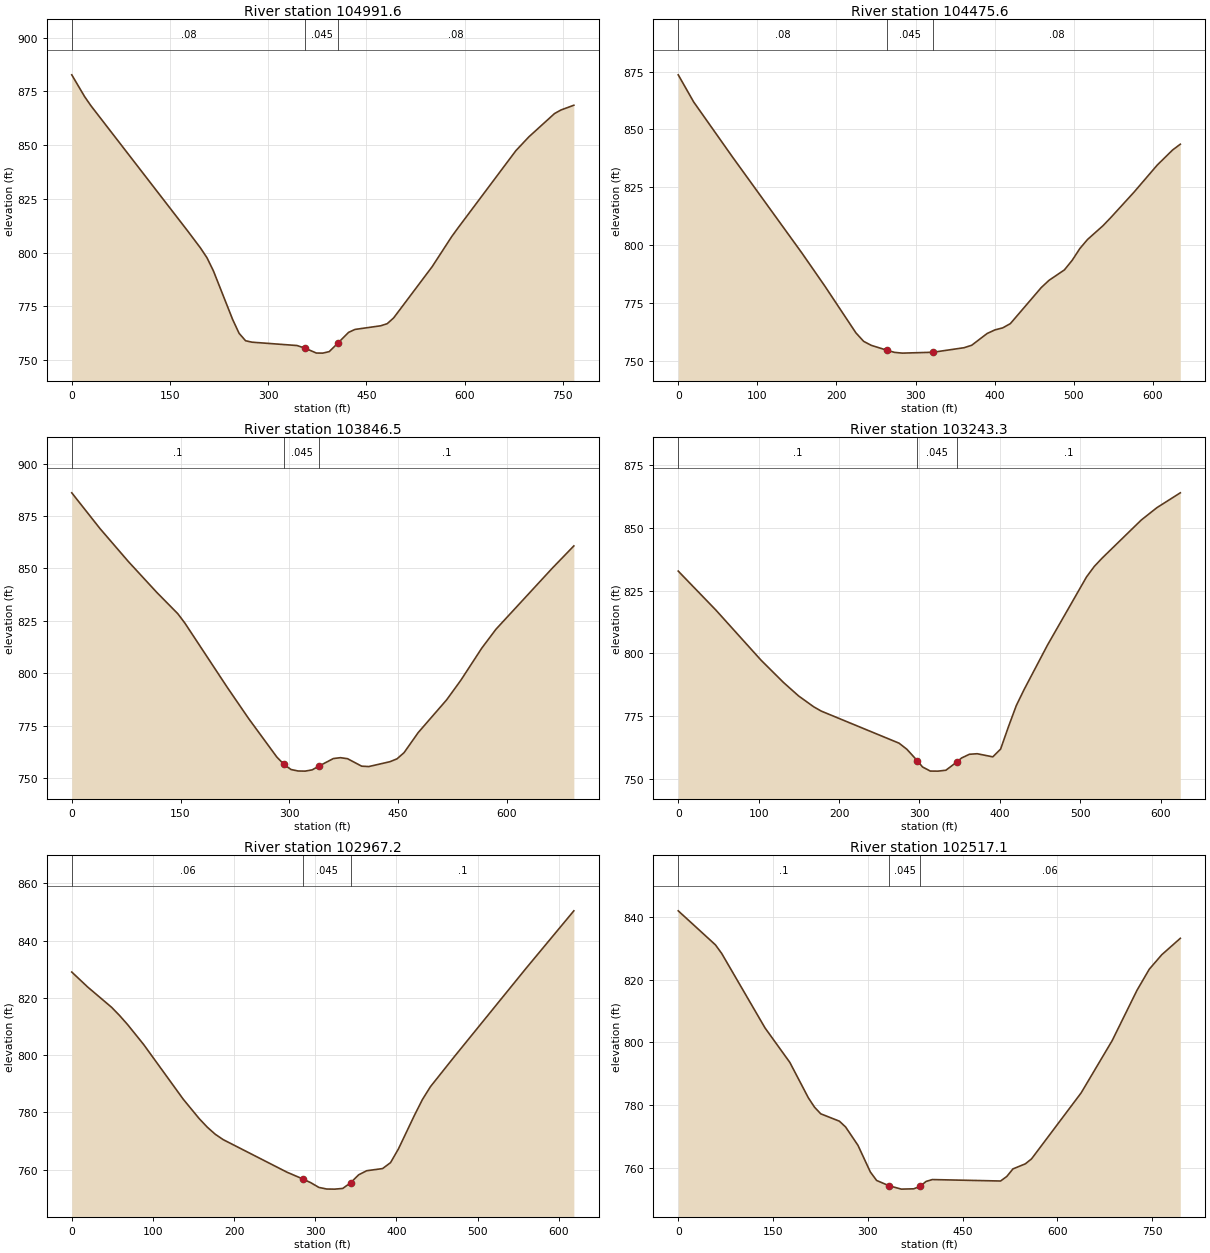
Type RM Length L Ch R = 1 ,104991.6,520.4,516,510.8
XS GIS Cut Line= 2
     1488324.257      283421.124     1487733.979      283910.707
#Sta/Elev= 30
       0  882.74    19.7  872.57    29.5  868.27     177  810.13   196.6   802.2
   206.5  797.67   216.3  791.59   245.8  768.89   255.6   762.5   265.5  759.05
   275.3  758.38   344.1  756.82   356.4755.5784   373.6  753.33   383.4  753.29
   393.3     754   406.4757.9246   422.8  762.94   432.6  764.31   471.9  766.01
   481.8  766.98   491.6  769.65   550.6  793.55   580.1  807.39   589.9   811.5
   678.4  847.47   698.1  853.86   737.4  864.73   747.2  866.38   766.9   868.6
#Mann= 3 , 0 , 0
       0     .08       0   356.4    .045       0   406.4     .08       0
Bank Sta=356.4,406.4
XS Rating Curve= 0 ,0
Exp/Cntr=0.3,0.1

Type RM Length L Ch R = 1 ,104475.6,627.4,629.1,627.2
XS GIS Cut Line= 2
     1487914.534      283039.179     1487515.229      283532.235
#Sta/Elev= 30
       0  873.63    19.5   861.9    68.3  838.21   156.2  796.56   185.5   782.1
   224.5  761.99   234.3   758.3     244  756.56   263.6  754.47   273.3  753.53
   283.1   753.2   322.1  753.58   361.2  755.54   370.9  756.61   390.4   761.7
   400.2  763.25     410  764.12   419.7  765.96   458.8  781.58   468.5  784.68
     488  789.21   497.8  793.34   507.6  798.48   517.3  802.39   536.9  808.38
   546.6  811.84   575.9  822.82   605.2  834.53   624.7  841.09   634.5  843.61
#Mann= 3 , 0 , 0
       0     .08       0   263.6    .045       0   322.1     .08       0
Bank Sta=263.6,322.1
XS Rating Curve= 0 ,0
Exp/Cntr=0.3,0.1

Type RM Length L Ch R = 1 ,103846.5,607.1,603.2,599
XS GIS Cut Line= 2
     1487504.812      282657.235     1487018.701       283150.29
#Sta/Elev= 30
       0  886.11      39  869.01      78  853.33     117  838.67   146.3  828.38
     156  823.92   214.5  793.22   243.8  778.42   282.8  759.98   292.6756.4848
   302.3  754.04   312.1  753.33   321.8  753.26   331.6  753.87   341.3  755.74
   360.8  759.27   370.6  759.68   380.3  759.19   399.8  755.63   409.6  755.44
   438.8  757.76   448.6  759.14   458.3   762.1   477.8  771.68   516.9  787.26
   536.4  796.56   565.6  812.06   585.1  821.03   663.1  850.29   692.4  860.77
#Mann= 3 , 0 , 0
       0      .1       0   292.6    .045       0   341.3      .1       0
Bank Sta=292.6,341.3
XS Rating Curve= 0 ,0
Exp/Cntr=0.3,0.1

Type RM Length L Ch R = 1 ,103243.3,278.1,276.1,273.8
XS GIS Cut Line= 3
     1487074.257      282233.624     1486931.895      282355.151
     1486685.368      282716.262
#Sta/Elev= 30
       0  832.75    46.8  817.26     103  797.32     131  788.43   149.7   783.1
   168.5  778.78   177.8  777.08   274.6  764.32   284.3  761.91   297.2757.3911
   303.8  754.86   313.5  753.22   323.2   753.2   332.9  753.56   347.2757.0132
   352.4  758.43   362.1   759.9   371.8  760.12   391.2  758.88   400.9  761.96
   410.7  770.88   420.4  779.26   430.1  785.62   459.2  803.32   507.8  830.45
   517.5  834.64   527.2  837.92   575.8  853.05   595.3  857.98   624.4  863.88
#Mann= 3 , 0 , 0
       0      .1       0   297.2    .045       0   347.2      .1       0
Bank Sta=297.2,347.2
XS Rating Curve= 0 ,0
Exp/Cntr=0.3,0.1

Type RM Length L Ch R = 1 ,102967.2,461.1,450.1,439
XS GIS Cut Line= 2
     1486775.645      282046.124     1486477.034       282587.79
#Sta/Elev= 30
       0  829.05    19.6  823.82    49.1  816.72    58.9  813.86    68.7  810.72
    88.4  803.79   137.4  784.59   157.1   777.8   166.9  774.86   176.7  772.39
   186.5   770.5   265.1  759.12   284.7  756.74   294.5  755.44   304.4   753.8
   314.2  753.23     324   753.2   333.8  753.44   343.6  755.44   353.4   758.2
   363.3  759.63   382.9  760.38   392.7  762.46   402.5   767.3   422.2  779.03
     432  784.52   441.8  788.98   471.3  799.49   559.6  830.34   618.5  850.44
#Mann= 3 , 0 , 0
       0     .06       0   284.7    .045       0   343.6      .1       0
Bank Sta=284.7,343.6
XS Rating Curve= 0 ,0
Exp/Cntr=0.3,0.1

Type RM Length L Ch R = 1 ,102517.1,336.1,329.4,322.7
XS GIS Cut Line= 2
     1486237.885      281793.953     1486211.843      282588.224
#Sta/Elev= 30
       0     842    58.9  831.14    68.7  828.43   137.4  804.63   176.6  793.65
     206  782.32   215.8  779.33   225.6  777.23   255.1  774.88   264.9  773.04
   284.5  767.17   304.1  758.67     314  755.97   333.6  754.28   353.2   753.2
   372.8   753.3   382.6  754.08   392.4  755.66   402.2  756.25   510.2  755.79
     520  757.23   529.8  759.65   549.4  761.27   559.2  762.85   637.7   783.9
   686.8  800.57     726  816.59   745.6  823.38   765.3  827.98   794.7  833.23
#Mann= 3 , 0 , 0
       0      .1       0   333.6    .045       0   382.6     .06       0
Bank Sta=333.6,382.6
XS Rating Curve= 0 ,0
Exp/Cntr=0.3,0.1

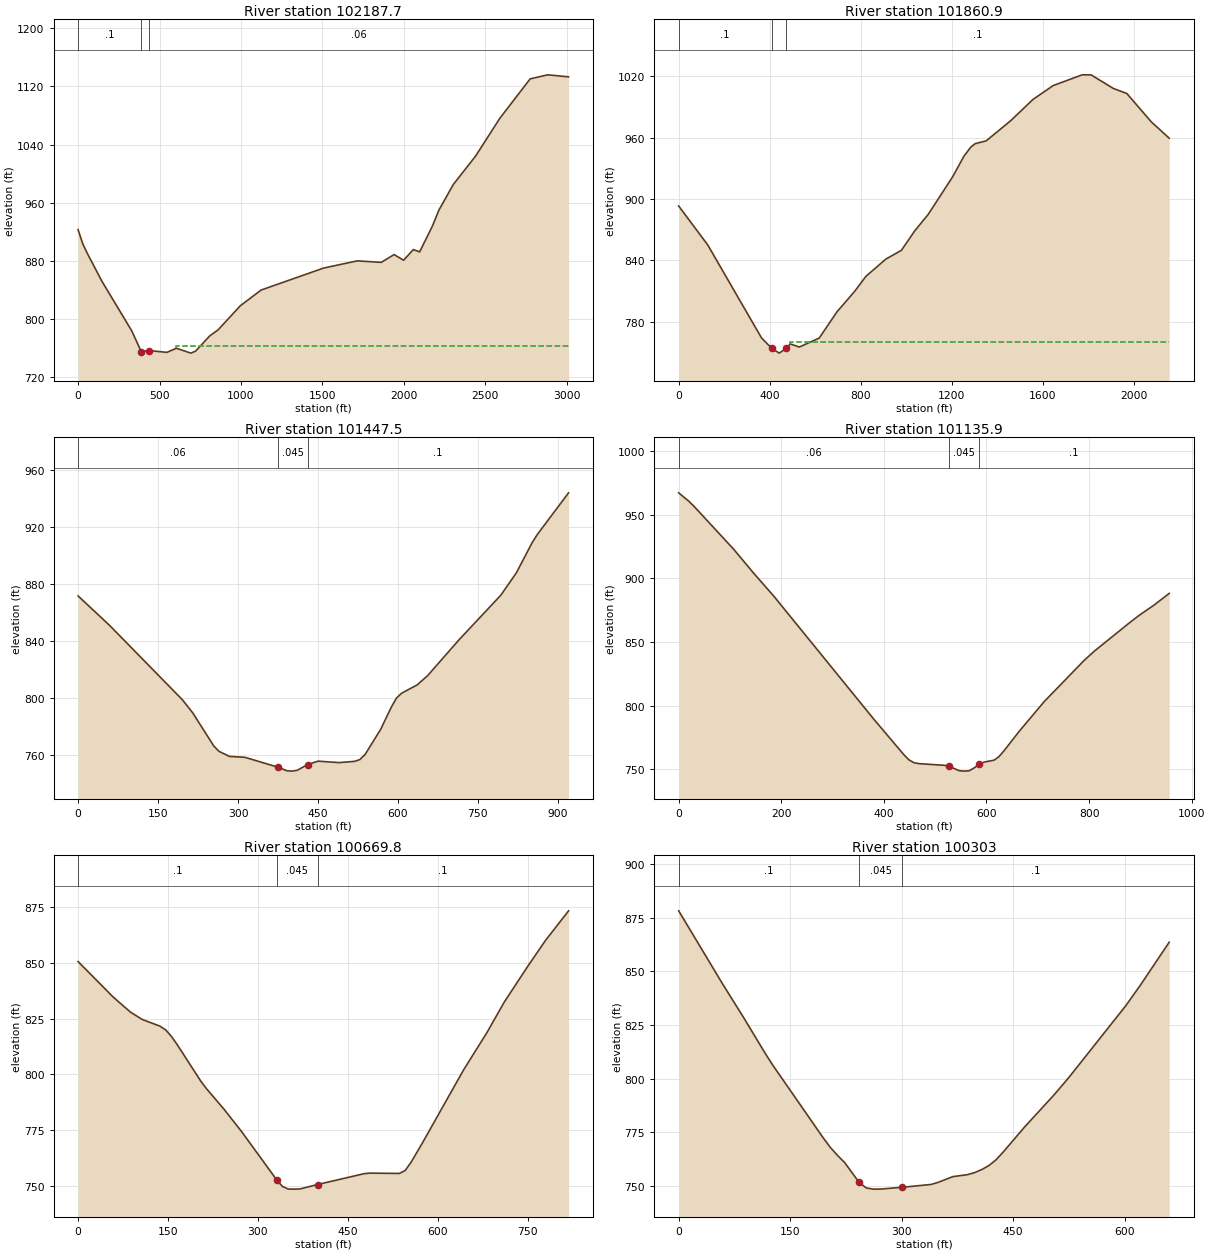
Type RM Length L Ch R = 1 ,102187.7,314.9,326.8,338.3
XS GIS Cut Line= 4
     1485865.923       281775.29     1485883.284      282094.735
     1486011.757      282566.957     1486656.686      284671.558
#Sta/Elev= 30
       0  923.06    29.1  903.38    58.2   889.8   145.4  852.47   329.7  783.79
   388.4     755   437.4  756.77     545  754.27   603.8  759.95   691.8  753.23
   721.2  755.95   809.3  777.17   858.4  784.98     996  818.39  1123.8  840.01
    1507   870.2  1713.4   880.1  1860.8  878.06  1939.4  888.76  1998.3     881
  2057.3  895.62  2096.6   892.5  2175.2  928.16  2214.5   949.8    2303  985.12
  2440.6 1024.44    2588 1075.99  2774.7 1130.38  2882.8 1135.94  3010.5 1133.16
#Mann= 3 , 0 , 0
       0      .1       0   388.4    .045       0   437.4     .06       0
#XS Ineff= 2 , 0
                          603.42          762.59
Permanent Ineff=
       F       F
Bank Sta=388.4,437.4
XS Rating Curve= 0 ,0
Exp/Cntr=0.3,0.1

Type RM Length L Ch R = 1 ,101860.9,388.3,413.4,438.5
XS GIS Cut Line= 4
     1485768.701       281837.79     1485612.451      282122.512
     1485451.516      282756.195     1485078.561      283872.078
#Sta/Elev= 30
       0  893.14   127.9  855.06   363.8  764.36   409.1754.0729   441.9  749.44
   471.2  754.04   490.7  758.43   529.7  755.36   617.5  764.17   695.6  789.83
   773.7  809.95   822.4  824.41   910.3  841.31   978.6  849.88  1037.4  868.94
  1096.2  884.93  1204.1  921.82  1253.1   941.7  1282.5  950.45  1302.1  954.03
  1351.2  956.81    1459  976.53    1557  997.33  1645.3  1010.8  1772.8  1021.3
    1812 1021.27    1910 1007.96  1968.8 1003.09  2076.7   975.3  2155.1  959.42
#Mann= 3 , 0 , 0
       0      .1       0   409.1    .045       0   471.2      .1       0
#XS Ineff= 2 , 0
                          491.05          760.64
Permanent Ineff=
       F       F
Bank Sta=409.1,471.2
XS Rating Curve= 0 ,0
Exp/Cntr=0.3,0.1

Type RM Length L Ch R = 1 ,101447.5,310.9,311.6,312.2
XS GIS Cut Line= 2
     1485692.312      281865.568     1484793.007      282060.012
#Sta/Elev= 30
       0  871.71    58.7  851.15   195.8  798.68   215.3   789.4   254.5  766.28
   264.3  762.49   283.9   758.9   313.2  758.24   375.5751.2513   391.5  748.83
   401.3  748.55   411.1  749.14   430.7  753.19   450.3  755.56   489.4  754.55
   518.8  755.42   528.6  756.67   538.4  760.24   567.7  777.98   587.3  793.29
   597.1  799.82   606.9  803.33   636.2  809.18   655.8  815.71   714.5  840.82
   792.8  872.12   822.2  887.94   851.6  909.04   861.4  914.85   920.1  944.17
#Mann= 3 , 0 , 0
       0     .06       0   375.5    .045       0   430.7      .1       0
Bank Sta=375.5,430.7
XS Rating Curve= 0 ,0
Exp/Cntr=0.3,0.1

Type RM Length L Ch R = 1 ,101135.9,479,466.1,453
XS GIS Cut Line= 2
     1485776.477      281546.558     1484836.373      281721.037
#Sta/Elev= 30
       0  967.33    19.5  960.83    29.3  956.98   107.3  922.93   146.4  904.05
   185.4  886.11   380.5   789.3     439  761.43   448.8   757.4   458.6  755.15
   468.3  754.41   517.1  753.13   526.9   752.4   546.4   748.9   556.1  748.52
   565.9  748.76   575.6  750.92   585.4  753.84   595.2  755.61   614.7   757.1
   624.4  759.93   634.2  764.52   663.5  779.65   712.2  803.04   790.3  835.53
   809.8  842.69   878.1  864.93   897.6     871   926.9  879.14   956.2  888.26
#Mann= 3 , 0 , 0
       0     .06       0   526.9    .045       0   585.4      .1       0
Bank Sta=526.9,585.4
XS Rating Curve= 0 ,0
Exp/Cntr=0.3,0.1

Type RM Length L Ch R = 1 ,100669.8,374.8,366.8,358.8
XS GIS Cut Line= 2
     1485411.062      280952.374      1484813.84      281511.401
#Sta/Elev= 30
       0  850.54    58.4  834.66    87.6  827.82   107.1  824.56   136.3  821.61
   146.1  819.91   155.8  816.94   165.6  813.18   204.5  796.99   214.2  793.52
   243.5   784.3   272.7  774.31   331.2752.6692   340.8  749.71   350.6  748.54
   360.3   748.5   370.1  748.58   399.3  750.56   477.2  755.44   486.9  755.67
   535.6  755.53   545.4  756.84   555.1  760.44   574.6  769.36   642.7  801.86
   681.7  818.62   710.9  832.42   749.9  848.39   779.1  859.86     818  873.28
#Mann= 3 , 0 , 0
       0      .1       0   331.2    .045       0   399.3      .1       0
Bank Sta=331.2,399.3
XS Rating Curve= 0 ,0
Exp/Cntr=0.3,0.1

Type RM Length L Ch R = 1 ,100303  ,381.8,381.9,382
XS GIS Cut Line= 2
     1484983.979      280733.624      1484688.84      281323.901
#Sta/Elev= 30
       0  878.14    58.2   844.6    87.4  828.42   116.5  811.72   126.2  806.48
   194.1   772.6   203.8  768.08   213.5  764.32   223.2  760.96   242.6   751.8
   252.3  749.09     262  748.54   271.7  748.57   300.9   749.4   339.7  750.72
   349.4  751.73   368.8  754.35   388.2  755.26   397.9  756.19   407.6  757.61
   417.3  759.48     427  762.18   436.7  765.83   465.8  777.62   504.7  792.28
   524.1  800.15   533.8  804.36   601.7     834   621.1  843.45     660  863.51
#Mann= 3 , 0 , 0
       0      .1       0   242.6    .045       0   300.9      .1       0
Bank Sta=242.6,300.9
XS Rating Curve= 0 ,0
Exp/Cntr=0.3,0.1

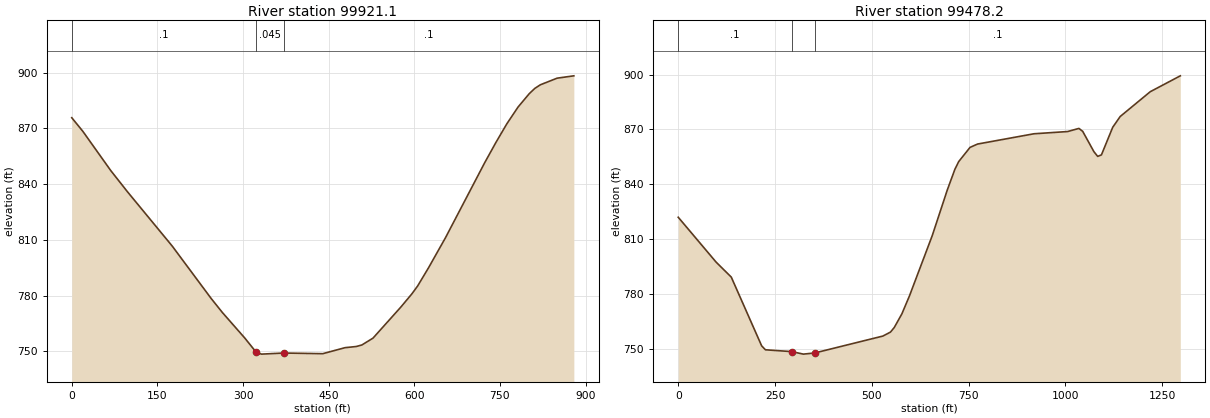
Type RM Length L Ch R = 1 ,99921.1 ,429.2,442.9,455.3
XS GIS Cut Line= 2
     1484685.368      280483.624       1484289.1       281268.78
#Sta/Elev= 30
       0  875.71    19.5  868.34    68.4  847.23    97.7  835.81   175.9  806.67
   244.3   778.4   263.8  770.91   302.9  757.22   322.5  749.74   332.2   748.5
   371.3  749.09   439.7  748.74   478.8  751.98   498.4   752.6   508.2  753.43
   527.7  757.11   576.6  773.87   596.1  781.05   605.9  785.18   625.4  795.19
   654.7  811.16   723.1  851.36   742.7  862.25   762.2  872.47   781.8  881.46
   801.3  888.61   811.1  891.47   820.8  893.42   850.2  896.99   879.5  898.25
#Mann= 3 , 0 , 0
       0      .1       0   322.5    .045       0   371.3      .1       0
Bank Sta=322.5,371.3
XS Rating Curve= 0 ,0
Exp/Cntr=0.3,0.1

Type RM Length L Ch R = 1 ,99478.2 ,356.2,373.2,391.2
XS GIS Cut Line= 3
     1484442.312      280341.262      1483845.09      280768.346
     1483293.007      280875.985
#Sta/Elev= 30
       0  822.03    97.9  797.49     137  789.31   215.4  751.77   225.2  749.59
   293.7  748.58   323.1  747.22   352.5747.8554   528.6   757.1   548.2  759.27
     558   761.8   577.6  769.23   597.2  779.05   655.9  811.91   695.1  837.06
   714.6  848.28   724.4  852.46   753.6  860.21     773  862.04   918.5  867.65
  1005.8  868.88  1034.8  870.59  1044.6  868.98  1073.6  857.87  1083.3   855.3
    1093  856.13  1122.1  871.19  1141.5  877.11  1219.1  890.65  1296.7  899.33
#Mann= 3 , 0 , 0
       0      .1       0   293.7    .045       0   352.5      .1       0
Bank Sta=293.7,352.5
XS Rating Curve= 0 ,0
Exp/Cntr=0.3,0.1