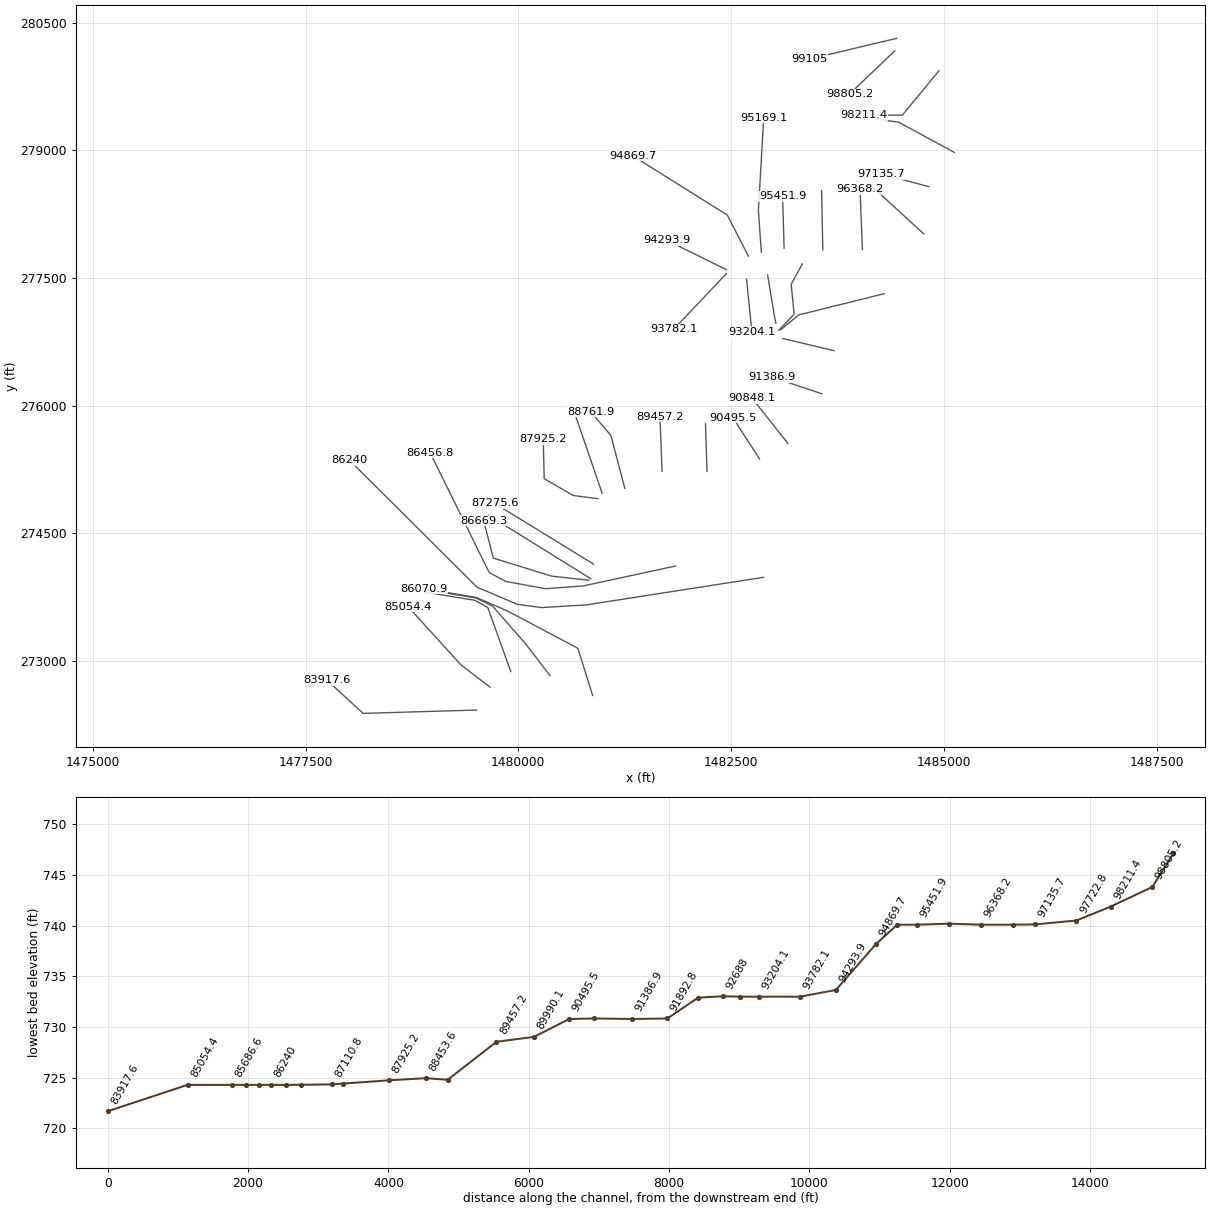
HEC-RAS study GSCR.prj: GSCR

--- GSCR.g01 (geometry) --- (continued)

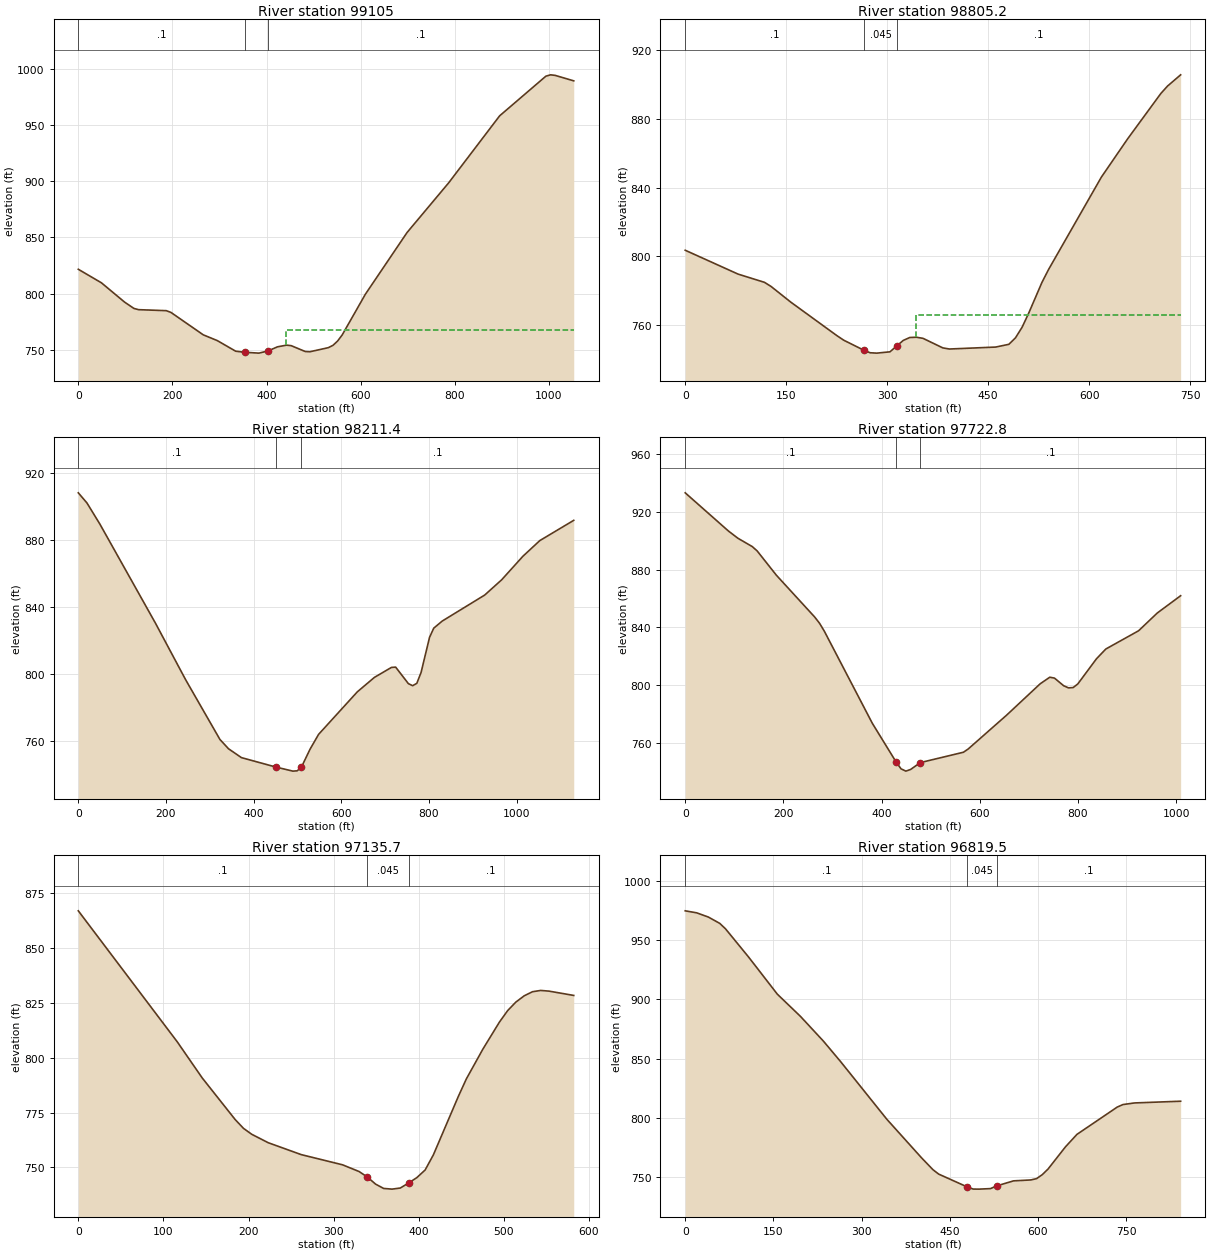
Type RM Length L Ch R = 1 ,99105   ,287.9,299.8,311.8
XS GIS Cut Line= 2
     1484445.784      280316.957     1483421.479      280073.901
#Sta/Elev= 30
       0  821.69    49.2  809.63    98.4  792.48   118.1  786.89   127.9  785.77
   186.9  784.88   196.8  783.34   265.6  763.38   295.2   758.3   334.5  748.83
   354.2  747.87   383.7  747.13   403.4   749.1   423.1  752.71   442.7  754.23
   452.6  753.74   482.1  748.59   491.9  748.33   531.3  751.99   541.1  754.03
     551  757.88   560.8  763.33     610  799.48   698.6  854.36   787.1  898.57
   895.3  958.09   993.7  993.39  1003.6  994.57  1013.4  994.07  1052.8  989.22
#Mann= 3 , 0 , 0
       0      .1       0   354.2    .045       0   403.4      .1       0
#XS Ineff= 2 , 0
                          441.07          767.86
Permanent Ineff=
       F       F
Bank Sta=354.2,403.4
XS Rating Curve= 0 ,0
Exp/Cntr=0.3,0.1

Type RM Length L Ch R = 1 ,98805.2 ,591.2,593.9,596.5
XS GIS Cut Line= 2
     1484422.311      280168.953     1483890.229      279660.707
#Sta/Elev= 30
       0  803.58    78.5  789.72   117.7  784.94   127.5  782.55     157  773.38
   225.6  753.89   235.5  751.31   265.9745.3949   274.7  744.03   284.5  743.82
   304.1  744.58     314  747.92   323.8   751.2   333.6   752.9   343.4  753.05
   353.2   752.4   382.6  746.86   392.4  746.21   461.1  747.34   480.7  748.94
   490.5   752.7   500.4   758.9   510.2  767.09   529.8  784.88   539.6  792.37
   618.1  846.07   657.3  868.41   706.4  894.63   716.2  898.89   735.8  905.47
#Mann= 3 , 0 , 0
       0      .1       0   265.9    .045       0     314      .1       0
#XS Ineff= 2 , 0
                          342.51          766.14
Permanent Ineff=
       F       F
Bank Sta=265.9,314
XS Rating Curve= 0 ,0
Exp/Cntr=0.3,0.1

Type RM Length L Ch R = 1 ,98211.4 ,519.8,488.5,457.3
XS GIS Cut Line= 3
     1484942.312      279935.012     1484511.757      279414.179
     1484056.895      279414.179
#Sta/Elev= 30
       0   908.3    19.6  902.28      49  889.72   176.3  830.24   244.8   796.6
   323.2  760.82   342.8  755.26   372.2  749.97   450.5  744.35   489.7  741.89
   499.5  742.07   509.3  744.34   528.8  754.98   548.4  763.88   636.6  789.27
   675.8  797.95   714.5  803.89   724.2  804.08   753.2  794.22   762.9  792.97
   772.5  794.39   782.2  800.87   801.6  821.94   811.2  827.39   830.6  831.64
   927.4  847.17   966.1  856.28  1014.5  870.34  1053.2  879.74  1130.6  891.85
#Mann= 3 , 0 , 0
       0      .1       0   450.5    .045       0   509.3      .1       0
Bank Sta=450.5,509.3
XS Rating Curve= 0 ,0
Exp/Cntr=0.3,0.1

Type RM Length L Ch R = 1 ,97722.8 ,581.8,587.2,592.5
XS GIS Cut Line= 3
     1485122.868      278976.679      1484470.09      279330.846
     1484206.201       279369.04
#Sta/Elev= 30
       0  933.11      88  906.69   107.5  901.64   136.8  895.86   146.6  892.88
   185.7   876.1   263.8  847.15   273.6  842.87   283.4  837.36   381.1  773.67
     430  746.64   439.7   742.1   449.5  740.51   459.3  741.69   478.8  746.39
   566.8  753.58   576.5  755.83   654.7  779.23   723.1  800.93   742.7   805.5
   752.2   804.9   771.2  799.55   780.8  798.13   790.3  798.34   799.8  800.86
   837.9  818.29   856.9  825.02   923.6  837.64   961.7  849.94  1009.3   861.9
#Mann= 3 , 0 , 0
       0      .1       0     430    .045       0   478.8      .1       0
Bank Sta=430,478.8
XS Rating Curve= 0 ,0
Exp/Cntr=0.3,0.1

Type RM Length L Ch R = 1 ,97135.7 ,327.8,316.2,304.7
XS GIS Cut Line= 2
     1484824.257      278573.901     1484261.757      278723.207
#Sta/Elev= 30
       0  867.01   116.4   807.2   145.5  790.85   184.3  771.84     194  767.85
   203.7  765.14   223.1  761.29   261.9  755.86   310.4  751.22   329.8  748.16
   339.5  745.66   349.2  742.42   358.7  740.44   368.6  740.13   378.3  740.64
     388  742.93   397.7  745.38   407.4  748.84   417.1  755.74   446.2  782.18
   455.9  790.42   475.3  803.98   494.7  816.28   504.4  821.53   514.1  825.44
   523.8  828.26   533.5  830.12   543.2  830.71   552.9   830.4     582  828.44
#Mann= 3 , 0 , 0
       0      .1       0   339.5    .045       0     388      .1       0
Bank Sta=339.5,388
XS Rating Curve= 0 ,0
Exp/Cntr=0.3,0.1

Type RM Length L Ch R = 1 ,96819.5 ,468.4,451.3,433.8
XS GIS Cut Line= 2
      1484761.72      278021.384     1484140.193      278590.828
#Sta/Elev= 30
       0  974.56    19.6  972.86    39.2  969.35    58.8  963.98    68.6  959.38
   107.8  935.65   156.8  904.32     196  885.68   235.2  864.76   264.6  847.42
   343.1  798.94   401.9   766.6   421.5   756.5   431.3  752.76     480741.9227
   490.1  740.14   499.9   740.1   519.5  740.54     530742.8185   558.7  747.06
   588.1  747.84   597.9  748.95   607.7  752.35   617.5  757.09   646.9  775.65
   666.5   786.2   735.1  809.22   744.9  811.35   764.5  812.71     843  814.16
#Mann= 3 , 0 , 0
       0      .1       0     480    .045       0     530      .1       0
Bank Sta=480,530
XS Rating Curve= 0 ,0
Exp/Cntr=0.3,0.1

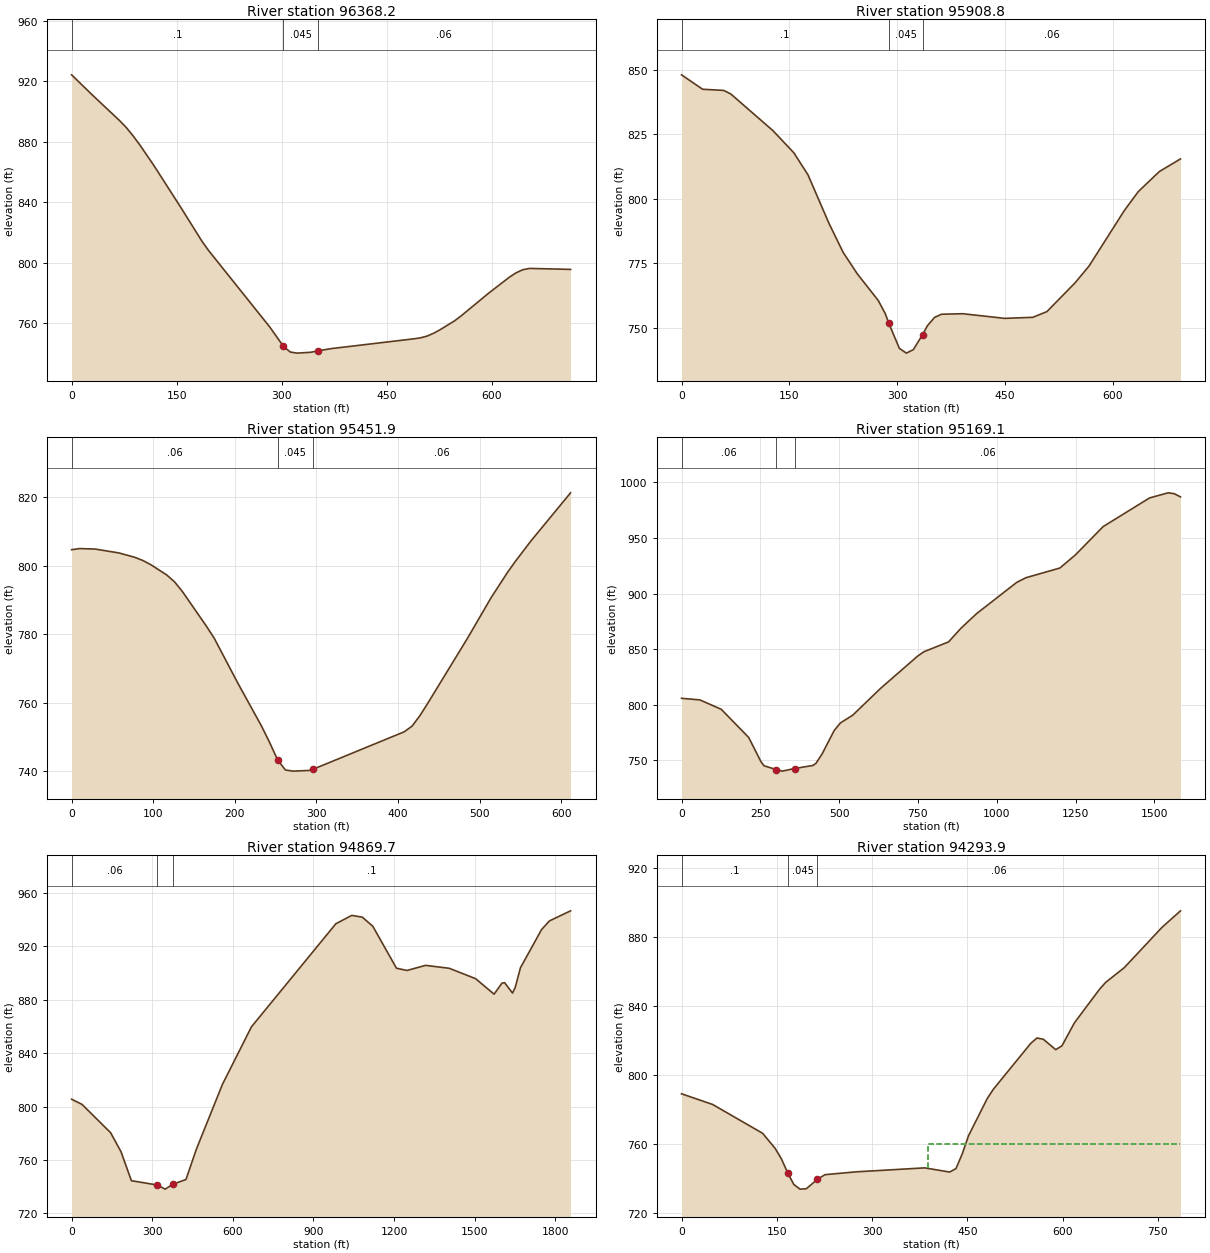
Type RM Length L Ch R = 1 ,96368.2 ,459.8,459.4,458.9
XS GIS Cut Line= 2
     1484043.007      277834.318     1484015.229      278546.124
#Sta/Elev= 30
       0   924.1    29.3  910.91    68.3  893.92    78.1  889.24    87.8  883.74
    97.6  877.63   117.1  864.42   156.1   836.3   185.4   814.6   195.2  808.17
     283  757.34   302.5  744.54   312.3  740.82     322   740.1   341.5  740.66
   351.3  741.57   370.8  743.09   487.9  749.52   497.7  750.16   507.4  751.34
   517.2  753.31   526.9  755.79   546.5  761.36   556.2  764.74   595.2  779.65
   624.5  790.13   634.3  793.12     644  795.21   653.8  796.11   712.4  795.46
#Mann= 3 , 0 , 0
       0      .1       0   302.5    .045       0   351.3     .06       0
Bank Sta=302.5,351.3
XS Rating Curve= 0 ,0
Exp/Cntr=0.3,0.1

Type RM Length L Ch R = 1 ,95908.8 ,456.8,457,457.1
XS GIS Cut Line= 2
     1483577.729      277830.846      1483563.84       278525.29
#Sta/Elev= 30
       0  848.06    29.4  842.47    58.7  842.02    68.5  840.66   127.2  826.45
   156.5   817.8   176.1  809.28   205.4  790.43     225  779.25   244.6  770.98
   273.9  760.59   283.7  755.48  288.28751.9842   303.3  742.02     313   740.2
   322.8  741.57  335.63747.3859   342.4  750.84   352.2  754.03     362  755.27
   391.3  755.48     450  753.67   489.1  754.08   508.7   756.3   547.8  767.42
   567.4  773.98   616.3   795.4   635.9  802.81   665.2  810.58   694.6  815.47
#Mann= 3 , 0 , 0
       0      .1       0  288.28    .045       0  335.63     .06       0
Bank Sta=288.28,335.63
XS Rating Curve= 0 ,0
Exp/Cntr=0.3,0.1

Type RM Length L Ch R = 1 ,95451.9 ,281.8,282.8,283.7
XS GIS Cut Line= 2
     1483122.868      277851.679     1483105.507       278462.79
#Sta/Elev= 30
       0  804.65     9.7  804.99    29.1  804.84    58.2   803.7    77.6  802.43
    87.3  801.51      97   800.3   116.4  797.32   126.2  795.28   135.9  792.42
     165  782.42   174.7  778.87   203.8  765.71   232.9  753.15   242.6  748.48
   252.3  743.44     262  740.42   271.7   740.1   291.1   740.3   295.9740.6464
   407.6  751.57   417.3  753.25     427  756.35   436.7  759.99   485.2  778.88
   514.3  790.77   533.7  797.88   543.4  801.14   562.8   807.2   611.4  821.24
#Mann= 3 , 0 , 0
       0     .06       0   252.3    .045       0   295.9     .06       0
Bank Sta=252.3,295.9
XS Rating Curve= 0 ,0
Exp/Cntr=0.3,0.1

Type RM Length L Ch R = 1 ,95169.1 ,290.2,299.3,308.4
XS GIS Cut Line= 3
      1482855.47      277802.634     1482820.748       278295.69
     1482883.248      279382.495
#Sta/Elev= 30
       0  805.65    58.2  804.25     126  795.79   213.2  770.39     252  748.62
   261.7  744.94   300.4  741.53   319.8   740.1   358.6  742.44   416.7   745.2
   426.4  747.05   445.8  755.49   484.6   776.8   504.1  783.48   543.3   790.5
   631.6  814.63   749.3  843.71   768.9  847.57   847.3  856.48   886.6  868.77
   935.6  881.77  1063.1  909.97  1092.5  914.22  1200.4  922.97  1249.4  934.73
  1337.7  960.28  1484.8  986.05  1543.6  990.66  1563.3  989.87  1582.9  987.02
#Mann= 3 , 0 , 0
       0     .06       0   300.4    .045       0   358.6     .06       0
Bank Sta=300.4,358.6
XS Rating Curve= 0 ,0
Exp/Cntr=0.3,0.1

Type RM Length L Ch R = 1 ,94869.7 ,561,575.9,590
XS GIS Cut Line= 3
     1482702.729      277757.929     1482456.165      278240.134
     1481341.581      278938.051
#Sta/Elev= 30
       0  805.51    38.7  801.64   145.1  780.45   183.8  766.23   222.4  744.54
   319.2  741.28   348.2  738.22   377.2  741.93   425.5  745.41   464.2  768.07
   561.2   816.6   669.2  859.67   983.2  936.79  1042.1  943.03  1081.4  941.74
  1120.6  934.97  1208.9   903.5  1248.2  901.84  1316.9  905.65  1405.2  903.47
  1503.4  895.69    1572  884.11  1601.5  892.39  1611.3   892.7  1640.7  884.91
  1650.6  889.08  1670.2   903.9  1748.7  932.43  1778.1  938.93  1856.6  946.46
#Mann= 3 , 0 , 0
       0     .06       0   319.2    .045       0   377.2      .1       0
Bank Sta=319.2,377.2
XS Rating Curve= 0 ,0
Exp/Cntr=0.3,0.1

Type RM Length L Ch R = 1 ,94293.9 ,482.6,511.7,540.7
XS GIS Cut Line= 2
     1482445.784      277598.207     1481740.923      277945.429
#Sta/Elev= 30
       0  789.01    49.1  782.79   127.7  766.07   147.3  757.39   157.2  751.31
     167  743.27   176.8  736.38   186.6  733.66   196.4  733.86   213.9739.3051
   225.9  742.05     275   743.7     383     746   422.3  743.58   432.2  745.59
     442  754.07   451.8  764.53   481.3  786.15   491.1  791.65     550   818.3
   559.8  821.38   569.7  820.67   589.3  814.62   599.1  816.85   618.8  830.24
   658.1   849.6   667.9  853.67   697.4  862.27   756.3   885.5   785.7   895.2
#Mann= 3 , 0 , 0
       0      .1       0     167    .045       0   213.9     .06       0
#XS Ineff= 2 , 0
                           388.5          759.86
Permanent Ineff=
       F       F
Bank Sta=167,213.9
XS Rating Curve= 0 ,0
Exp/Cntr=0.3,0.1

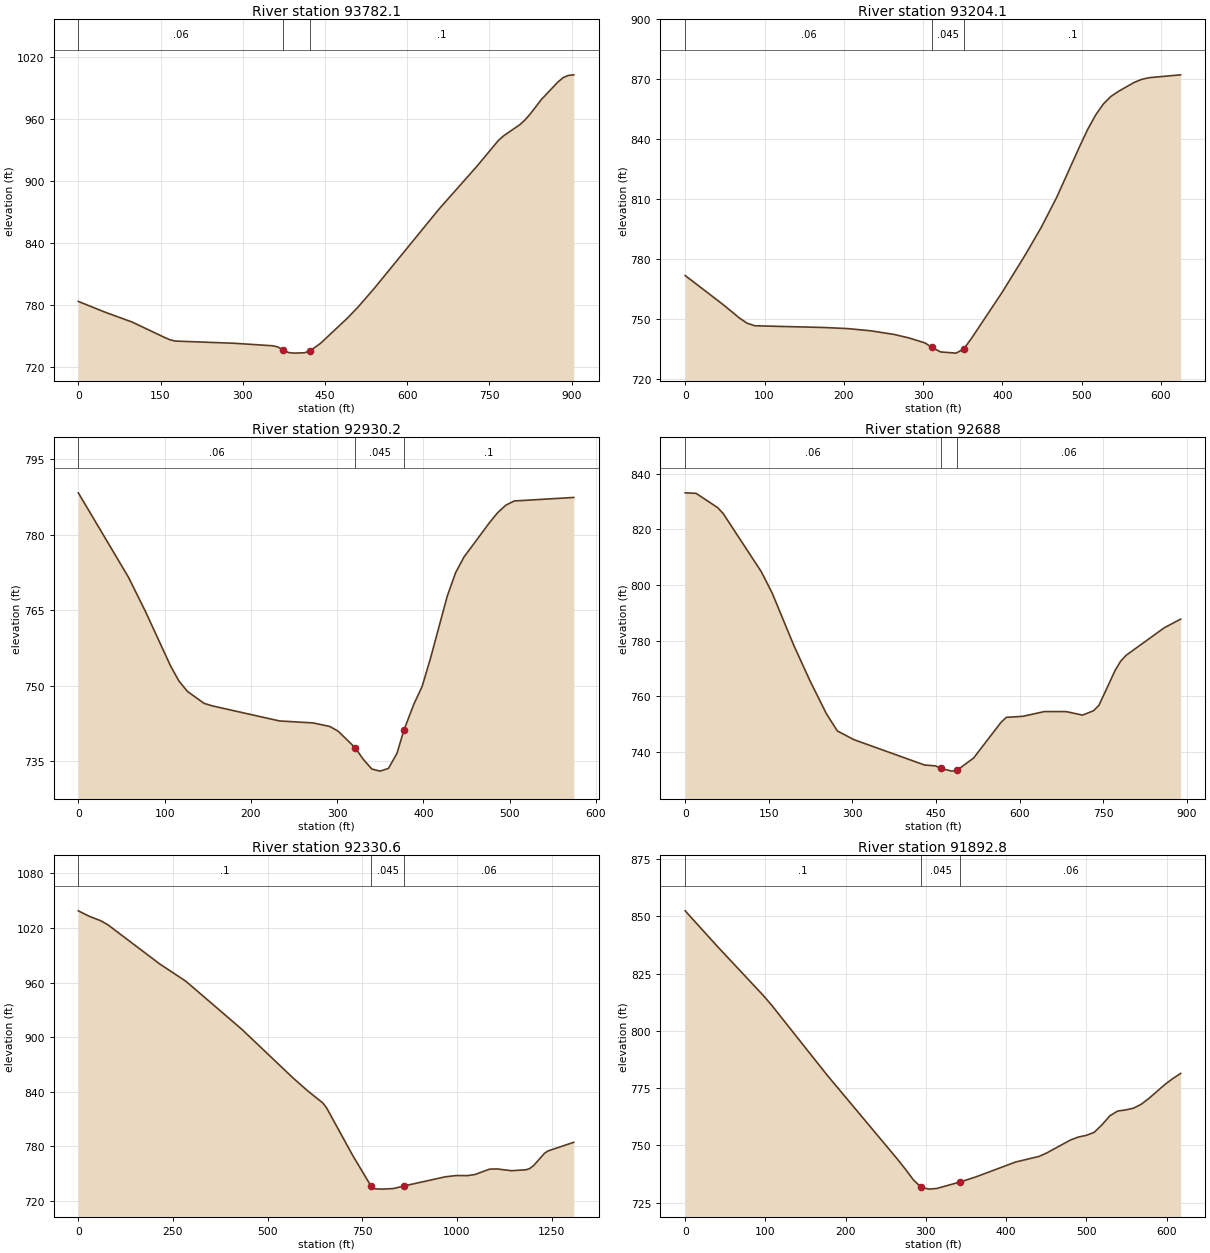
Type RM Length L Ch R = 1 ,93782.1 ,558.7,578,597.4
XS GIS Cut Line= 2
     1482445.784      277553.068     1481824.257      276896.818
#Sta/Elev= 30
       0   783.1    49.1  772.62    98.2  763.11   157.2  748.24     167  745.99
   176.8  744.69   284.9  742.54   353.7  740.15   363.5  739.09   373.3   736.2
   383.2  733.63     393     733   412.6  733.36   422.5  735.06   442.1  742.58
   491.2  767.06   510.9  777.97   540.4  796.05   658.2  872.67     727  913.91
   766.3  939.01   776.1  943.63   805.6   954.4   815.4  959.15   825.3  965.26
   844.9  978.81   874.4  995.35   884.2  999.87     894 1002.08   903.9 1002.66
#Mann= 3 , 0 , 0
       0     .06       0   373.3    .045       0   422.5      .1       0
Bank Sta=373.3,422.5
XS Rating Curve= 0 ,0
Exp/Cntr=0.3,0.1

Type RM Length L Ch R = 1 ,93204.1 ,272.4,273.9,275.3
XS GIS Cut Line= 2
     1482681.895      277487.096     1482744.395      276865.568
#Sta/Elev= 30
       0  771.83    48.8  756.99    68.3  750.59    78.1  747.97    87.8  746.69
   175.7  745.82     205  745.27   234.2  744.16   263.5  742.35     283  740.51
   302.6  738.07   310.8735.8974   322.1   733.6   341.6     733   351.4  735.16
   361.1  740.46   400.2  763.77   429.5  782.64     449  795.99   468.5  811.03
   497.8  836.81   507.5  844.95   517.3  852.02   527.1  857.61   536.8  861.48
   546.6  864.06   566.1  868.47   575.9  870.04   585.6  870.87   624.7  872.27
#Mann= 3 , 0 , 0
       0     .06       0   310.8    .045       0   351.4      .1       0
Bank Sta=310.8,351.4
XS Rating Curve= 0 ,0
Exp/Cntr=0.3,0.1

Type RM Length L Ch R = 1 ,92930.2 ,243.5,242.1,240.7
XS GIS Cut Line= 3
     1482929.291      277535.707     1483011.924      277037.065
     1483026.513      276969.735
#Sta/Elev= 30
       0  788.36    58.3  771.52    77.8  764.77   106.9  753.94   116.6  750.94
   126.4  748.87   145.8  746.48   155.5  745.97   233.3  742.98   272.2  742.59
   291.6  741.88   301.3  740.93   320.8  737.67   330.5  735.31   340.2  733.42
   349.9     733   359.6  733.55   369.4  736.54   377.4 741.142   388.8  746.26
   398.5  749.83   408.2  755.42   427.7  767.83   437.4  772.49   447.1   775.6
   476.3  782.35     486   784.4   495.7  785.92   505.4  786.74   574.3  787.44
#Mann= 3 , 0 , 0
       0     .06       0   320.8    .045       0   377.4      .1       0
Bank Sta=320.8,377.4
XS Rating Curve= 0 ,0
Exp/Cntr=0.3,0.1

Type RM Length L Ch R = 1 ,92688   ,389.8,357.4,325.1
XS GIS Cut Line= 4
     1483336.807      277665.915     1483205.792      277426.393
     1483241.091      277076.128     1483059.066      276885.099
#Sta/Elev= 30
       0   833.1    19.5  832.92    58.5  827.74    68.2  825.64   136.5  804.75
     156  797.08     195  778.19   224.3  765.35   253.5  753.62     273  747.49
   302.4  744.38   429.5  735.23     449  734.93   458.8  734.02   478.4  733.04
   488.2  733.42   517.5  737.76   566.4  750.53   576.2  752.38   605.5  752.74
   644.6  754.46   683.7  754.44     713  753.18   732.6  754.75   742.3   756.7
   771.6  769.35   781.4   772.6   791.2   774.7   859.6  784.59   888.9  787.69
#Mann= 3 , 0 , 0
       0     .06       0   458.8    .045       0   488.2     .06       0
Bank Sta=458.8,488.2
XS Rating Curve= 0 ,0
Exp/Cntr=0.3,0.1

Type RM Length L Ch R = 1 ,92330.6 ,448.3,437.8,427.2
XS GIS Cut Line= 3
     1484299.915      277316.523      1483292.97      277066.523
     1483084.673      276893.346
#Sta/Elev= 30
       0 1038.93    29.4 1032.82    58.7 1028.12    78.3 1023.51   215.3  980.41
   283.8  961.58   430.7  909.08   567.7   854.9   606.8  840.59     646  827.58
   655.8  822.18   724.3  770.18   773.2  736.21     783  733.22   802.6   732.9
     832  733.54   861.3   736.5     969  746.44   998.4  747.85  1027.7  747.75
  1047.2  748.94  1085.9  754.84  1105.2  755.14  1143.9  753.15  1182.6  754.17
  1192.3   755.6    1202  758.61    1231  772.22  1240.7  774.93  1308.4   784.4
#Mann= 3 , 0 , 0
       0      .1       0   773.2    .045       0   861.3     .06       0
Bank Sta=773.2,861.3
XS Rating Curve= 0 ,0
Exp/Cntr=0.3,0.1

Type RM Length L Ch R = 1 ,91892.8 ,507.8,505.9,503.9
XS GIS Cut Line= 2
     1483709.673      276646.818     1483108.979      276789.179
#Sta/Elev= 30
       0  852.46    39.2  837.26      98  815.21   107.8   811.2   176.4  780.86
   264.6  743.88   274.4  739.56   284.2  734.95     294  731.62   303.8  730.85
   313.6  731.16     343  734.02   362.6  736.24   411.6  742.69     441  745.16
   450.8  746.72   480.2  752.34     490  753.63   499.8  754.34   509.6  755.66
   519.3  758.95   529.1  762.89   538.9  764.97   548.7  765.46   558.5  766.21
   568.3  767.96   578.1  770.59   597.7  776.58   607.5  779.15   617.3  781.42
#Mann= 3 , 0 , 0
       0      .1       0     294    .045       0     343     .06       0
Bank Sta=294,343
XS Rating Curve= 0 ,0
Exp/Cntr=0.3,0.1

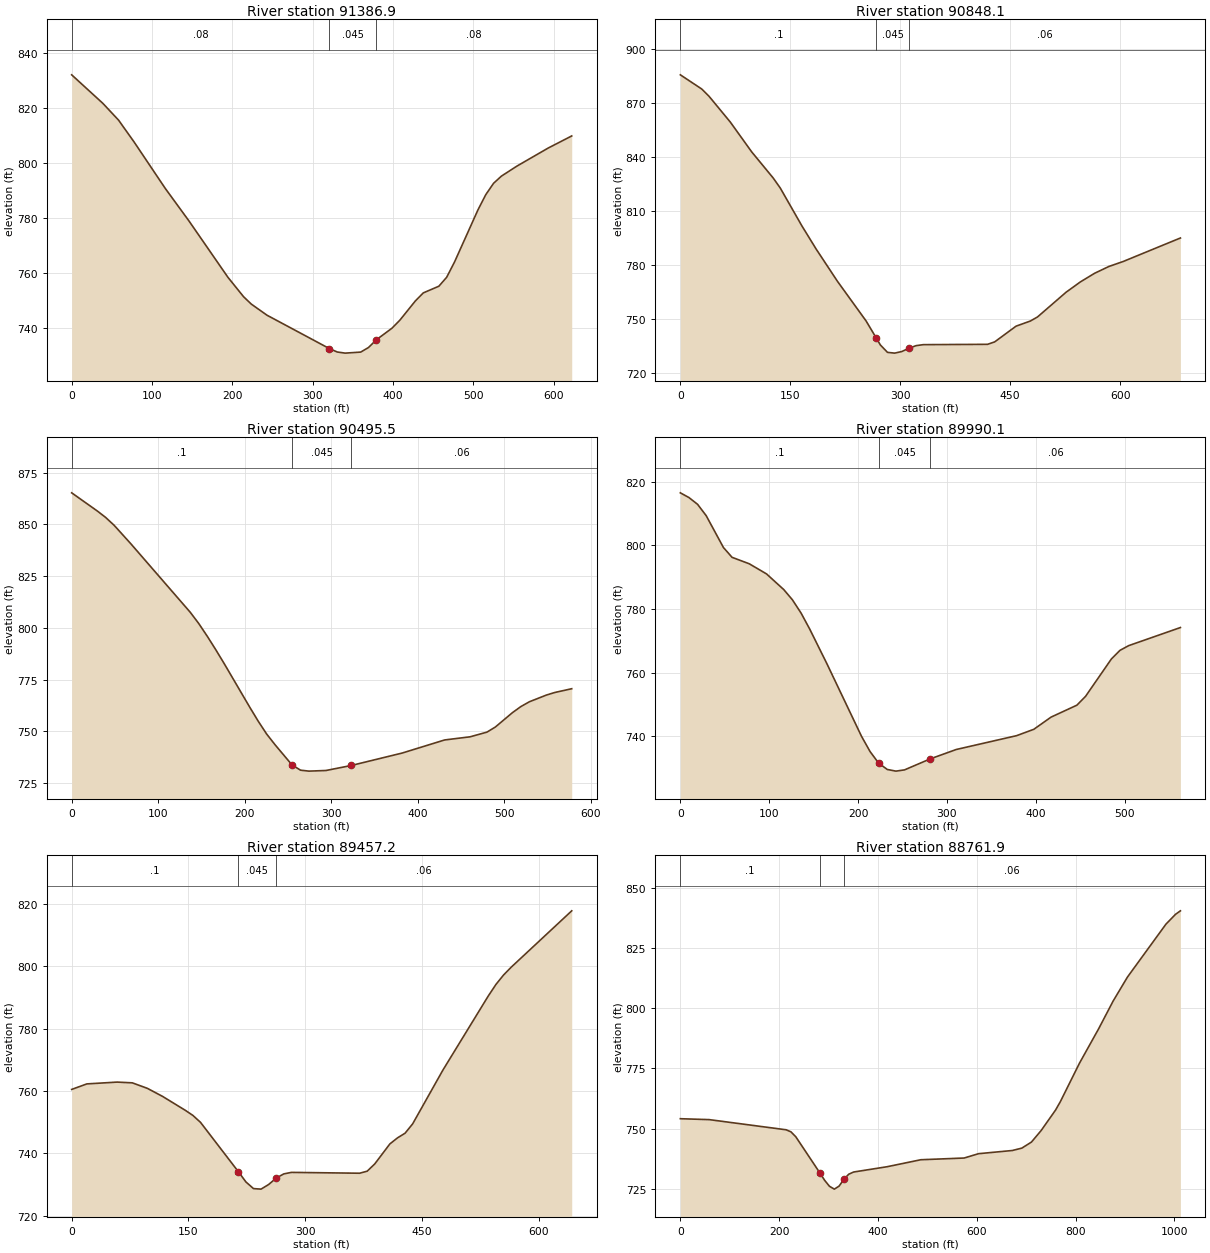
Type RM Length L Ch R = 1 ,91386.9 ,551.8,538.8,525.7
XS GIS Cut Line= 2
     1483567.312      276139.874     1482977.034       276337.79
#Sta/Elev= 30
       0  832.07    38.9  821.67    58.4  815.58    77.8   807.6   116.7  790.67
   145.9  778.96   194.6  758.38     214  751.34   223.7  748.63   243.2   744.6
     321  732.43   330.7  731.21   340.5   730.8   359.9  731.18   369.6  732.85
   379.4  735.66   398.8  739.87   408.6  742.78     428  749.82   437.8  752.72
   457.2  755.15   466.9   758.4   476.7  763.97   505.8  782.89   515.6  788.47
   525.3   792.6     535   795.2   554.5  798.88   593.4  805.44   622.6  809.83
#Mann= 3 , 0 , 0
       0     .08       0     321    .045       0   379.4     .08       0
Bank Sta=321,379.4
XS Rating Curve= 0 ,0
Exp/Cntr=0.3,0.1

Type RM Length L Ch R = 1 ,90848.1 ,354.7,352.6,350.2
XS GIS Cut Line= 2
     1483168.007       275556.54     1482744.395      276091.262
#Sta/Elev= 30
       0  885.81    29.2   877.9      39  873.93    68.2  859.48    97.4  842.87
   126.7  828.34   136.4  822.72   165.7  801.78   185.2  788.84   214.4   770.8
   253.4  748.76   267.4739.1627   272.9  735.38   282.6  731.28   292.4  730.85
   302.1  731.74   311.9  733.58   321.6  735.01   331.4  735.57   419.1  735.75
   428.8   737.1     458  745.87   477.5  748.72   487.3  751.01   526.3  764.78
   545.8  770.52   565.2  775.32   584.7  779.11   604.2  781.88   682.2  794.96
#Mann= 3 , 0 , 0
       0      .1       0   267.4    .045       0   311.9     .06       0
Bank Sta=267.4,311.9
XS Rating Curve= 0 ,0
Exp/Cntr=0.3,0.1

Type RM Length L Ch R = 1 ,90495.5 ,517.6,505.4,493.2
XS GIS Cut Line= 2
     1482834.673      275372.512     1482522.173      275858.624
#Sta/Elev= 30
       0  865.29    29.4  856.58    39.2  853.42      49  849.64    68.6  840.57
   137.1  807.54   146.9  802.11   156.7  795.99   166.5   789.5   176.3  782.75
   205.7  761.76   215.5     755   225.3  748.75   235.1  743.52   254.7  733.78
   264.5  731.26   274.2   730.8   293.8   731.1   323.2  733.53     382  739.54
     431  745.86   460.4  747.38   479.9  749.64   489.7  752.13   509.3  759.03
   519.1  761.99   528.9  764.31   548.5  767.54   558.3   768.8   577.9  770.62
#Mann= 3 , 0 , 0
       0      .1       0   254.7    .045       0   323.2     .06       0
Bank Sta=254.7,323.2
XS Rating Curve= 0 ,0
Exp/Cntr=0.3,0.1

Type RM Length L Ch R = 1 ,89990.1 ,532.5,532.9,532.8
XS GIS Cut Line= 2
     1482216.618      275226.679     1482199.257      275789.179
#Sta/Elev= 30
       0  816.54     9.7  815.05    19.4  812.92    29.1  809.35    48.5  799.34
    58.2  796.26    77.6  794.22      97  791.04   116.4  786.11   126.1  782.91
   135.8  778.76   145.5  773.75     165  762.77   203.8  740.03   213.5  735.19
   223.2  731.54   232.9  729.55   242.6  729.03   252.3  729.42   281.4   732.9
   310.5  735.83   378.4  740.18   397.8  742.18   417.2  746.01   446.3  749.77
     456  752.53   485.1  764.29   494.8  767.01   504.6  768.49   562.8  774.18
#Mann= 3 , 0 , 0
       0      .1       0   223.2    .045       0   281.4     .06       0
Bank Sta=223.2,281.4
XS Rating Curve= 0 ,0
Exp/Cntr=0.3,0.1

Type RM Length L Ch R = 1 ,89457.2 ,689.3,695.3,699.9
XS GIS Cut Line= 2
      1481688.84      275230.151       1481664.1      275872.078
#Sta/Elev= 30
       0  760.52    19.5  762.29    58.4  762.87    77.9  762.63    97.3  760.86
   116.8  758.28     146  753.82   155.7  752.19   165.5  749.97   214.1  734.16
   223.9  730.84   233.6  728.72   243.3  728.55   253.1  730.04   262.8   732.1
   272.5  733.43   282.3  733.92   369.9  733.65   379.6   734.3   389.3  736.61
   408.8  743.05   418.5  744.97   428.3  746.48     438  749.46   476.9  766.72
   535.3  790.52   545.1   794.2   554.8   797.2   564.5  799.68   642.4  817.79
#Mann= 3 , 0 , 0
       0      .1       0   214.1    .045       0   262.8     .06       0
Bank Sta=214.1,262.8
XS Rating Curve= 0 ,0
Exp/Cntr=0.3,0.1

Type RM Length L Ch R = 1 ,88761.9 ,306.7,308.2,309.8
XS GIS Cut Line= 3
     1481251.304      275028.328     1481088.109      275649.856
     1480848.526      275931.106
#Sta/Elev= 30
       0   754.1    58.4  753.72   214.2  749.49   223.9  748.63   233.7  746.58
   282.4  731.54   292.1  728.45   301.8  725.99   311.6   724.8   321.3  726.06
     331  728.89   340.8     731   350.5  731.91   418.7  734.13   486.8  737.03
   574.4  737.74   603.6  739.55   671.8  740.87   691.2  741.87   710.6  744.38
   730.1  749.15   759.3  757.67     769  761.16   807.9  777.24   846.8   791.6
   875.9  803.05   905.1   813.1   982.9  835.08  1002.3  839.17  1012.1  840.61
#Mann= 3 , 0 , 0
       0      .1       0   282.4    .045       0     331     .06       0
Bank Sta=282.4,331
XS Rating Curve= 0 ,0
Exp/Cntr=0.3,0.1

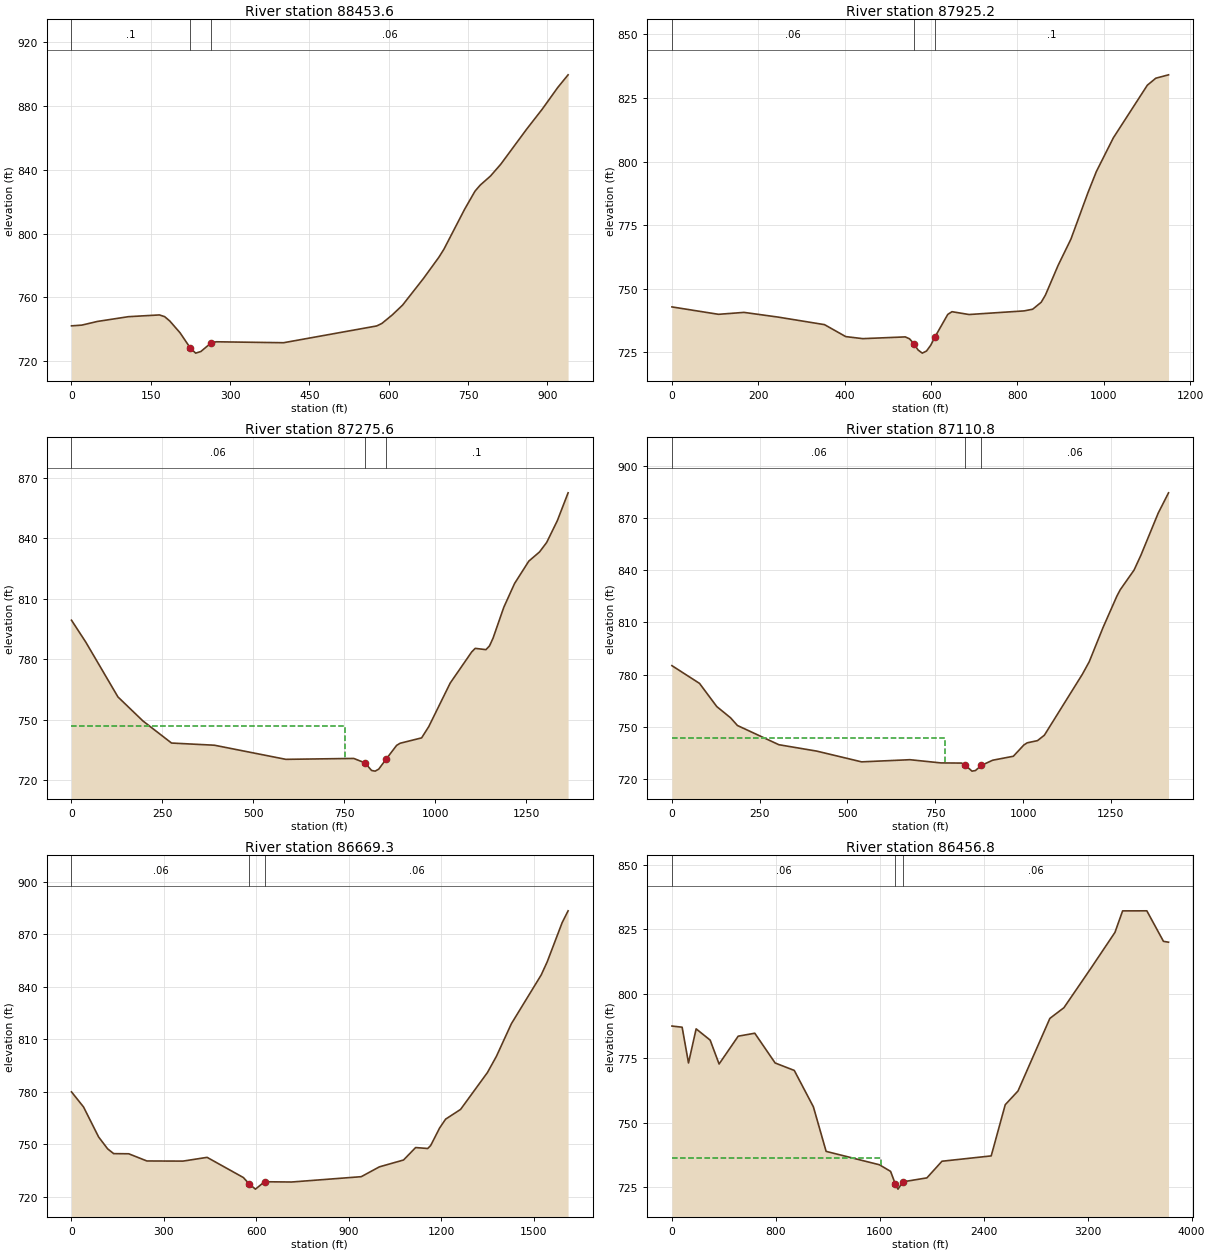
Type RM Length L Ch R = 1 ,88453.6 ,511.6,528.5,545.4
XS GIS Cut Line= 2
     1480983.979      274973.207     1480679.725      275861.662
#Sta/Elev= 30
       0  742.08    19.6  742.54    48.9  744.84   107.6  747.83   166.3  748.93
   176.1  747.86   185.9  745.12   205.4  737.67     225  728.03   234.8  724.96
   244.6  725.97   264.1  731.38   273.9  732.08   401.1  731.49   577.2  742.02
   586.9  743.58   606.5   748.9   626.1   755.1   665.2  771.64   694.6  785.06
   704.3  790.19   743.5   815.3     763  826.57   772.8  830.37   792.4  836.12
   811.9  843.56   860.8  865.55   890.2  878.07   919.5  891.65   939.1  899.62
#Mann= 3 , 0 , 0
       0      .1       0     225    .045       0   264.1     .06       0
Bank Sta=225,264.1
XS Rating Curve= 0 ,0
Exp/Cntr=0.3,0.1

Type RM Length L Ch R = 1 ,87925.2 ,650.6,649.5,647.2
XS GIS Cut Line= 4
     1480935.368      274907.235     1480643.701      274945.429
     1480303.423      275143.346     1480293.007      275605.151
#Sta/Elev= 30
       0   742.9   107.9  739.99   166.7  740.75   245.1  738.92   353.2  735.94
   402.4  731.24   441.8  730.44   540.2  731.12     550  730.38   559.9   728.5
   569.7     726   579.6  724.75   589.4  725.58   599.2  727.86   609.1  731.16
   638.6  739.96   648.4  741.02   687.8  739.91   815.6  741.34   835.2     742
   854.9  744.73   864.7  747.56   894.2  759.27   923.7  769.52     963  787.71
   982.6  796.06    1022  809.33  1100.6  829.97  1120.2  832.72  1149.7  834.05
#Mann= 3 , 0 , 0
       0     .06       0   559.9    .045       0   609.1      .1       0
Bank Sta=559.9,609.1
XS Rating Curve= 0 ,0
Exp/Cntr=0.3,0.1

Type RM Length L Ch R = 1 ,87275.6 ,165,164.9,164.4
XS GIS Cut Line= 2
     1480886.757      274136.401     1479723.562      274851.679
#Sta/Elev= 30
       0  799.35    39.3  788.48   127.7  761.27   196.5  749.33   275.1  738.37
     393  737.29   589.4  730.28   776.1  730.73   806.8728.5421   825.2  724.75
     835  724.43   844.8  725.42   864.5  730.22     894  737.21   903.8  738.28
   962.7  740.93   982.4  746.54  1041.3  768.13  1100.3  783.57  1110.1  785.37
  1139.6  784.74  1149.4  786.59  1159.2  790.46  1188.7  805.76  1218.2  817.54
  1257.5  828.69  1286.9  833.23  1306.6  837.95    1336   848.8  1365.5  862.59
#Mann= 3 , 0 , 0
       0     .06       0   806.8    .045       0   864.5      .1       0
#XS Ineff= 2 , 0
          751.75  747.05
Permanent Ineff=
       F       F
Bank Sta=806.8,864.5
XS Rating Curve= 0 ,0
Exp/Cntr=0.3,0.1

Type RM Length L Ch R = 1 ,87110.8 ,436.3,441.5,440.1
XS GIS Cut Line= 2
     1480852.034      273966.262     1479650.645       274712.79
#Sta/Elev= 30
       0  785.12    78.6   774.9   127.7  761.55     167  755.07   186.6  750.64
   304.5  739.57   412.5  735.88   540.2  729.69   677.8  730.93   766.2  729.08
   825.1  728.99   834.9  727.87   854.6  724.35   864.4  724.67   881.1727.6303
   913.5  730.63   972.4  732.92  1001.9  739.33  1011.7  740.65  1041.2  741.93
  1060.8  745.06  1168.9  780.15  1188.5  787.38  1227.8  807.08  1267.1  825.12
  1276.9  828.89  1316.2   840.2  1335.9  848.85    1385  873.03  1414.4  884.71
#Mann= 3 , 0 , 0
       0     .06       0   834.9    .045       0   881.1     .06       0
#XS Ineff= 2 , 0
             777  743.57
Permanent Ineff=
       F       F
Bank Sta=834.9,881.1
XS Rating Curve= 0 ,0
Exp/Cntr=0.3,0.1

Type RM Length L Ch R = 1 ,86669.3 ,207.7,212.5,217.6
XS GIS Cut Line= 4
     1480827.729      273948.901     1480390.229      273997.512
     1479706.201      274209.318     1479591.618       274650.29
#Sta/Elev= 30
       0  779.88    39.1  771.25      88  754.12   117.4  747.31     137  744.59
   185.9   744.5   244.6   740.4   361.9  740.32   440.2  742.46   557.9  730.93
   577.5  727.14   597.1  724.31   626.6  728.52   714.8  728.38   940.5  731.42
   999.3  737.03  1077.8  740.95    1117  748.06  1156.3  747.52    1166  749.27
    1195  759.28  1214.4   764.3  1262.9  769.85  1350.1  790.92  1379.2  800.17
  1427.7  818.78  1524.6  846.67    1544  854.13  1592.5  876.51  1611.9  883.31
#Mann= 3 , 0 , 0
       0     .06       0   577.5    .045       0   626.6     .06       0
Bank Sta=577.5,626.6
XS Rating Curve= 0 ,0
Exp/Cntr=0.3,0.1

Type RM Length L Ch R = 1 ,86456.8 ,218.1,216.8,215.4
XS GIS Cut Line= 6
     1481845.524      274116.002     1480762.305      273882.047
     1480322.086      273849.509     1479852.034      273935.012
      1479657.59      274039.179     1478963.109      275448.467
#Sta/Elev= 30
       0  787.51    78.5  787.06   127.5   773.2   186.3  786.42   294.2  782.06
   362.9   772.8     510  783.58   637.5  784.73   794.4  773.19   941.5  770.31
  1088.6  756.21  1186.7  738.93  1597.2  733.74  1682.8  731.18    1720726.2158
  1739.8   724.3  1777.9  727.13  1962.2  728.66  2078.3  735.11  2457.2  737.18
  2565.2  757.02  2663.4  762.34  2908.8  790.48  3016.9  794.62  3223.1   809.8
  3409.6  823.81  3468.6  832.15  3655.1  832.17  3782.8  820.35    3822  820.01
#Mann= 3 , 0 , 0
       0     .06       0    1720    .045       0  1777.9     .06       0
#XS Ineff= 2 , 0
         1607.05  736.47
Permanent Ineff=
       F       F
Bank Sta=1720,1777.9
XS Rating Curve= 0 ,0
Exp/Cntr=0.3,0.1

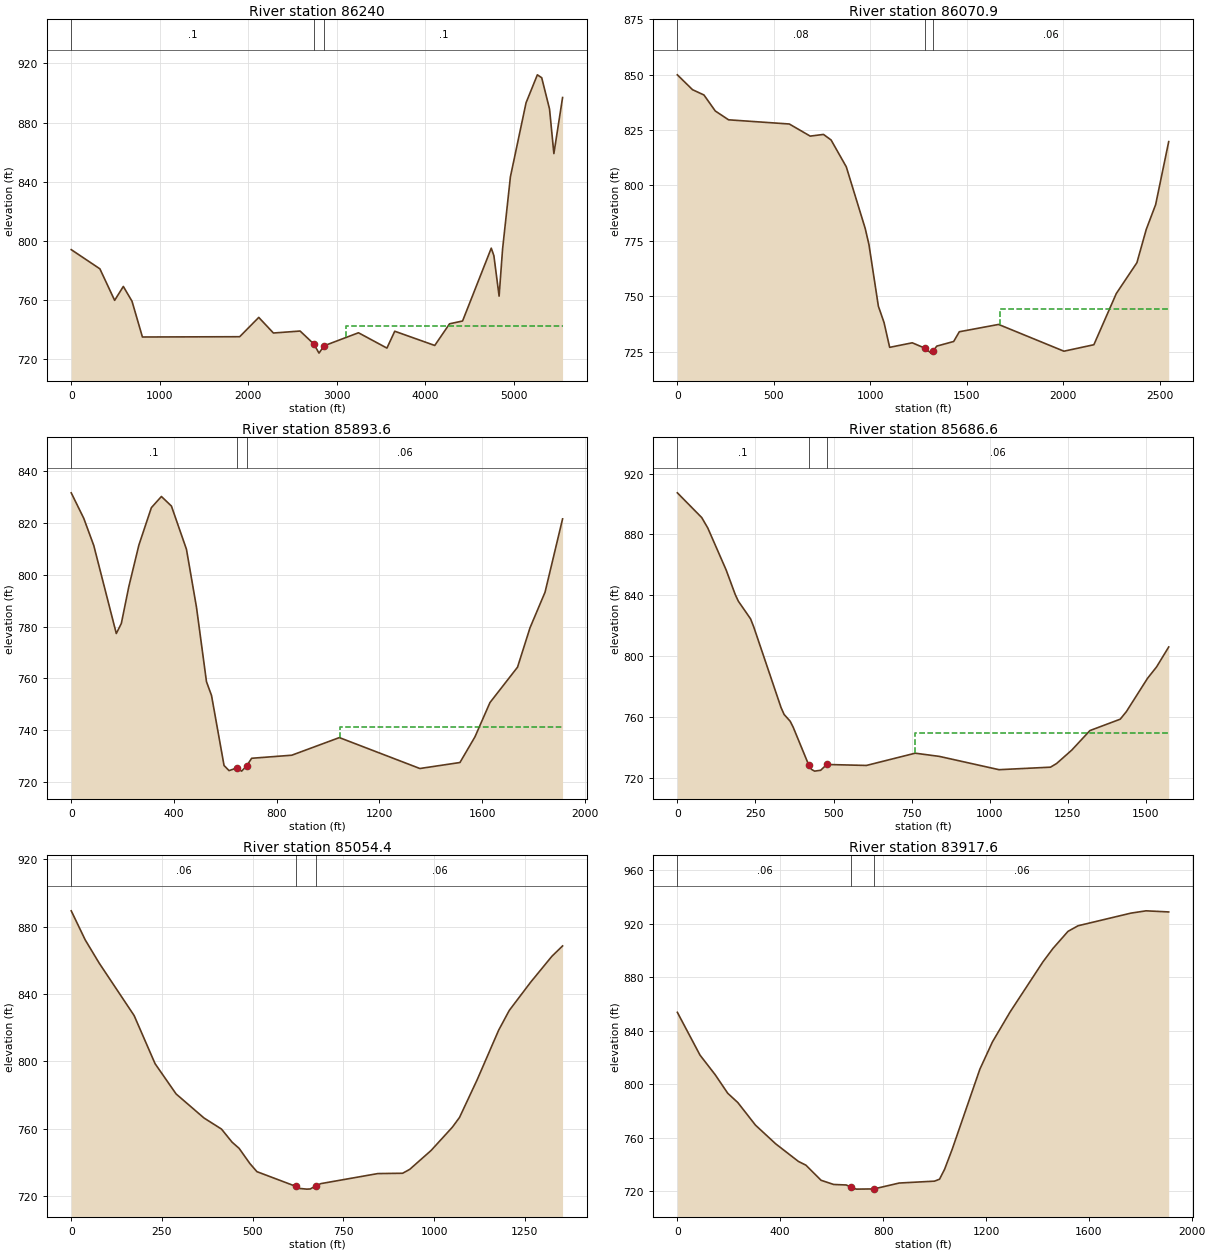
Type RM Length L Ch R = 1 ,86240   ,177.2,169.2,161.2
XS GIS Cut Line= 6
     1482882.156      273983.537     1480799.257      273659.318
     1480274.951      273628.068     1479986.757      273666.262
     1479514.534      273867.651      1478017.97      275356.801
#Sta/Elev= 30
       0  794.18   323.6  781.22   490.2  759.94   588.3  769.33   686.3  759.34
     804  735.19  1902.1  735.38  2117.7  748.42  2283.1  737.88  2584.6  739.22
  2739.8  730.45    2798   724.3  2856.1  729.27  3243.6  738.05    3565   727.7
  3653.3  739.08    4105  729.48    4272  744.09  4419.3     746  4743.3  795.18
  4772.8   790.1  4831.7  762.78    4871  794.59  4959.4  843.37  5136.1  893.35
  5263.8  912.22  5312.9  910.26  5401.2  889.16  5450.3  859.04  5548.5  896.88
#Mann= 3 , 0 , 0
       0      .1       0  2739.8    .045       0  2856.1      .1       0
#XS Ineff= 2 , 0
                         3103.19          742.77
Permanent Ineff=
       F       F
Bank Sta=2739.8,2856.1
XS Rating Curve= 0 ,0
Exp/Cntr=0.3,0.1

Type RM Length L Ch R = 1 ,86070.9 ,185.5,177.2,169
XS GIS Cut Line= 6
     1480872.651      272594.952     1480699.945      273148.784
     1480387.445      273315.451     1479878.764      273584.548
     1479506.765      273747.295     1478885.237      273851.462
#Sta/Elev= 30
       0  849.94    78.7  843.22   137.7  840.85   196.7   833.6   265.5  829.63
   580.1  827.74   688.4  822.27   757.2  823.04   796.6  820.52   875.3  808.41
   973.3   780.6   992.8   773.3  1041.6  745.48  1070.9  738.13  1100.1  726.91
  1217.2  728.96  1284.5 726.473  1314.7   724.3  1324.4  725.05    1344  727.46
  1431.8  729.56    1461  733.95  1664.5  737.25  2003.1  725.17  2158.2  728.09
  2274.5  751.21  2381.2  765.12  2429.7  780.17  2478.2  791.32    2546  819.79
#Mann= 3 , 0 , 0
       0     .08       0  1284.5    .045       0  1324.4     .06       0
#XS Ineff= 2 , 0
                         1672.48             744
Permanent Ineff=
       F       F
Bank Sta=1284.5,1324.4
XS Rating Curve= 0 ,0
Exp/Cntr=0.3,0.1

Type RM Length L Ch R = 1 ,85893.6 ,215.5,207.1,198.6
XS GIS Cut Line= 5
     1480372.868      272827.374     1480088.145      273198.901
     1479695.784      273646.818      1479501.34      273740.568
      1478876.34      273844.735
#Sta/Elev= 30
       0  831.53    48.8   821.7    87.8  811.22   175.5  777.32     195  781.18
   224.3  795.42   263.3  811.37     312  825.81   351.1  830.12   390.1  826.43
   448.6  809.78   487.6  787.49   526.6  758.75   546.2  753.45     595  726.46
   614.5  724.49   643.8  725.49   663.3   724.3   682.8  726.28   702.4  729.25
   858.6  730.43    1044  737.22  1357.4  725.31  1513.4  727.62  1571.8   737.5
  1630.3  750.72  1737.6  764.35  1786.3  779.55  1844.8  793.26    1913  821.48
#Mann= 3 , 0 , 0
       0      .1       0   643.8    .045       0   682.8     .06       0
#XS Ineff= 2 , 0
                         1047.23          741.43
Permanent Ineff=
       F       F
Bank Sta=643.8,682.8
XS Rating Curve= 0 ,0
Exp/Cntr=0.3,0.1

Type RM Length L Ch R = 1 ,85686.6 ,623,632.2,641.1
XS GIS Cut Line= 4
     1479911.062      272875.985     1479640.229      273629.457
     1479490.923       273712.79     1478897.173      273810.012
#Sta/Elev= 30
       0   907.4    78.1   891.1    97.6  884.19   156.2  856.66   185.5  840.39
   195.3   836.1   234.3  824.52   244.1  819.47     332  766.13   341.8   761.6
   361.3   757.1     371  753.14   420.4 728.465   429.6  725.43   439.4   724.3
   458.9  724.86   478.4  728.67   605.4  728.04   761.6   736.1   838.7     734
  1029.9  725.25  1194.8   726.9  1214.3   729.3  1262.8  738.12    1321  750.98
    1418  758.47  1437.5  763.38  1505.4  785.34  1534.5  792.88  1573.3  805.98
#Mann= 3 , 0 , 0
       0      .1       0   420.4    .045       0   478.4     .06       0
#XS Ineff= 2 , 0
                          762.22           749.4
Permanent Ineff=
       F       F
Bank Sta=420.4,478.4
XS Rating Curve= 0 ,0
Exp/Cntr=0.3,0.1

Type RM Length L Ch R = 1 ,85054.4 ,1116,1136.8,1156.5
XS GIS Cut Line= 3
     1479668.007      272691.957     1479324.257      272955.846
     1478705.767      273637.703
#Sta/Elev= 30
       0  889.31    38.5   872.1      77  858.32   173.3  827.23   231.1  798.66
   288.9  780.75     366  766.45   414.1   759.9   443.2  752.15   462.7  748.46
   492.1  739.52   511.7  734.65   619.4   725.9   629.2  724.71   648.8   724.3
   658.6  724.39   675.6726.4088     688  727.57   844.7  733.52   913.2  733.71
   932.8  736.03   991.6  747.22  1050.3  761.05  1069.9   766.8  1118.9  789.32
  1177.7  818.51    1207  830.25  1265.8  846.96  1324.6  862.39  1353.9   868.5
#Mann= 3 , 0 , 0
       0     .06       0   619.4    .045       0   675.6     .06       0
Bank Sta=619.4,675.6
XS Rating Curve= 0 ,0
Exp/Cntr=0.3,0.1

Type RM Length L Ch R = 1 ,83917.6 ,757.5,755.9,753.7
XS GIS Cut Line= 3
     1479508.284      272423.728     1478175.819      272384.665
     1477750.472       272775.29
#Sta/Elev= 30
       0  853.91    88.2  821.88     147  807.28     196  793.36   235.2  786.42
   303.8  769.54   382.3  755.58   470.5  742.44   499.9   739.6   558.7  728.32
   607.7  725.18   656.7   724.8   676.3  723.08   695.9   721.7   764.5  721.86
   862.6  726.26   999.8  727.66  1019.4  729.13    1039  736.52  1068.4  751.39
  1176.2  811.36  1225.2  831.82  1293.8  854.18  1421.1  891.55  1460.3  901.64
    1519  914.47  1558.2  918.65  1763.7  928.09  1822.4  929.81  1910.5  928.98
#Mann= 3 , 0 , 0
       0     .06       0   676.3    .045       0   764.5     .06       0
Bank Sta=676.3,764.5
XS Rating Curve= 0 ,0
Exp/Cntr=0.3,0.1