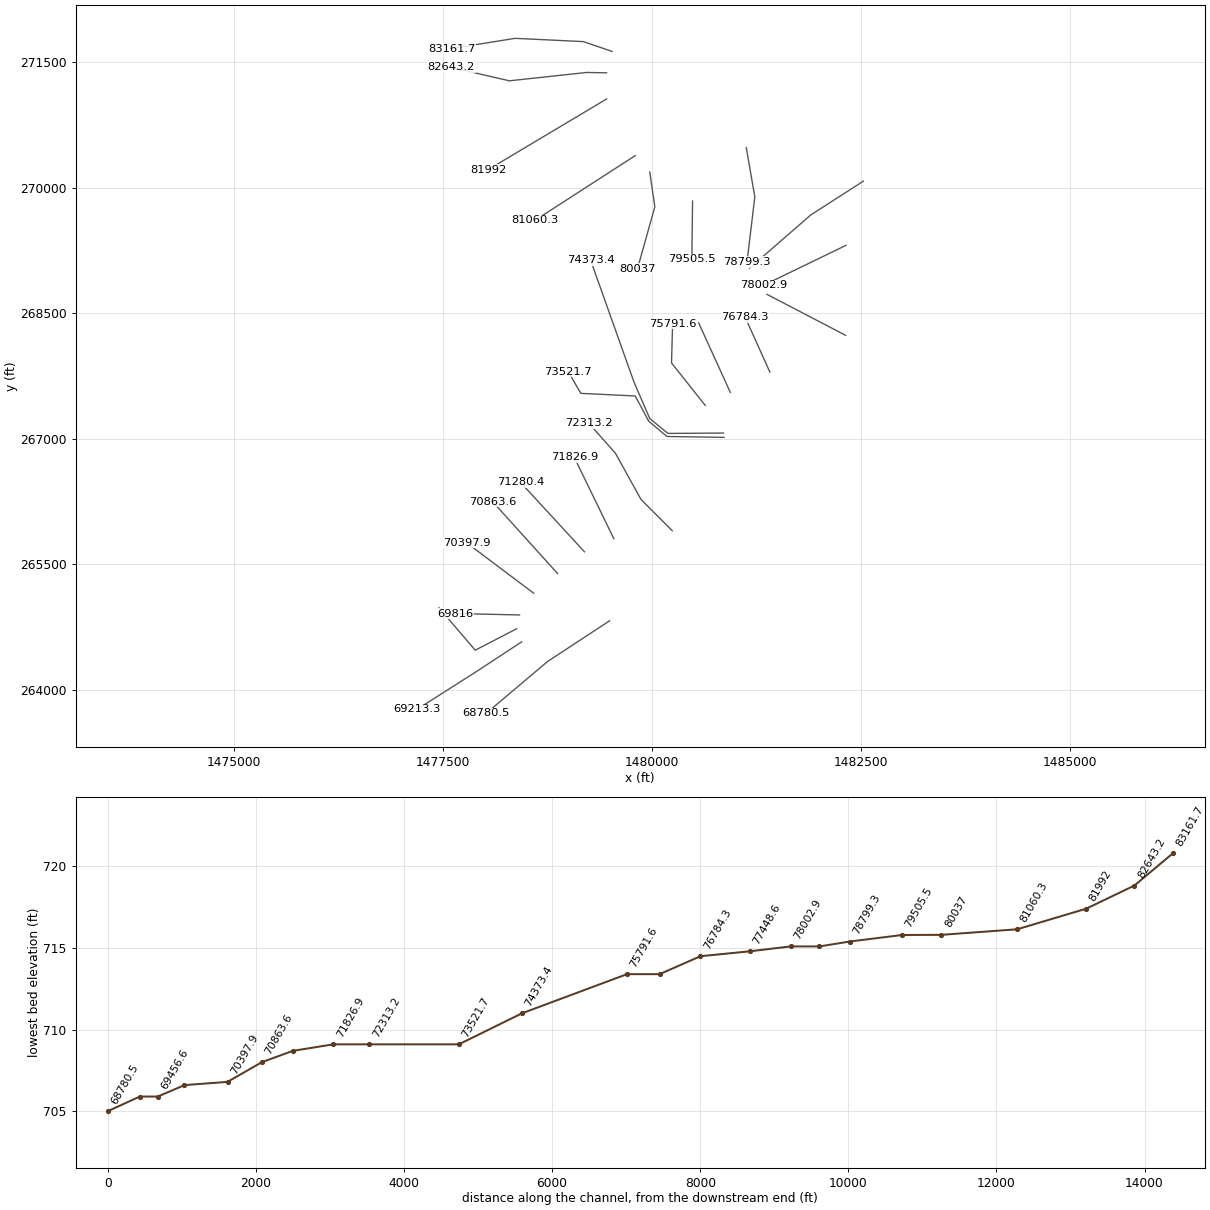
HEC-RAS study GSCR.prj: GSCR

--- GSCR.g01 (geometry) --- (continued)

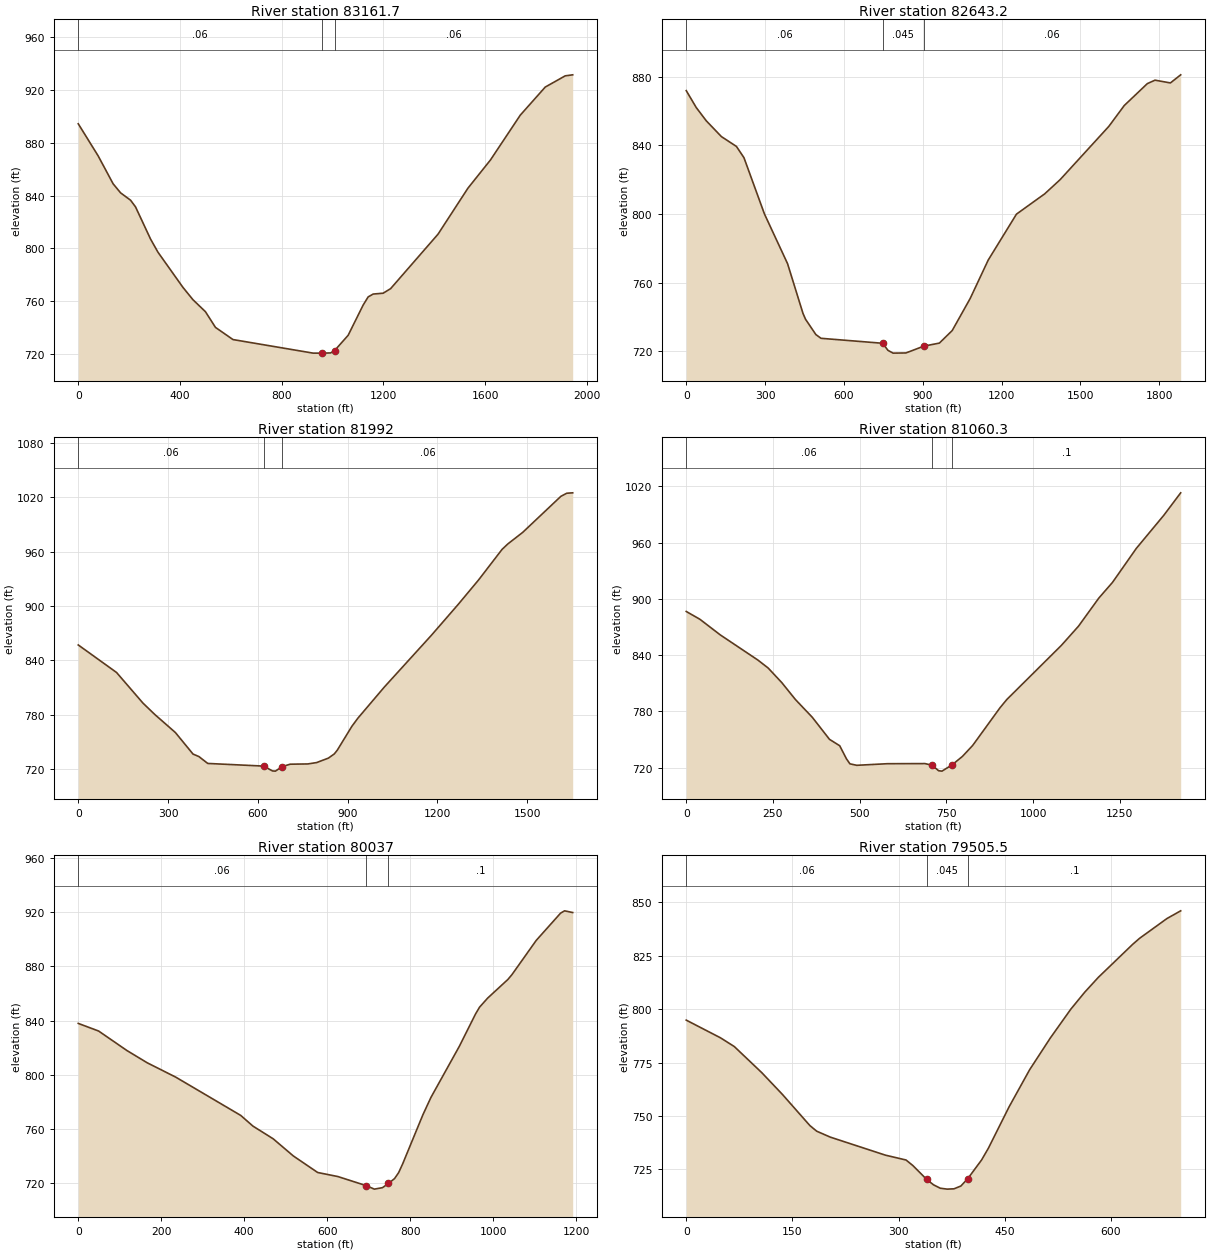
Type RM Length L Ch R = 1 ,83161.7 ,518,518.5,519.1
XS GIS Cut Line= 4
     1479521.739      271631.193     1479178.857      271748.381
     1478362.885      271787.443     1477607.677      271665.915
#Sta/Elev= 30
       0  894.38    78.4  870.04   137.1  848.96   166.5   842.1   205.7  836.54
   225.2  831.49     284  807.24   313.4  797.19   411.6  770.57   450.9  761.24
   500.2  752.14   539.5  740.28   608.4  731.06   923.4   720.8   958.2   720.8
   992.3  720.95  1008.2722.7781  1061.2  734.28  1120.2  757.16  1139.9  763.35
  1159.6  765.51  1198.9  766.16  1228.3  769.62  1414.6  810.82  1532.3  845.66
  1620.6  866.93  1738.2  900.95  1836.3  922.18  1914.8  930.67  1944.2  931.44
#Mann= 3 , 0 , 0
       0     .06       0   958.2    .045       0  1008.2     .06       0
Bank Sta=958.2,1008.2
XS Rating Curve= 0 ,0
Exp/Cntr=0.3,0.1

Type RM Length L Ch R = 1 ,82643.2 ,638.3,651.2,663.7
XS GIS Cut Line= 4
     1479456.635      271375.117      1479217.92      271379.457
     1478293.441      271279.631     1477598.996      271440.221
#Sta/Elev= 30
       0  872.01    38.2   862.1    76.4  854.37   133.7   845.2     191  839.44
   219.6  832.88   297.5  800.06   385.6  770.99   444.3  741.96   454.1  738.55
   493.2  729.66   512.8  727.48   747.7  724.57   767.3  720.48   786.9  718.83
   835.8  718.93   904.3  722.92   963.1  724.68    1012     732  1080.5  750.75
    1149  773.13  1256.5  799.94  1363.9  811.78  1422.5  820.04    1608  851.16
  1666.6  863.31  1754.4   876.1  1783.7  878.12  1842.3  876.51  1881.4  881.24
#Mann= 3 , 0 , 0
       0     .06       0   747.7    .045       0   904.3     .06       0
Bank Sta=747.7,904.3
XS Rating Curve= 0 ,0
Exp/Cntr=0.3,0.1

Type RM Length L Ch R = 1 ,81992   ,931.1,931.7,931.5
XS GIS Cut Line= 2
     1479456.635      271062.617     1478037.364      270216.262
#Sta/Elev= 30
       0   856.9   127.9  826.49   216.4  792.55   255.7  780.06   324.6  760.08
   383.6  736.26   403.3  733.49   432.8   725.9   619.7  722.97   649.2  717.61
     659  717.41   680.7722.3115   708.2  725.07   767.2  725.36   796.7  726.86
   836.1  731.82   855.7  736.43   865.6  740.52   914.8  767.11   934.4  775.87
    1023  810.38  1180.3   867.6  1268.9  901.38  1337.7  928.67  1416.4  962.54
  1436.1  968.69  1485.2  981.29  1613.1 1021.23  1632.8 1024.64  1652.5 1025.08
#Mann= 3 , 0 , 0
       0     .06       0   619.7    .045       0   680.7     .06       0
Bank Sta=619.7,680.7
XS Rating Curve= 0 ,0
Exp/Cntr=0.3,0.1

Type RM Length L Ch R = 1 ,81060.3 ,1006.5,1023.3,1039.3
XS GIS Cut Line= 2
     1479799.517      270385.533       1478601.6      269612.964
#Sta/Elev= 30
       0  886.54    39.3  878.24    98.3  861.49   206.4  834.73   235.9  826.27
   275.3  810.68   314.6  792.63   363.7  773.47   412.9  750.09   442.4  743.24
     462  729.17   471.9  723.94   491.5  722.36     580  724.07   688.1   724.2
   708.5722.5085   727.5  716.59   737.3  716.15   766.8  722.95   796.3   731.9
   825.8   743.6   904.4  783.72   924.1  792.57  1081.4  850.35  1130.5  870.71
  1189.5  900.88  1228.8  917.59  1297.6  953.93  1376.3  989.01  1425.4 1013.18
#Mann= 3 , 0 , 0
       0     .06       0   708.5    .045       0   766.8      .1       0
Bank Sta=708.5,766.8
XS Rating Curve= 0 ,0
Exp/Cntr=0.3,0.1

Type RM Length L Ch R = 1 ,80037   ,525.5,531.5,537.3
XS GIS Cut Line= 3
     1479973.128      270190.221     1480033.892      269773.554
     1479825.559      269031.367
#Sta/Elev= 30
       0  837.91      49  832.31   117.5  817.89   166.5  808.85     235  798.33
   391.7  770.12   421.1  762.25   469.9  752.89   518.6  740.23   577.2  728.06
     626  725.07   694.3  718.37   713.8  715.81   733.3  716.88   747.9 719.984
   762.6  723.61   772.4  727.97   782.1  734.43   830.9  770.62   850.4  783.47
   918.7  821.03   957.8  844.87   967.5   849.9     987  856.56  1035.8   870.3
  1045.6  873.87  1104.1  899.08  1162.7  919.12  1172.4  920.86    1192  919.59
#Mann= 3 , 0 , 0
       0     .06       0   694.3    .045       0   747.9      .1       0
Bank Sta=694.3,747.9
XS Rating Curve= 0 ,0
Exp/Cntr=0.3,0.1

Type RM Length L Ch R = 1 ,79505.5 ,708.5,706.2,703.7
XS GIS Cut Line= 2
     1480485.281      269842.999       1480476.6      269144.214
#Sta/Elev= 30
       0  794.82    48.5  786.53    67.9  782.47   106.8  770.24   135.9  760.09
   174.7  745.53   184.4  742.88   203.8  740.09   281.5  731.68   310.6  729.42
   320.3  726.82   339.7  720.37   349.4  717.83   359.1  716.22   368.8   715.8
   378.5  715.95   388.2  717.27     398  720.75   417.4  729.44   427.1  734.98
   456.2  754.23   485.3  771.62   514.4   786.4   543.5  799.94     563  807.81
   582.4  814.82   630.9  830.25   640.6  833.05   679.4  842.33   698.8  845.93
#Mann= 3 , 0 , 0
       0     .06       0   339.7    .045       0     398      .1       0
Bank Sta=339.7,398
XS Rating Curve= 0 ,0
Exp/Cntr=0.3,0.1

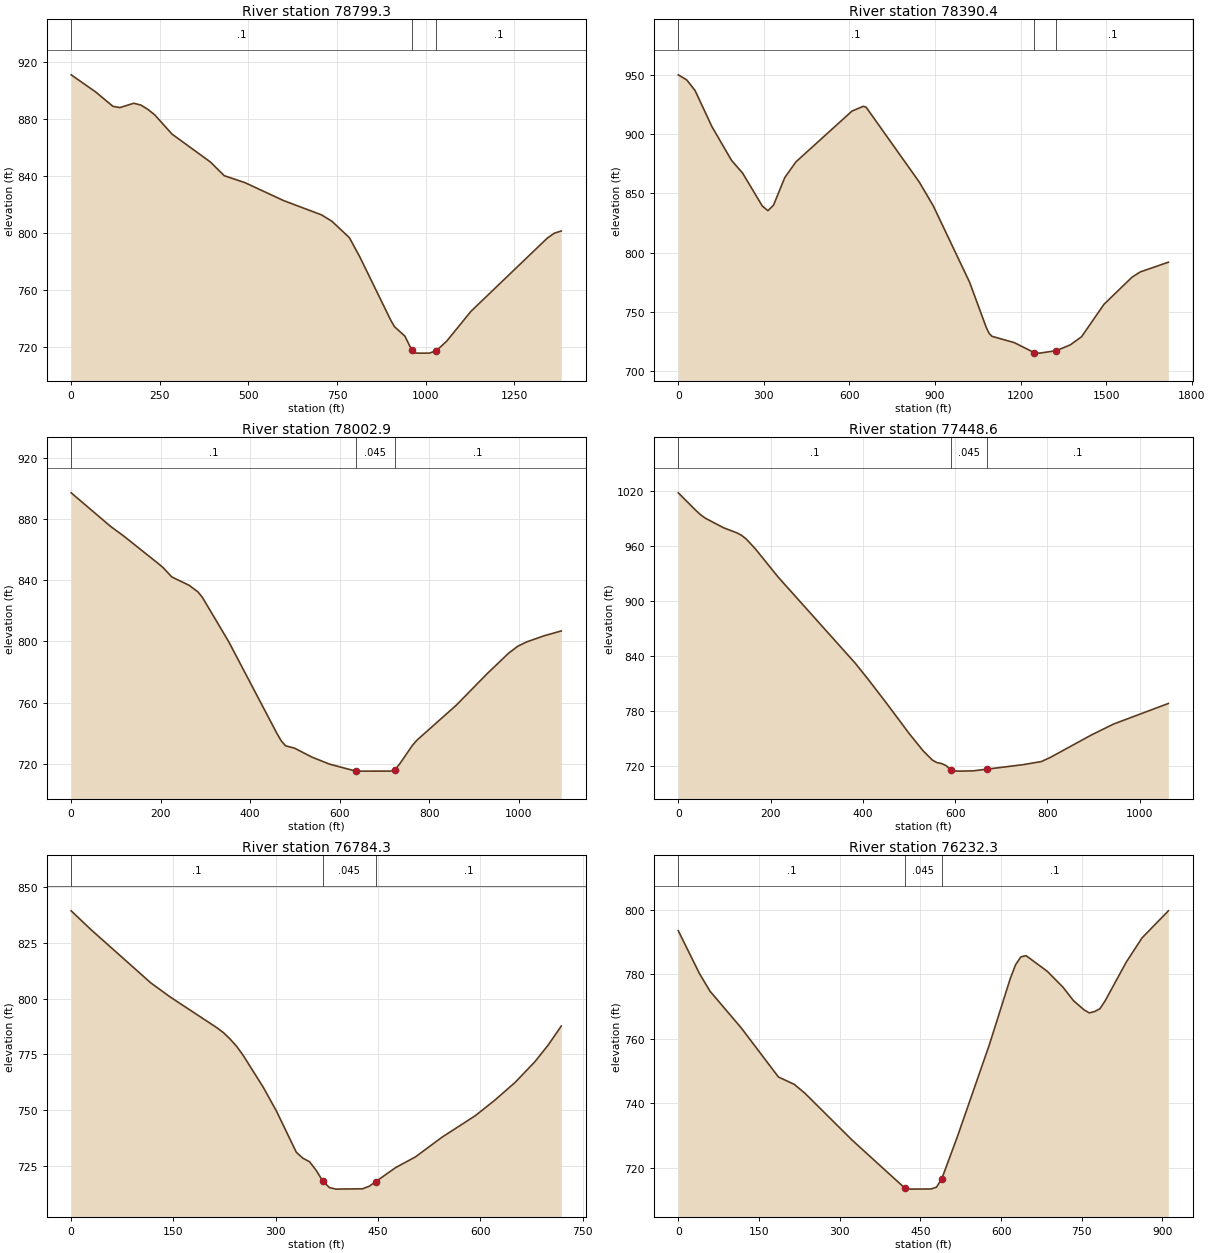
Type RM Length L Ch R = 1 ,78799.3 ,425.7,409,392.1
XS GIS Cut Line= 3
     1481127.642      270481.453     1481229.976      269891.878
     1481136.323      269113.832
#Sta/Elev= 30
       0   911.2    68.7  899.23   117.7  889.04   137.3  888.16   176.6   891.2
   196.2  889.94   215.8  887.01   235.4  883.12   284.5  869.47   392.4  849.92
   431.6  840.25   490.5   835.3   598.4  822.79   706.1  812.65   735.5  808.14
   784.5  796.65   813.9  783.13   902.1  738.13   911.9  733.98   941.2  727.33
   960.8  717.34   970.6  715.48   980.4   715.4  1009.8   715.4  1029.4  717.03
  1058.8  723.77  1127.4  744.81  1342.9  796.38  1362.5  799.78    1382  801.32
#Mann= 3 , 0 , 0
       0      .1       0   960.8    .045       0  1029.4      .1       0
Bank Sta=960.8,1029.4
XS Rating Curve= 0 ,0
Exp/Cntr=0.3,0.1

Type RM Length L Ch R = 1 ,78390.4 ,393.5,387.5,381.1
XS GIS Cut Line= 3
     1482528.684      270080.412     1481900.375      269677.182
     1481166.704      269040.047
#Sta/Elev= 30
       0  949.96    29.5  945.72    58.9  936.71   117.9  906.28   186.6  877.82
   225.9  866.91   294.7  839.23   314.3  835.33     334  839.99   373.3  863.21
   412.6  876.53     609  919.36   648.3  923.36   658.2  922.77   844.7  859.56
   893.8  839.52  1021.4  774.94  1080.3   736.5  1090.1  731.68  1099.9  729.28
  1178.4  723.95  1247.2  715.59  1266.8   715.1  1325.7  717.18  1374.7  722.11
    1414  728.95  1492.5  756.28  1590.7  779.14  1620.1  783.65  1718.3  791.82
#Mann= 3 , 0 , 0
       0      .1       0  1247.2    .045       0  1325.7      .1       0
Bank Sta=1247.2,1325.7
XS Rating Curve= 0 ,0
Exp/Cntr=0.3,0.1

Type RM Length L Ch R = 1 ,78002.9 ,575.3,554.3,533.4
XS GIS Cut Line= 2
     1482321.218      269313.485     1481335.975      268836.054
#Sta/Elev= 30
       0  897.27      88  875.31   117.3  869.01   195.5  850.76   205.3  848.33
   224.8  842.21   263.9  836.68   283.5  832.34   293.3  828.76   351.9  799.86
   459.4   739.9   469.2  734.96     479  731.66   498.5   730.2   537.6  724.31
   576.7  719.72   635.4  715.14   645.2   715.1   713.6  715.12   723.4  716.07
   733.1  719.51   762.5  732.02   772.2   735.3   860.2  758.23   928.6  778.69
   977.5  792.38   997.1  796.73  1016.6  799.57  1055.7  803.62  1094.8  806.86
#Mann= 3 , 0 , 0
       0      .1       0   635.4    .045       0   723.4      .1       0
Bank Sta=635.4,723.4
XS Rating Curve= 0 ,0
Exp/Cntr=0.3,0.1

Type RM Length L Ch R = 1 ,77448.6 ,679.4,664.2,649.2
XS GIS Cut Line= 2
     1482316.878      268237.096     1481375.038      268727.547
#Sta/Elev= 30
       0 1017.92    39.3  998.17    49.2  993.68      59  990.18    98.3  979.83
   127.8  974.16   137.6  971.44   147.5  967.49   167.2   956.8   216.3  926.23
   383.5  832.32     413   813.8   452.3  788.06   501.4  755.02   530.9  736.72
   550.6  726.85   560.4  724.08   570.3  723.08   580.1  720.87   589.9  716.56
   599.8  714.88   609.6   714.8   639.1   715.1   668.6  716.92   747.2  721.85
   786.6  725.22   806.2  729.73   894.7  754.07   943.9  766.22  1061.9  788.48
#Mann= 3 , 0 , 0
       0      .1       0   589.9    .045       0   668.6      .1       0
Bank Sta=589.9,668.6
XS Rating Curve= 0 ,0
Exp/Cntr=0.3,0.1

Type RM Length L Ch R = 1 ,76784.3 ,551.5,552,551.8
XS GIS Cut Line= 2
      1481409.76      267798.728     1481114.621       268454.11
#Sta/Elev= 30
       0  839.34    29.1   830.9   116.6  807.07   145.7   800.6   213.7  786.91
   223.4  784.68   233.1  781.83   242.8  778.52   252.5  774.41   281.7  760.21
   301.1  749.51   330.2  731.05     340  728.34   349.7  726.78   359.4  722.92
   369.1  718.08   378.8   715.2   388.5   714.5   427.4  714.65   437.1  715.79
   446.8  717.87   475.9  724.16   505.1  728.99   543.9  737.79   592.5  747.39
   621.6  754.46   650.8  762.28   679.9  771.56   699.4  779.04   718.8  787.64
#Mann= 3 , 0 , 0
       0      .1       0   369.1    .045       0   446.8      .1       0
Bank Sta=369.1,446.8
XS Rating Curve= 0 ,0
Exp/Cntr=0.3,0.1

Type RM Length L Ch R = 1 ,76232.3 ,434.9,440.7,446
XS GIS Cut Line= 2
      1480936.67      267555.672     1480559.066      268384.665
#Sta/Elev= 30
       0  793.54    39.2  780.32    58.8  774.83   117.5   763.3   186.1  748.19
   215.5   745.9   235.1  743.19   323.2  728.59   421.2   713.7     431   713.4
   470.2  713.45     480  714.03   489.8  716.63   519.1  729.83   577.9  758.04
   617.1  778.71   626.9  782.98   636.7  785.42   646.5   785.8   685.6  780.99
     715  776.04   734.6  771.84   754.2  769.01     764  768.05   773.8  768.47
   783.6  769.34   793.4   771.8   832.6  783.79     862  791.32   910.9  799.71
#Mann= 3 , 0 , 0
       0      .1       0   421.2    .045       0   489.8      .1       0
Bank Sta=421.2,489.8
XS Rating Curve= 0 ,0
Exp/Cntr=0.3,0.1

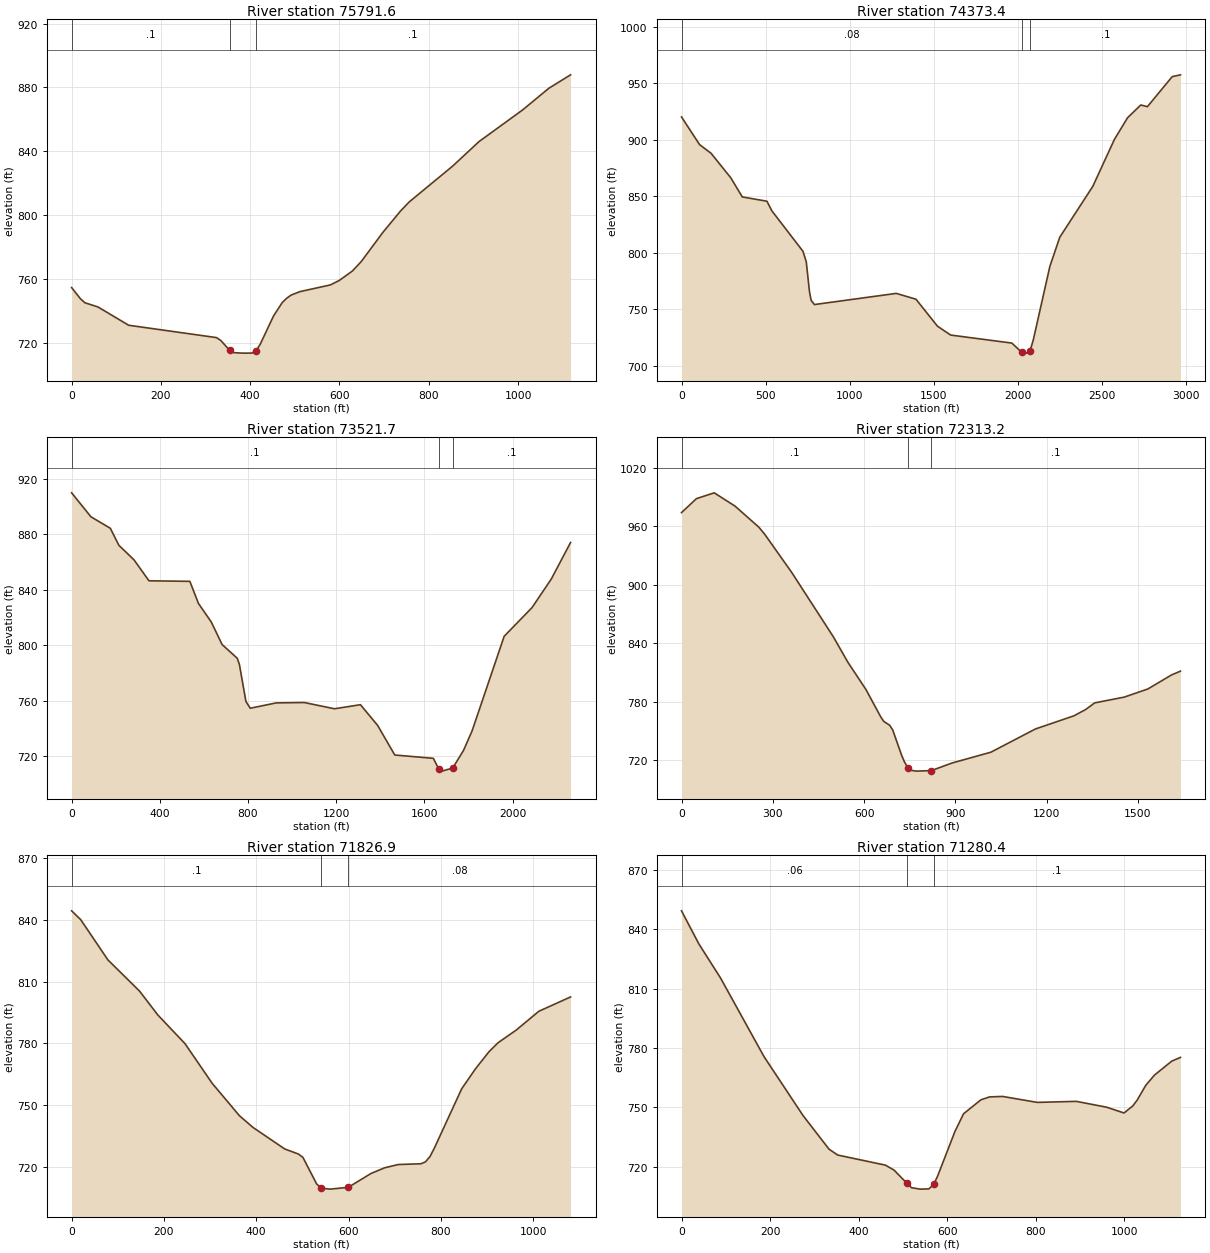
Type RM Length L Ch R = 1 ,75791.6 ,1425.4,1418.2,1410.6
XS GIS Cut Line= 3
     1480637.191      267399.422     1480233.545      267907.235
     1480246.566      268375.985
#Sta/Elev= 30
       0  754.51    19.7  747.52    29.5  745.02      59  742.36   127.8  730.88
   324.4  723.14   334.2  721.33   353.8  715.22   363.7  713.68   383.3   713.4
     403   713.4   412.8  714.67   422.6  719.05   452.1  736.61   471.8  745.12
   481.6  747.78   491.4  749.76   511.1  751.94   579.9   756.2   599.6  758.99
     629  764.91   648.7   770.8   697.5  789.22   736.6  802.47   756.2  808.21
   853.8  830.76   912.5  846.05  1010.2   865.9  1068.8  879.46  1117.6  887.92
#Mann= 3 , 0 , 0
       0      .1       0   353.8    .045       0   412.8      .1       0
Bank Sta=353.8,412.8
XS Rating Curve= 0 ,0
Exp/Cntr=0.3,0.1

Type RM Length L Ch R = 1 ,74373.4 ,824.3,851.7,877.3
XS GIS Cut Line= 5
     1480854.204      267069.561     1480190.142      267065.221
     1479973.128      267243.172     1479786.496       267672.86
     1479265.663      269135.533
#Sta/Elev= 30
       0   920.1   107.4  895.59   175.8  887.91     293  866.18   361.3  849.29
   507.8  845.47   537.1  836.96   722.1  801.13   741.5  791.93   760.8  765.24
   770.5  757.76   789.9     754  1276.6  763.88  1393.7  758.71  1521.3  734.87
  1599.9  726.99  1963.5   719.9  2022.4  711.71  2049.6     711  2071.6  712.81
  2091.2  722.85  2189.5  787.77  2248.5  813.64    2445  858.72  2572.8  900.08
  2651.4  919.41    2730  930.69  2769.3  929.18  2916.7  955.77  2965.8  957.38
#Mann= 3 , 0 , 0
       0     .08       0  2022.4    .045       0  2071.6      .1       0
Bank Sta=2022.4,2071.6
XS Rating Curve= 0 ,0
Exp/Cntr=0.3,0.1

Type RM Length L Ch R = 1 ,73521.7 ,1231.6,1208.5,1185.2
XS GIS Cut Line= 6
     1480862.017      267017.912     1480179.725      267028.328
     1479960.975       267210.62     1479799.517      267512.703
     1479148.475      267543.953     1478997.434       267804.37
#Sta/Elev= 30
       0  909.73    87.7  892.45   175.5  884.19   214.5  871.87   282.7  861.47
   350.9  846.31   536.2  845.91   575.1  830.01   633.6  816.53   682.4  800.35
   751.1  790.47   760.9  785.99   790.4  759.34     810  754.44   927.8  758.28
  1055.2  758.56  1192.2  754.05  1309.6  756.99  1387.5  742.12  1465.3  720.73
  1640.4  718.32 1664.98710.5398  1679.3   709.1    1728  711.33  1776.6  723.87
  1815.5  737.91  1961.4   806.3  2087.7  826.98  2175.1  847.58  2262.5  873.92
#Mann= 3 , 0 , 0
       0      .1       0 1664.98    .045       0    1728      .1       0
Bank Sta=1664.98,1728
XS Rating Curve= 0 ,0
Exp/Cntr=0.3,0.1

Type RM Length L Ch R = 1 ,72313.2 ,487.5,486.3,485.1
XS GIS Cut Line= 4
     1480242.225      265902.026     1479868.961       266275.29
     1479560.802      266830.846     1479243.961      267186.749
#Sta/Elev= 30
       0  974.15    48.9  988.46   107.5  994.44     176  980.79   254.2  959.22
   273.7  951.84   361.7  913.04   498.6  847.01   547.4  820.39   606.1  792.81
   654.9  764.61   664.7  760.11   684.3  756.06     694  751.32   723.4  725.33
   733.1  718.24   744.3   712.5   752.7  709.98   772.2   709.1   821.1  709.66
   889.5  717.46  1016.6   728.5  1163.2  752.33  1289.6  765.81  1328.5   772.3
  1357.7  779.07  1454.9  784.97  1532.7  793.36  1610.5  807.75  1639.7  811.64
#Mann= 3 , 0 , 0
       0      .1       0   744.3    .045       0   821.1      .1       0
Bank Sta=744.3,821.1
XS Rating Curve= 0 ,0
Exp/Cntr=0.3,0.1

Type RM Length L Ch R = 1 ,71826.9 ,540,546.5,553.2
XS GIS Cut Line= 2
     1479543.441       265806.54      1479070.35      266778.762
#Sta/Elev= 30
       0  844.37    19.7  840.09    78.6  820.54   147.4  805.31   186.8  793.76
   245.7  779.81   304.7  760.51   363.7  744.77   393.2  739.06     462   728.6
   491.5  726.16   501.3   724.5   530.8  711.69   540.6  709.58   560.3   709.1
   599.6  709.98   648.7   716.7   678.2  719.46   707.7  721.06   756.8  721.41
   766.7  722.34   776.5   724.9   786.3  729.15   845.3  757.88   874.8  767.47
   904.3  775.85     924  780.23   963.3  786.38  1012.4  795.54  1081.2  802.51
#Mann= 3 , 0 , 0
       0      .1       0   540.6    .045       0   599.6     .08       0
Bank Sta=540.6,599.6
XS Rating Curve= 0 ,0
Exp/Cntr=0.3,0.1

Type RM Length L Ch R = 1 ,71280.4 ,416.9,416.8,416.4
XS GIS Cut Line= 2
     1479191.878       265650.29     1478427.989      266479.283
#Sta/Elev= 30
       0   849.4    39.2  832.68    88.2  815.44   186.2  775.77   274.5  745.92
   333.3   728.9   352.9  725.93   460.7  720.83   480.3   718.3   509.7  711.56
   519.5  709.43   539.1   708.7   558.7   708.8   569.6711.0618   578.3  715.11
   617.6  737.76   637.2   746.8   676.4  753.85     696  755.32   725.4  755.56
   803.8  752.55     892  753.07   960.6  750.11   999.8   747.2  1019.4  750.73
  1029.2   753.6  1048.9  761.18  1068.5  766.34  1107.7  773.42  1127.3   775.3
#Mann= 3 , 0 , 0
       0     .06       0   509.7    .045       0   569.6      .1       0
Bank Sta=509.7,569.6
XS Rating Curve= 0 ,0
Exp/Cntr=0.3,0.1

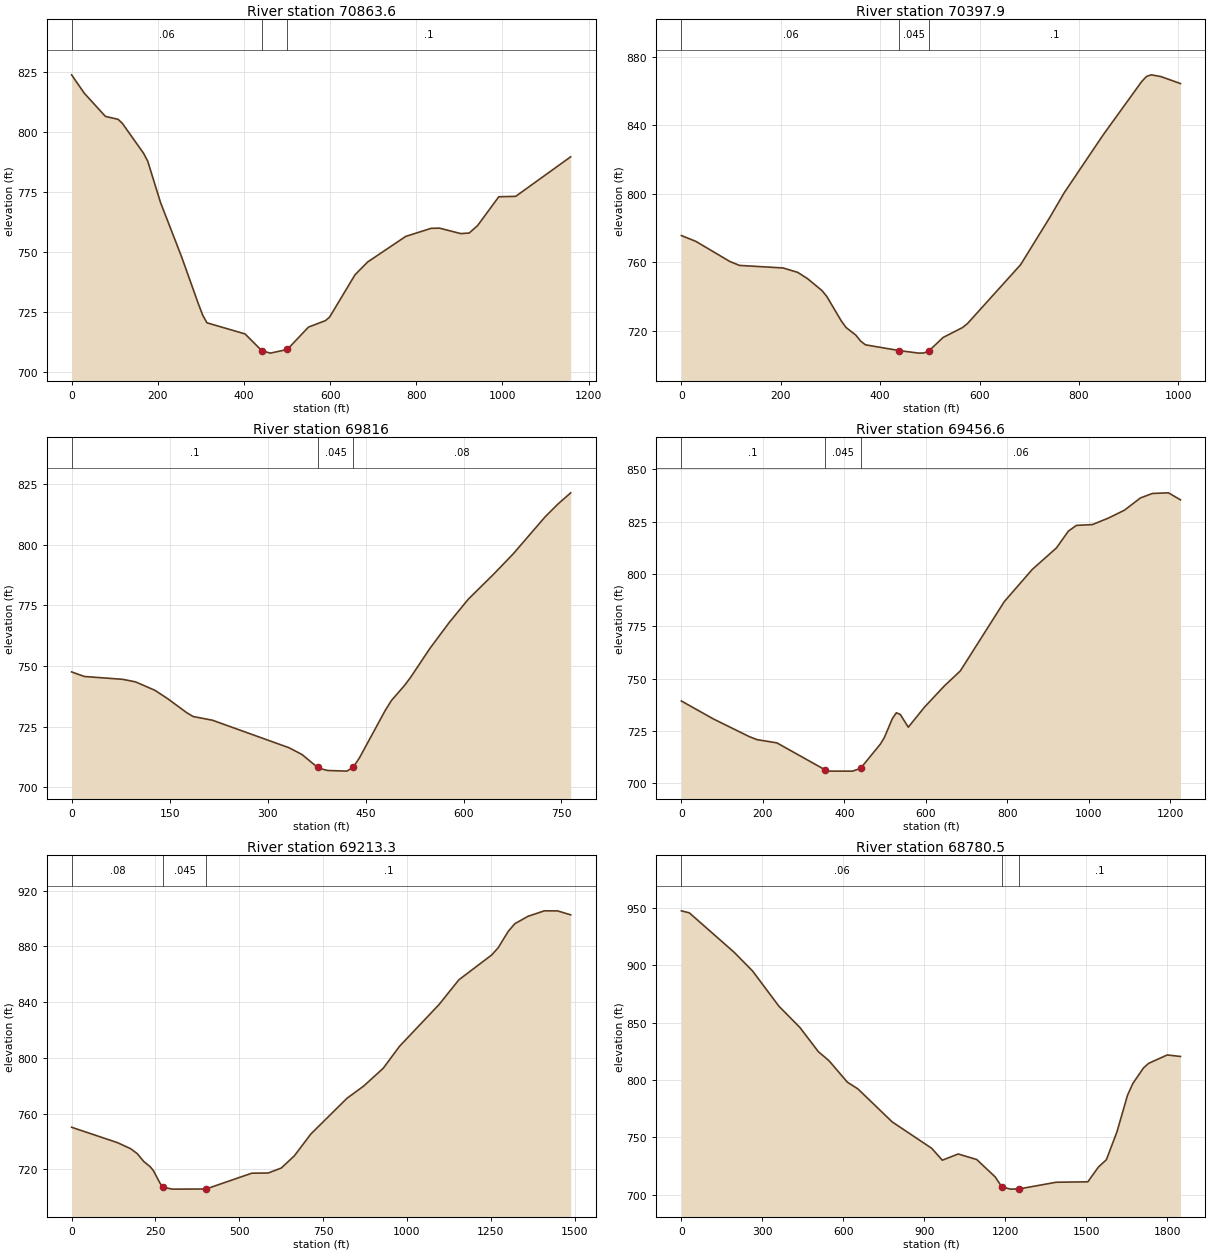
Type RM Length L Ch R = 1 ,70863.6 ,461.1,465.7,469.5
XS GIS Cut Line= 2
     1478870.698      265389.874     1478093.788      266249.249
#Sta/Elev= 30
       0  823.84    29.4  816.18    78.5  806.54     108  805.31   117.8  803.65
   166.9  791.22   176.7   787.9   206.2  770.81   255.3  748.09   294.5   728.4
   304.4  723.78   314.2  720.63   402.5  716.01   441.8  708.97   461.4  708.01
   500.6709.5313   549.8  718.84   589.1  721.53   598.9  723.02   657.8   740.6
   687.2  745.94   775.6  756.59   834.5  759.95   854.2  760.03   903.2  757.76
   922.9  757.99   942.5  761.12   991.6  773.09  1030.9  773.27  1158.5  789.72
#Mann= 3 , 0 , 0
       0     .06       0   441.8    .045       0   500.6      .1       0
Bank Sta=441.8,500.6
XS Rating Curve= 0 ,0
Exp/Cntr=0.3,0.1

Type RM Length L Ch R = 1 ,70397.9 ,568,581.9,596
XS GIS Cut Line= 2
     1478584.239      265155.499     1477781.288      265758.797
#Sta/Elev= 30
       0  775.48    29.2  772.07    97.5  760.33     117  758.04   204.8  756.54
     234  753.98   253.5  750.39   282.8  743.37   292.5  739.96   321.8   725.6
   331.5  721.74     351  717.33   360.8  713.79   370.5  711.65   438.8  708.27
   477.8   706.8   487.5  706.88   497.3  707.88   526.6  715.94   565.6  721.72
   575.3  723.94   682.6  758.44   741.1  785.93   770.3  800.45   848.3  834.09
   926.3  865.45   936.1  868.45   945.8  869.36   965.3  868.31  1004.3  864.26
#Mann= 3 , 0 , 0
       0     .06       0   438.8    .045       0   497.3      .1       0
Bank Sta=438.8,497.3
XS Rating Curve= 0 ,0
Exp/Cntr=0.3,0.1

Type RM Length L Ch R = 1 ,69816   ,348.1,359.4,370.7
XS GIS Cut Line= 2
     1478414.968      264895.082     1477651.079      264912.443
#Sta/Elev= 30
       0   747.5    19.6  745.62    78.4  744.45      98  743.39   127.4  739.94
   146.9  736.51   176.3  730.68   186.1  729.11   215.5   727.6   333.1  716.22
   352.7  713.46   372.2  709.12   377.7708.2501     382  707.57   391.8  706.87
   421.2   706.6     431  708.11   440.8  712.13     480  731.55   489.8  735.78
   509.4  741.83   519.2  745.34   548.6  757.21     578  767.83   607.4  777.51
   646.5   787.9   675.9  796.13   724.9  811.43   744.5   816.7   764.1  821.35
#Mann= 3 , 0 , 0
       0      .1       0   377.7    .045       0     431     .08       0
Bank Sta=377.7,431
XS Rating Curve= 0 ,0
Exp/Cntr=0.3,0.1

Type RM Length L Ch R = 1 ,69456.6 ,241.3,243.3,244
XS GIS Cut Line= 3
     1478380.246      264730.151     1477885.454      264474.075
     1477450.559      264981.453
#Sta/Elev= 30
       0  739.38    78.2  730.85   166.2  722.42   185.7  720.93   234.6  719.38
   351.9  706.62   361.6   705.9   420.3   705.9   439.8   707.2   488.7  718.84
   498.5  722.01     518  730.98   527.8  733.76   537.6  732.93   557.1  726.87
   596.4  736.34   645.6  746.57   684.9  753.74     793  786.87   861.8  802.25
   920.7  812.42   950.2  820.47   969.9  823.22  1009.2   823.6  1048.5  826.71
  1087.8  830.46  1127.1  836.31  1156.6  838.46  1195.9  838.76  1225.4  835.42
#Mann= 3 , 0 , 0
       0      .1       0   351.9    .045       0   439.8     .06       0
Bank Sta=351.9,439.8
XS Rating Curve= 0 ,0
Exp/Cntr=0.3,0.1

Type RM Length L Ch R = 1 ,69213.3 ,428.7,432.7,437
XS GIS Cut Line= 3
      1478441.01      264573.901      1477893.84      264214.956
     1477190.142      263767.912
#Sta/Elev= 30
       0  750.26   136.7  739.24   175.8   734.9   195.3  731.45   214.9  725.77
   234.4  721.94   244.2  719.06   263.7   710.1   273.5  707.18   300.7   705.9
   400.4  705.98   537.2  717.33     586  717.45   625.1  721.03   664.2  729.78
   713.2  745.39   821.1  771.05   870.2  779.68     929  792.52   978.1  808.41
  1095.8  838.31  1154.6  855.97  1252.7  873.83  1272.3   879.1  1301.7  890.67
  1321.4  896.18  1360.6  901.51  1409.6  905.45  1448.9  905.41  1488.1  902.58
#Mann= 3 , 0 , 0
       0     .08       0   273.5    .045       0   400.4      .1       0
Bank Sta=273.5,400.4
XS Rating Curve= 0 ,0
Exp/Cntr=0.3,0.1

Type RM Length L Ch R = 1 ,68780.5 ,719.7,700.9,684.5
XS GIS Cut Line= 3
     1479492.225      264825.203     1478749.545      264338.327
     1478015.663      263718.867
#Sta/Elev= 30
       0  947.28    29.3  945.53   195.2  911.24   263.5  894.94   361.1  864.28
   439.1   845.7   507.4  824.63   546.5  816.85   614.8  798.11   653.8  792.25
   780.7  763.53   927.2  740.52   966.4  730.19  1025.2   735.6  1093.8  730.77
  1162.4   715.6  1186.6706.9875  1219.1     705  1250.6  705.17  1387.8  710.98
  1505.4  711.37  1544.6  724.25    1574   730.6  1613.2  754.88  1652.4   786.8
    1672  796.96  1711.2   810.4  1730.8  814.54  1799.4   821.8  1848.4   820.5
#Mann= 3 , 0 , 0
       0     .06       0  1186.6    .045       0  1250.6      .1       0
Bank Sta=1186.6,1250.6
XS Rating Curve= 0 ,0
Exp/Cntr=0.3,0.1