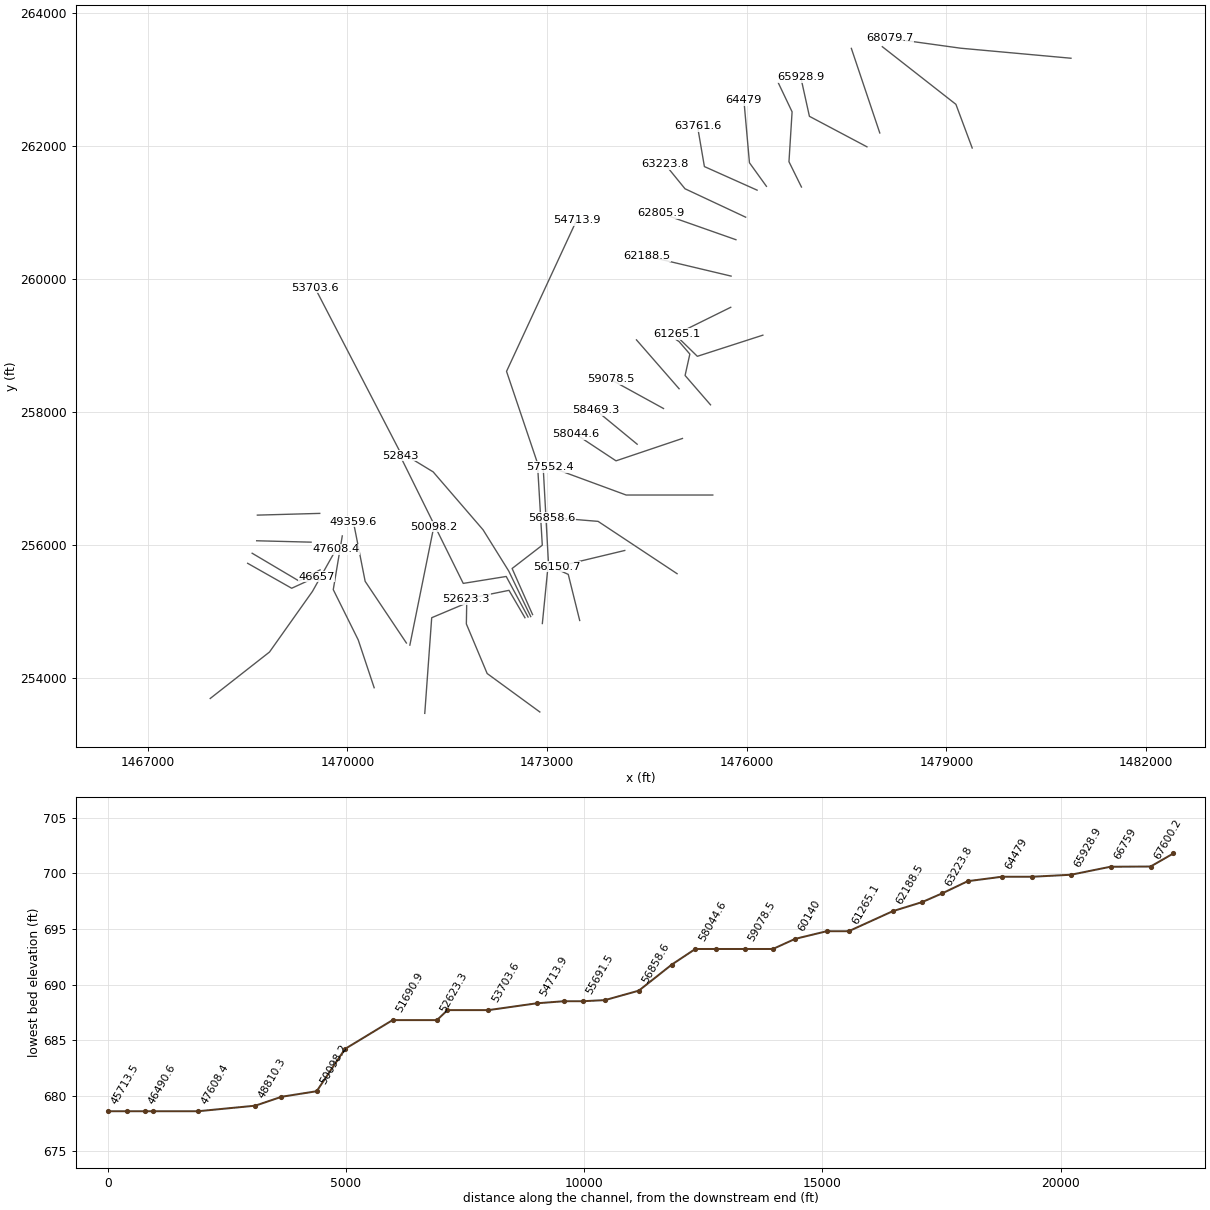
HEC-RAS study GSCR.prj: GSCR

--- GSCR.g01 (geometry) --- (continued)

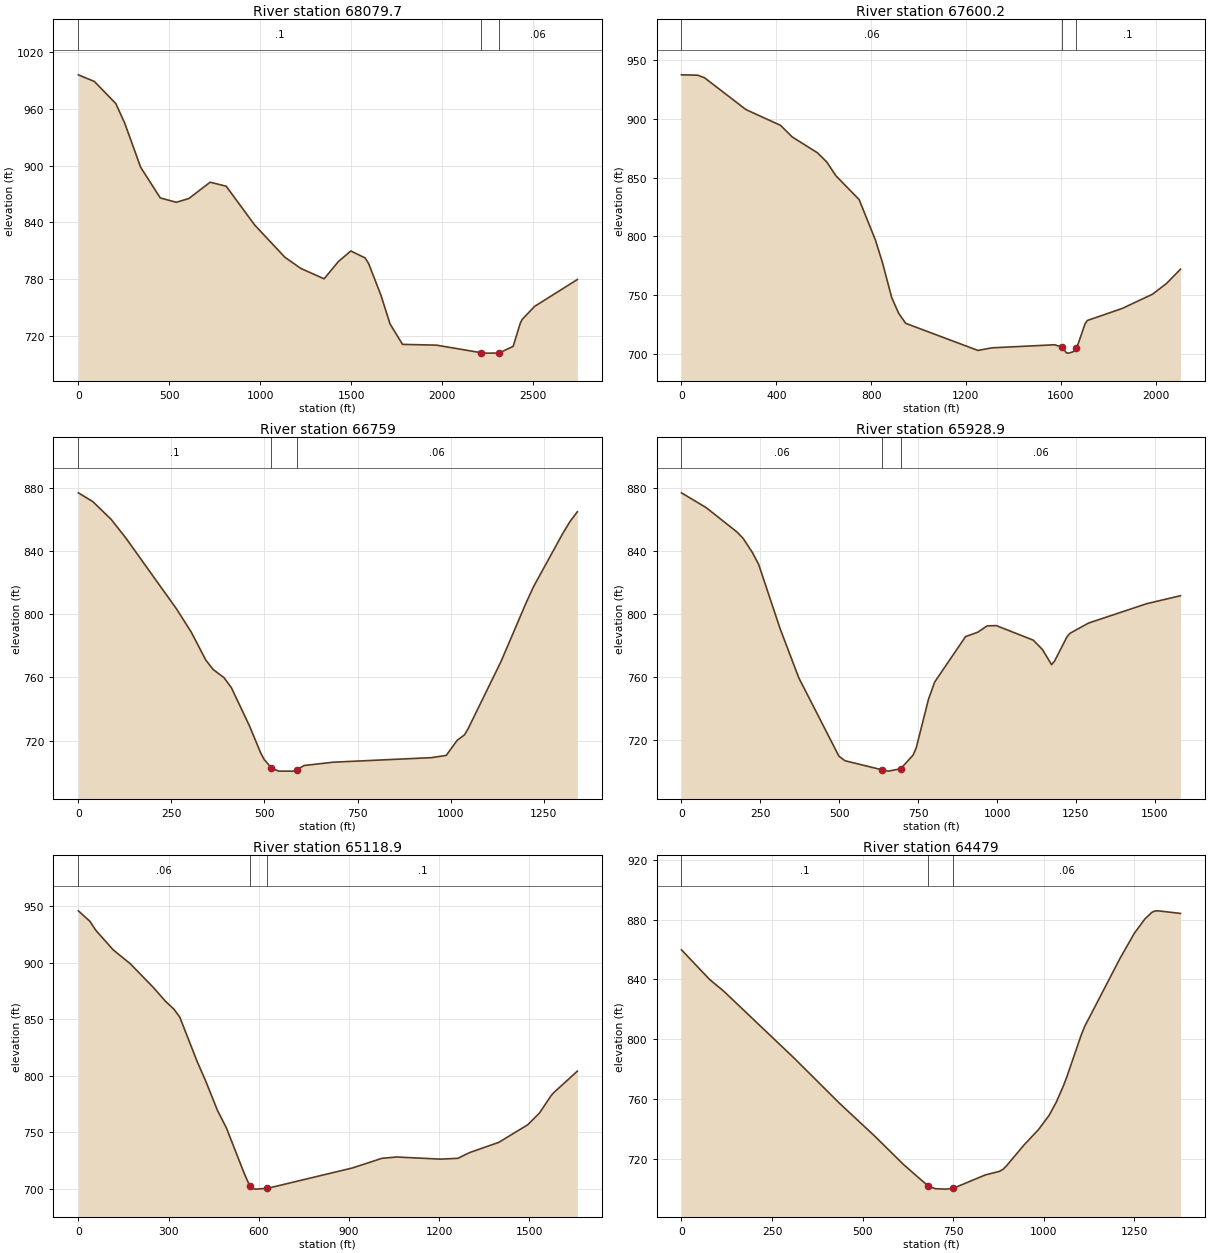
Type RM Length L Ch R = 1 ,68079.7 ,489.4,479.5,464.9
XS GIS Cut Line= 3
     1480872.434      263319.995     1479214.691      263470.699
     1478145.871       263619.04
#Sta/Elev= 30
       0     996    88.1  988.97   205.6   965.7   254.6  945.06   342.7  898.22
   450.4  865.86   538.5  861.25   607.1  865.21   724.6  882.48   812.7  878.26
   969.4  837.23  1135.8   803.1    1224  791.24  1351.2  780.35  1429.6  798.64
  1498.1  809.78  1576.4  802.46    1596  796.49  1664.6  762.47  1713.6  732.69
  1782.3  711.05  1968.7  710.24  2213.9  702.27  2243.4   701.8    2312  701.84
  2390.5  708.95  2429.7  733.42  2439.5  737.32  2508.2  751.19  2743.6  779.63
#Mann= 3 , 0 , 0
       0      .1       0  2213.9    .045       0    2312     .06       0
Bank Sta=2213.9,2312
XS Rating Curve= 0 ,0
Exp/Cntr=0.3,0.1

Type RM Length L Ch R = 1 ,67600.2 ,854.2,841.2,827.6
XS GIS Cut Line= 3
     1479388.059      261971.037     1479143.267      262627.287
     1478037.364      263493.172
#Sta/Elev= 30
       0  937.71    68.1  937.41    97.3  935.21   272.4  908.06   418.3  894.64
     467  884.82     574  871.25   612.9   863.5   651.8  851.66   749.5  831.45
   818.3  796.92   847.8  777.89     887  747.89   916.5  734.49     946     726
  1250.5  702.92  1309.4  705.13  1574.6  707.74  1605.7705.6655  1623.7  700.89
  1633.5  700.62  1653.2  701.86    1663  704.65  1672.8  708.16  1702.3   725.5
  1712.1  728.42  1859.4  738.69  1987.1  750.81    2046  759.93    2105  772.12
#Mann= 3 , 0 , 0
       0     .06       0  1605.7    .045       0    1663      .1       0
Bank Sta=1605.7,1663
XS Rating Curve= 0 ,0
Exp/Cntr=0.3,0.1

Type RM Length L Ch R = 1 ,66759   ,812.5,830,847
XS GIS Cut Line= 2
      1477999.17      262197.165     1477572.086      263467.999
#Sta/Elev= 30
       0  876.95    39.1  871.34    88.1  860.14   127.2  848.44   264.2  803.23
   303.4  788.66   342.5  770.93   362.1  765.02   391.4  759.81     411  753.52
   459.9  729.18   489.3  712.44   499.1  708.04   518.7  702.61   538.2   700.6
   577.4   700.6   587.2  701.55   606.7  704.17     685  706.26   949.2  709.15
   988.4  710.58  1017.7   720.1  1037.3  723.57  1047.1  727.44  1135.2  769.89
  1203.7  807.65  1223.2  817.59  1301.5  851.22  1321.1  858.84  1340.7  864.98
#Mann= 3 , 0 , 0
       0      .1       0   518.7    .045       0   587.2     .06       0
Bank Sta=518.7,587.2
XS Rating Curve= 0 ,0
Exp/Cntr=0.3,0.1

Type RM Length L Ch R = 1 ,65928.9 ,835.7,810.1,783.8
XS GIS Cut Line= 3
     1477806.461      261988.832     1476941.878      262447.165
      1476811.67      263035.707
#Sta/Elev= 30
       0  876.97    78.3  867.56   176.1  852.03   195.7  847.93   225.1  838.91
   244.6  831.44   313.1  790.29   371.8  759.27   499.1  709.35   518.6  706.48
   636.1  700.68   655.6  699.88   694.8  701.38   733.9  710.08   743.7  714.51
   782.8  745.58   802.4  756.58   900.3  785.49   939.4  788.31   968.8  792.32
     998  792.47  1114.7  783.24  1143.8   777.3    1173  767.61  1182.7  770.04
  1221.6  785.29  1231.3  787.58  1289.7  794.08  1474.4  806.43  1581.3   811.5
#Mann= 3 , 0 , 0
       0     .06       0   636.1    .045       0   694.8     .06       0
Bank Sta=636.1,694.8
XS Rating Curve= 0 ,0
Exp/Cntr=0.3,0.1

Type RM Length L Ch R = 1 ,65118.9 ,635.8,639.8,643.4
XS GIS Cut Line= 4
     1476822.086      261384.665     1476634.586      261764.874
     1476681.461      262514.874     1476473.128      262952.374
#Sta/Elev= 30
       0  945.79    38.5  936.49    57.8  928.68   115.6  911.35   173.4  898.82
   250.5  877.74     289  866.02     318   858.8   337.2  851.89     395  812.68
   423.9   795.1     463  769.18   492.2  754.01   550.8  714.26   570.3  702.38
   580.1  700.05   589.8   699.7   628.9  700.39   911.9  718.43  1009.5  726.92
  1058.3  728.11  1204.5  726.23  1262.6  726.94  1301.4  732.01  1398.3  741.03
  1495.2  756.67    1534  767.06  1572.7  782.39  1582.4  785.27    1660  804.02
#Mann= 3 , 0 , 0
       0     .06       0   570.3    .045       0   628.9      .1       0
Bank Sta=570.3,628.9
XS Rating Curve= 0 ,0
Exp/Cntr=0.3,0.1

Type RM Length L Ch R = 1 ,64479   ,693.2,717.5,740.4
XS GIS Cut Line= 3
     1476296.045      261395.082     1476040.836      261749.249
     1475957.503      262686.749
#Sta/Elev= 30
       0  859.85    77.6  840.03   116.4  832.23   310.4  787.54   436.5  757.11
   534.6  734.95     613  716.19   681.6  701.68   701.2  699.98   730.7   699.7
   750.3  700.24   838.5  709.17   877.7  711.58   887.5   712.9   897.3  715.25
   946.4  729.41   985.6   739.5    1015  749.04  1034.6  757.78  1054.2  768.62
    1064  774.82  1103.2  802.52    1113  808.44  1211.1  854.22  1250.3   870.9
  1279.7  880.53  1299.3  885.03  1309.1  885.93  1318.9  885.86  1377.7  884.19
#Mann= 3 , 0 , 0
       0      .1       0   681.6    .045       0   750.3     .06       0
Bank Sta=681.6,750.3
XS Rating Curve= 0 ,0
Exp/Cntr=0.3,0.1

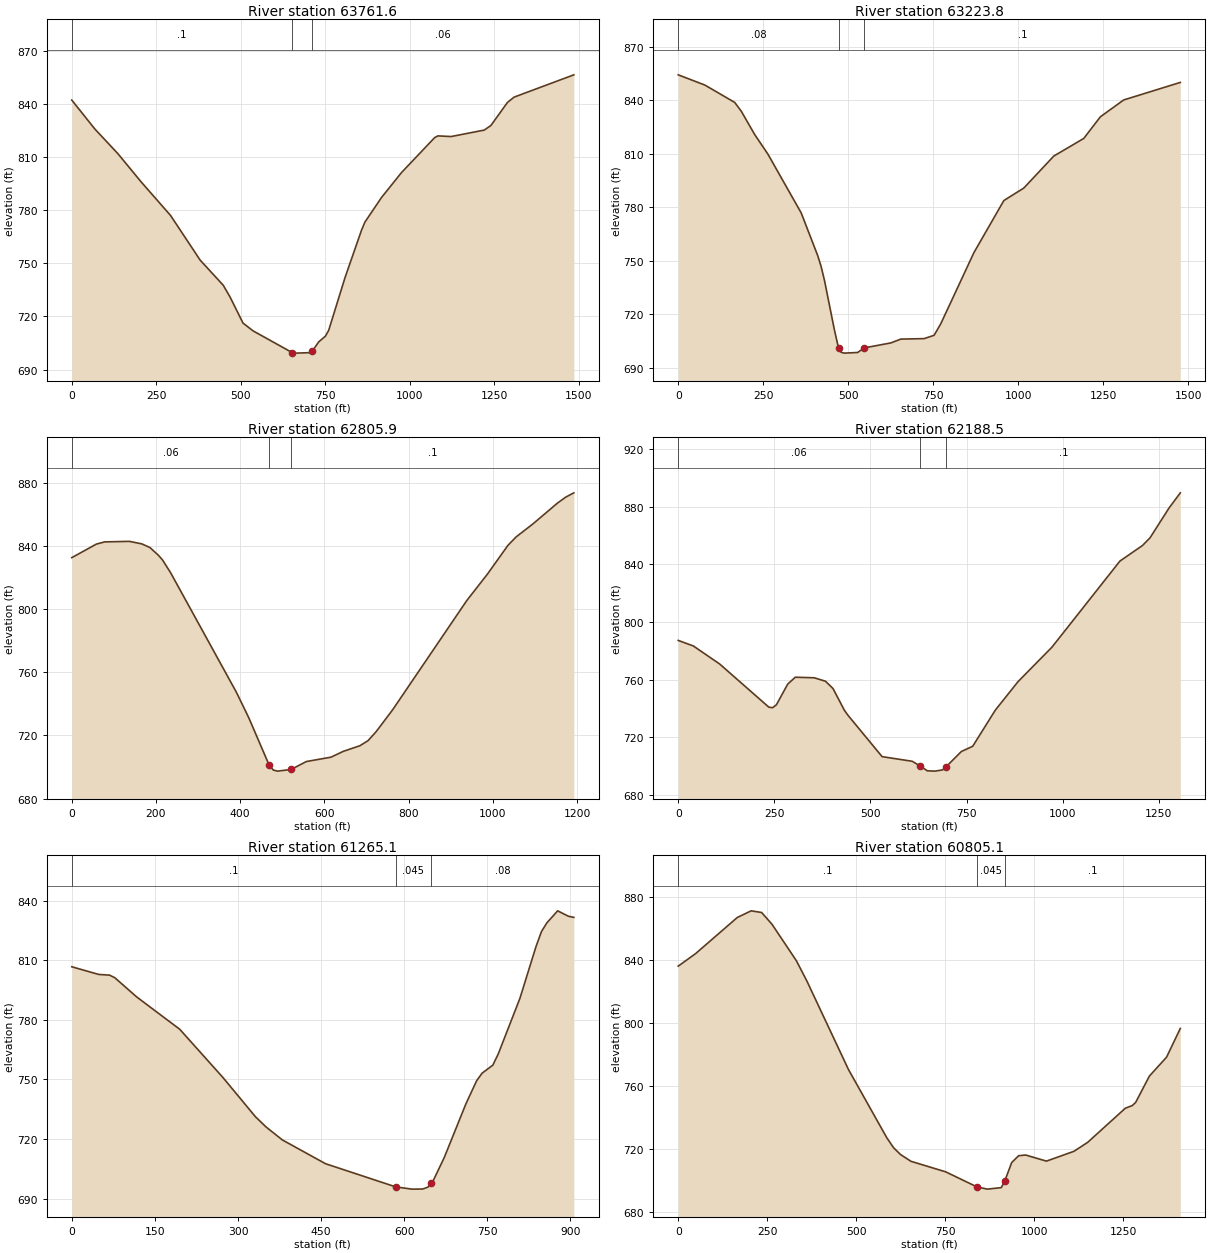
Type RM Length L Ch R = 1 ,63761.6 ,537.6,537.7,536.6
XS GIS Cut Line= 3
      1476155.42       261337.79     1475363.753      261691.957
     1475259.586      262301.332
#Sta/Elev= 30
       0  842.14    68.2  825.84   136.4  811.92   204.6  796.11   292.3  777.01
     380  751.78   448.3  737.59   467.8  731.17   506.7  716.26     536  711.92
   652.9  699.52   662.6   699.3   701.6  699.54   711.4  700.35   730.8  705.68
   750.3  708.83   760.1  712.14   808.8  742.12   857.5   768.8   867.3  773.25
   916.3  787.11   975.2  801.14  1073.4   820.9  1083.2  821.93  1122.4  821.56
  1220.5  825.21  1240.2  827.82  1289.2  840.84  1308.9  843.82  1485.5   856.4
#Mann= 3 , 0 , 0
       0      .1       0   652.9    .045       0   711.4     .06       0
Bank Sta=652.9,711.4
XS Rating Curve= 0 ,0
Exp/Cntr=0.3,0.1

Type RM Length L Ch R = 1 ,63223.8 ,415.8,418,420.3
XS GIS Cut Line= 3
     1475983.545       260931.54     1475072.086      261358.624
     1474775.211      261723.207
#Sta/Elev= 30
       0  854.34    78.2  848.61   166.1  838.86   185.7  833.84   224.8  820.86
   263.8  809.83   361.6  776.89   410.4  752.85   420.2  746.85     430  739.12
   459.3  711.28   469.1  703.01  472.96701.2909   478.8  698.69   488.6   698.2
   527.7  698.56   547.2  701.14   625.4  703.93   654.8  706.07   723.2  706.34
   752.5   708.2     772  714.59   869.7   754.6   957.7   783.8  1016.4  790.81
  1104.5  808.75  1192.7  818.64  1241.6  830.79  1310.2  840.24  1476.7  850.08
#Mann= 3 , 0 , 0
       0     .08       0  472.96    .045       0   547.2      .1       0
Bank Sta=472.96,547.2
XS Rating Curve= 0 ,0
Exp/Cntr=0.3,0.1

Type RM Length L Ch R = 1 ,62805.9 ,614.9,617.4,619.5
XS GIS Cut Line= 2
     1475837.711      260592.999     1474712.711      260988.832
#Sta/Elev= 30
       0  832.59    58.6  841.19    78.2  842.57   136.9  842.91   166.2  841.33
   185.7  838.99   205.3  834.24   215.1  831.32   234.6  823.14     391  747.38
   420.3  731.32   469.2  701.02     479  698.07   488.8  697.42   520.9698.4572
   557.2  703.49   615.8  706.26   645.2  709.98   684.3  713.48   703.8  716.72
   723.4  722.54   762.5  736.38   938.4  805.47   987.3  822.15  1036.2  840.43
  1055.8   845.8  1094.8  853.82  1153.5  867.09  1173.1  870.87  1192.6  873.64
#Mann= 3 , 0 , 0
       0     .06       0   469.2    .045       0   520.9      .1       0
Bank Sta=469.2,520.9
XS Rating Curve= 0 ,0
Exp/Cntr=0.3,0.1

Type RM Length L Ch R = 1 ,62188.5 ,907.4,923.4,938.9
XS GIS Cut Line= 2
     1475764.795      260046.124     1474493.961      260348.207
#Sta/Elev= 30
       0  787.29    39.3  783.44     108  770.88   235.7  740.98   245.5  740.61
   255.4  742.62   284.8  756.96   304.5  761.75   353.6  761.37     383  758.98
   402.7  753.89   432.1   738.9     442  735.21   530.4  706.65   608.9  703.42
   628.6  700.25   648.2  696.81   667.8   696.6   687.5  697.44   697.3  699.72
   736.6  710.21   766.1  713.84     825  738.94   883.9  758.65   972.3  782.61
  1149.1  842.33    1208  853.18  1227.7  858.56  1276.8  879.12  1306.2  889.68
#Mann= 3 , 0 , 0
       0     .06       0   628.6    .045       0   697.3      .1       0
Bank Sta=628.6,697.3
XS Rating Curve= 0 ,0
Exp/Cntr=0.3,0.1

Type RM Length L Ch R = 1 ,61265.1 ,463.3,460,456.7
XS GIS Cut Line= 2
     1475759.586      259577.374     1474947.086      259176.332
#Sta/Elev= 30
       0  806.74    48.7  802.87    68.2  802.53    77.9  801.18   116.9  791.61
   194.9  775.27   272.8     751   331.3   731.3   350.7  726.08     380  719.58
   457.9   707.6   584.6  695.93   613.8   694.8   633.3  694.85     643  695.83
   648.2697.6925   652.8  699.34   672.3  710.74   711.2  737.66   730.7  749.37
   740.5  753.16   759.9  757.22   769.7  762.87   808.7  790.78   837.9  816.97
   847.6  824.42   857.4  828.84   876.9   834.9   896.3  832.17   906.1   831.6
#Mann= 3 , 0 , 0
       0      .1       0   584.6    .045       0   648.2     .08       0
Bank Sta=584.6,648.2
XS Rating Curve= 0 ,0
Exp/Cntr=0.3,0.1

Type RM Length L Ch R = 1 ,60805.1 ,712.8,665.1,616.6
XS GIS Cut Line= 3
     1476242.225      259158.537      1475257.85      258840.828
     1474988.753      259103.415
#Sta/Elev= 30
       0  836.37    48.8  844.32   165.9  867.25   204.9  871.48   234.2  870.43
   263.5  862.92   331.8  839.83   361.1  827.05   478.2  770.75   585.5  727.57
     605  721.06   624.5  716.76   653.8  712.46   751.4  705.77   839.2  696.21
   868.5   694.8   907.5  695.76   917.3  699.97   936.8   711.7   956.3     716
   975.8  716.46  1034.4  712.58  1111.5   718.8  1150.1  724.48  1256.1  746.19
  1275.4  747.83    1285  749.86  1323.6  766.58  1371.8  778.58  1410.4  796.82
#Mann= 3 , 0 , 0
       0      .1       0   839.2    .045       0   917.3      .1       0
Bank Sta=839.2,917.3
XS Rating Curve= 0 ,0
Exp/Cntr=0.3,0.1

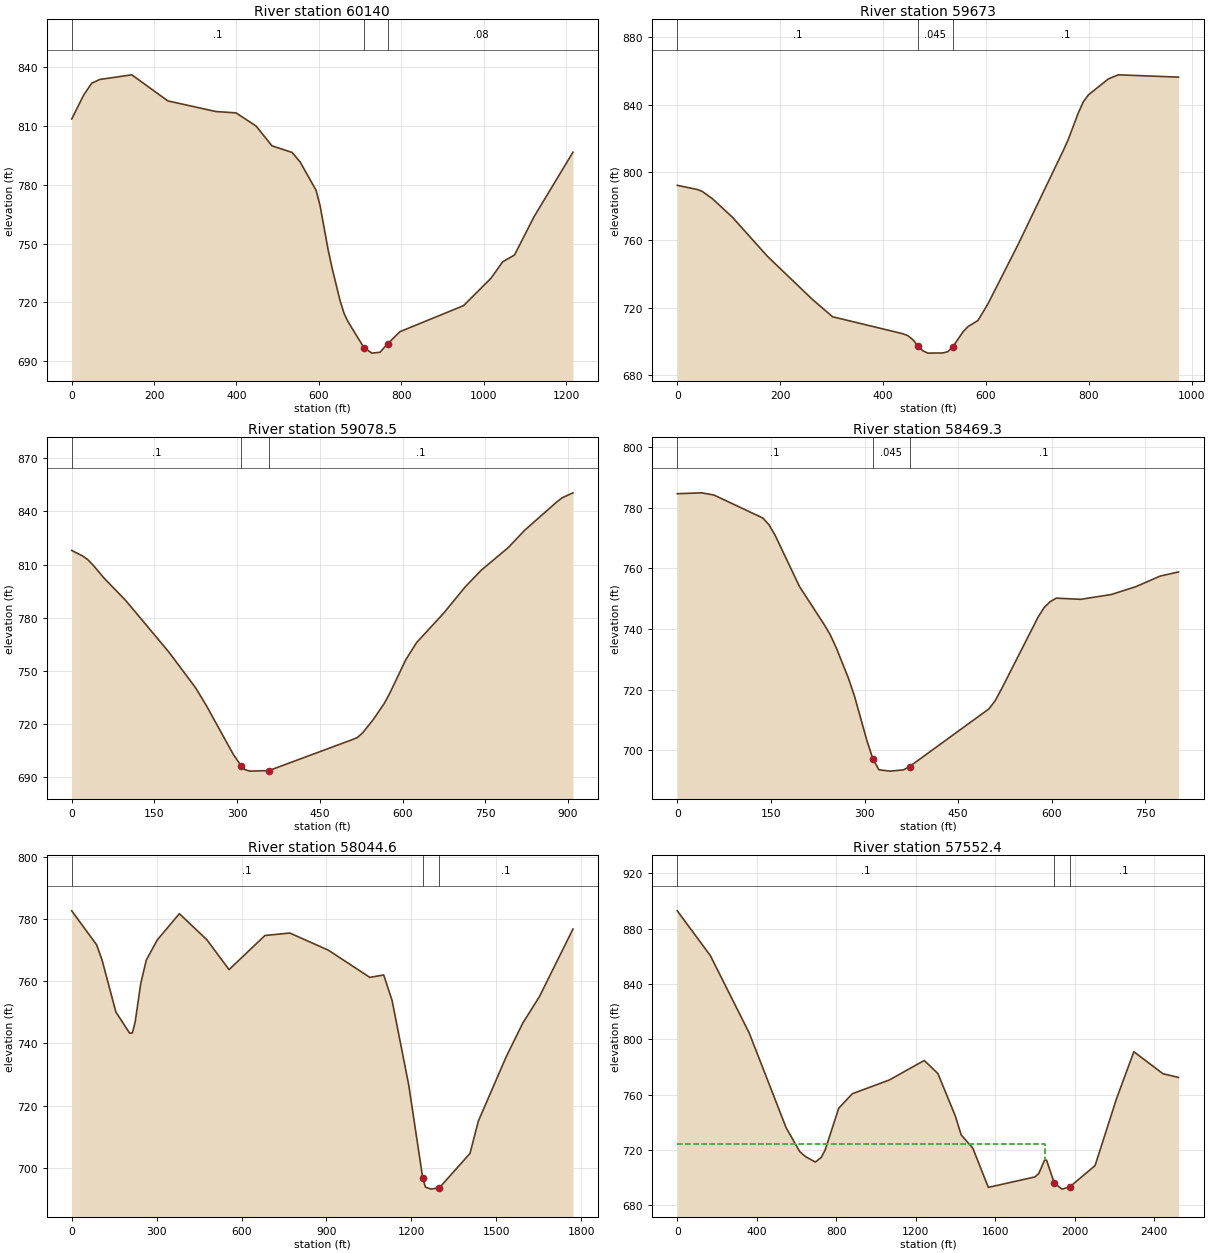
Type RM Length L Ch R = 1 ,60140   ,445.4,467,487.7
XS GIS Cut Line= 5
     1475455.767      258111.662     1475073.506      258552.511
     1475145.003      258874.249     1474983.545      259061.749
      1474936.67      259092.999
#Sta/Elev= 30
       0  813.58    29.2  825.88    48.6  831.84    68.1  833.76   145.9  836.12
   233.4  822.81   350.1  817.39   398.7  816.71   447.4  810.03   486.2  799.88
   534.9  796.52   554.3  791.73   593.2  777.22   602.9  769.39   622.3  747.05
     632  737.61   651.4  720.94     661  714.51   670.7  710.17   709.5  696.88
   728.9  694.11   748.3  694.54   767.7  699.02   796.8  705.05   951.2  718.34
  1017.8   732.3  1046.3  740.73  1074.9  744.15  1122.4  763.71  1216.9  796.65
#Mann= 3 , 0 , 0
       0      .1       0   709.5    .045       0   767.7     .08       0
Bank Sta=709.5,767.7
XS Rating Curve= 0 ,0
Exp/Cntr=0.3,0.1

Type RM Length L Ch R = 1 ,59673   ,586.5,594.5,602
XS GIS Cut Line= 2
     1474983.545      258353.415      1474342.92       259087.79
#Sta/Elev= 30
       0  792.34      39  789.88    48.7  788.71    68.2  784.46   107.2   773.5
   175.4  750.36   263.1  724.83   302.1  714.67   438.5  704.66   448.3  703.53
     458  701.14   467.8  697.58   477.5  694.55   487.3   693.2   516.5  693.31
   526.2   694.1     536  697.03   555.5  705.76   565.2  708.86   584.7   712.5
   604.2  722.42   662.7  757.42   750.4  812.84   760.1  819.38   779.6  835.08
   789.4  841.67   799.1  845.72   838.1  855.21   857.6  857.63   974.5  856.27
#Mann= 3 , 0 , 0
       0      .1       0   467.8    .045       0     536      .1       0
Bank Sta=467.8,536
XS Rating Curve= 0 ,0
Exp/Cntr=0.3,0.1

Type RM Length L Ch R = 1 ,59078.5 ,613.2,609.2,604.7
XS GIS Cut Line= 2
      1474749.17       258056.54     1473952.295       258494.04
#Sta/Elev= 30
       0  817.96    19.6  814.86    29.3  812.72    39.1  809.55    58.6  802.34
    97.8  789.71     176  760.59   224.8  740.26   244.4  730.14   293.2  702.59
   307.7695.9954   312.8   694.2   322.6   693.2   357.7693.5123   508.3  710.94
   518.1  712.19   527.8  714.88   547.4  722.55     567  731.55   576.7  737.15
     606  756.24   625.6  765.91   674.5  782.46   713.6  797.34   742.9  806.82
   791.8  819.59   821.1  829.26   879.8  845.39   889.5  847.72   909.1  850.53
#Mann= 3 , 0 , 0
       0      .1       0   307.7    .045       0   357.7      .1       0
Bank Sta=307.7,357.7
XS Rating Curve= 0 ,0
Exp/Cntr=0.3,0.1

Type RM Length L Ch R = 1 ,58469.3 ,422.4,424.7,427
XS GIS Cut Line= 2
     1474353.336      257520.082     1473733.545      258030.499
#Sta/Elev= 30
       0  784.62    39.2  784.91    58.8  784.18   137.1   776.6   146.9   774.4
   156.7  770.94   195.8  754.03     235   741.6   244.8  738.23   254.6  733.89
   274.2   723.8     284  717.82   303.5  703.46   313.3  697.25   323.1  693.63
     341   693.2   362.3  693.61   372.1  694.71   499.4  713.74   509.2   716.4
     519  720.11   577.7  743.85   587.5  747.07   597.3  749.05   607.1   750.2
   646.2  749.82   695.2   751.4   734.4  753.97   773.5  757.47   802.9  758.84
#Mann= 3 , 0 , 0
       0      .1       0   313.3    .045       0   372.1      .1       0
Bank Sta=313.3,372.1
XS Rating Curve= 0 ,0
Exp/Cntr=0.3,0.1

Type RM Length L Ch R = 1 ,58044.6 ,486.8,492.1,497.4
XS GIS Cut Line= 3
     1475033.892      257606.453     1474035.628      257270.082
      1473436.67      257665.915
#Sta/Elev= 30
       0  782.62    87.8  771.73   107.3  766.78   156.1  750.11   204.8  743.29
   214.6  743.41   224.3  746.96   243.8  759.18   263.4  766.78   302.4  773.27
   380.4  781.71   477.9   773.3     556  763.73   682.8  774.69   770.6  775.49
   907.1  769.97  1053.4  761.24  1102.6  762.01  1132.1  753.84  1191.1  726.61
  1240.3  696.86  1250.1  693.84  1269.8   693.2  1299.3  693.64  1407.5  704.67
    1437  715.05  1535.3   735.7  1594.3  746.58  1653.3  755.13  1771.4  776.77
#Mann= 3 , 0 , 0
       0      .1       0  1240.3    .045       0  1299.3      .1       0
Bank Sta=1240.3,1299.3
XS Rating Curve= 0 ,0
Exp/Cntr=0.3,0.1

Type RM Length L Ch R = 1 ,57552.4 ,687.4,693.9,699.6
XS GIS Cut Line= 3
     1475489.838       256756.41     1474187.755       256756.41
     1473041.921      257178.285
#Sta/Elev= 30
       0  892.92   166.4  860.59   362.2  804.61   548.2   736.1   616.8  718.88
   646.2  715.23   695.1  711.38   724.5  714.64     744  719.96   812.6  750.23
   881.1  760.74  1067.1  770.66  1243.3  784.77  1311.8  775.36  1399.8  744.62
  1429.1     731  1487.7  721.41  1565.8  693.07  1800.3  700.61  1819.8  703.07
  1849.1  712.87  1858.9  712.72    1898  696.11    1937   691.8  1976.1  693.47
  2103.1  708.82  2210.5  756.93  2298.4  791.09    2445   775.2  2523.1  772.52
#Mann= 3 , 0 , 0
       0      .1       0    1898    .045       0  1976.1      .1       0
#XS Ineff= 2 , 0
         1851.13   724.4
Permanent Ineff=
       F       F
Bank Sta=1898,1976.1
XS Rating Curve= 0 ,0
Exp/Cntr=0.3,0.1

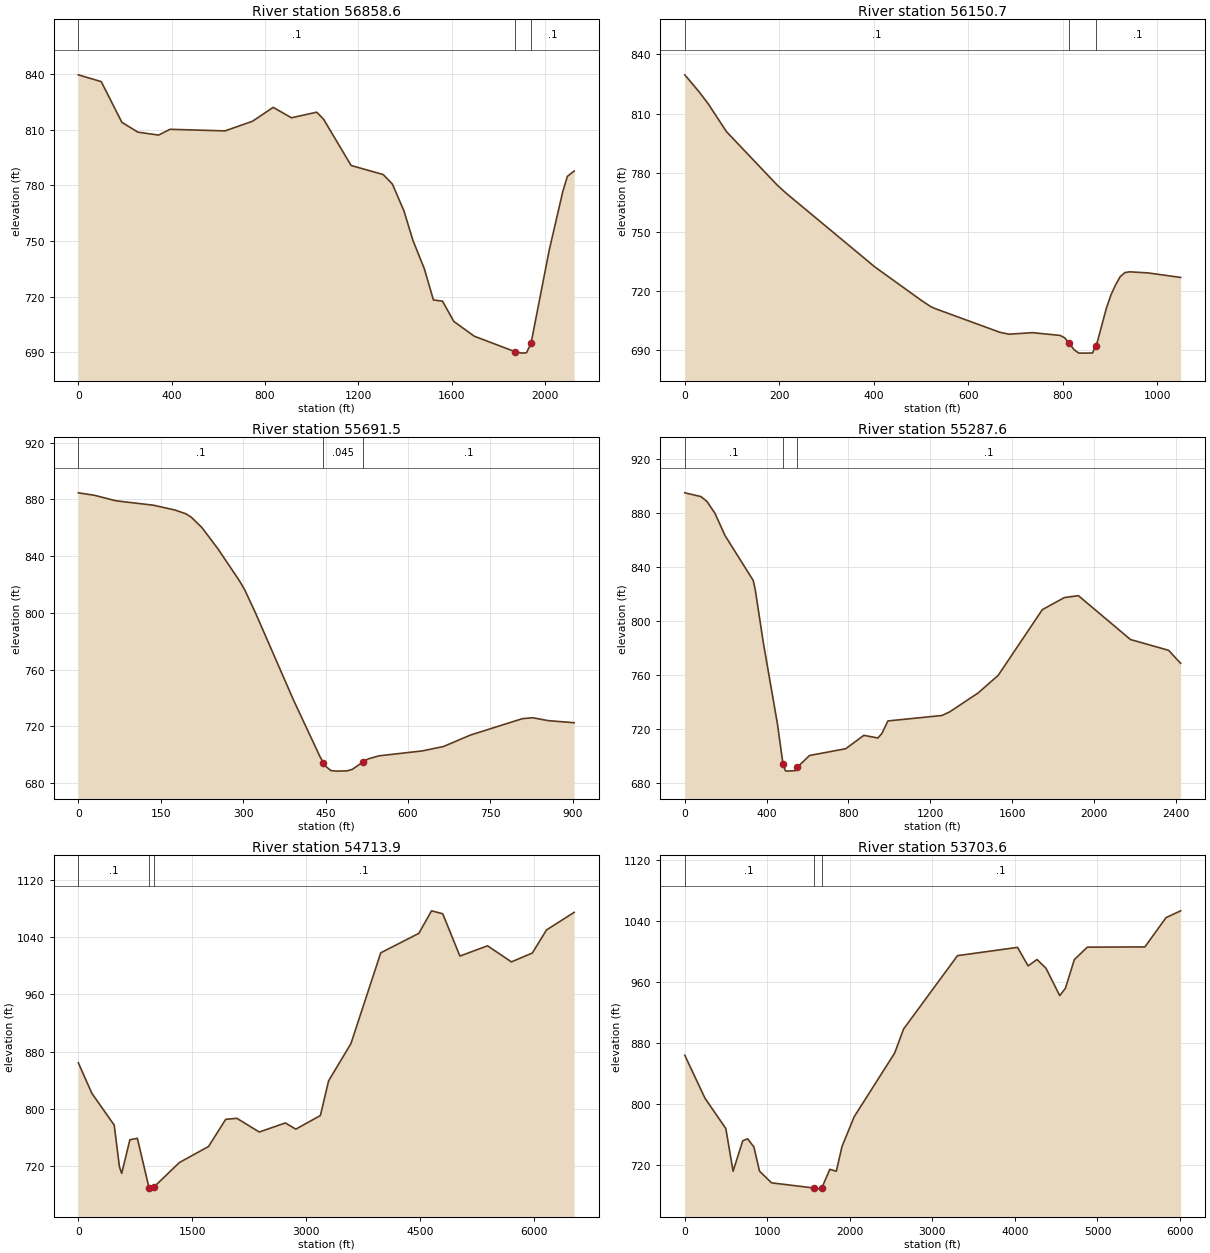
Type RM Length L Ch R = 1 ,56858.6 ,700.2,707.9,714.7
XS GIS Cut Line= 3
      1474953.38      255574.118      1473765.88      256360.577
     1473067.963      256417.868
#Sta/Elev= 30
       0  839.61    98.2  835.94   186.6  813.98   255.4  808.68   343.8   807.1
   392.9  810.21   628.7  809.36   746.5  814.57   834.9  822.05   913.5  816.43
  1021.6  819.46    1051  815.64  1168.9  790.69  1306.4  785.81  1345.7  780.67
  1394.8  766.37    1434   750.2  1482.7  734.93  1521.6  718.14  1560.5   717.5
  1609.1  706.54  1696.6  698.58  1871.7   690.2  1900.9  689.45  1920.3  689.65
  1939.8  694.73  2017.6  744.93    2076  776.67  2095.4   784.8  2124.6  787.71
#Mann= 3 , 0 , 0
       0      .1       0  1871.7    .045       0  1939.8      .1       0
Bank Sta=1871.7,1939.8
XS Rating Curve= 0 ,0
Exp/Cntr=0.3,0.1

Type RM Length L Ch R = 1 ,56150.7 ,494.4,459.2,423.3
XS GIS Cut Line= 2
     1474166.921      255923.077     1473146.088      255678.285
#Sta/Elev= 30
       0   829.6    29.4  821.24      49  815.13    88.3   800.8   196.2  773.61
   215.8  769.38   402.2  732.31   500.4   715.4     520  712.27   529.8  711.18
   667.2  699.14   686.8  698.19   735.8  698.98   794.7  697.57   804.5  696.32
   814.3  693.53   824.1  690.37   833.9  688.63   843.7   688.6   863.4  688.68
   870.1 692.365   873.2  694.07   892.8  711.52   902.6  718.26   912.4  723.35
   922.2  727.45     932  729.42   941.8   729.8   981.1  729.24  1049.8  726.94
#Mann= 3 , 0 , 0
       0      .1       0   814.3    .045       0   870.1      .1       0
Bank Sta=814.3,870.1
XS Rating Curve= 0 ,0
Exp/Cntr=0.3,0.1

Type RM Length L Ch R = 1 ,55691.5 ,411.7,403.9,396.3
XS GIS Cut Line= 3
     1473489.838      254870.993     1473317.963      255563.702
     1473146.088      255641.827
#Sta/Elev= 30
       0  884.63    29.3   882.9    68.4  879.02   136.9  875.89     176   872.5
   195.5   869.9   205.3  867.57   224.9  860.18   254.2  845.12   293.3  822.64
   303.1   816.1   322.6   799.9   391.1  739.09     440  698.57   446.2 694.409
   449.7  692.06   459.5  688.94   469.3   688.5   488.8  688.66   498.6  689.72
   518.2  694.95     528  697.17   547.5   699.3   625.7  702.72   664.8  705.87
   713.7  713.92   808.1  725.45     827  726.13   855.3  724.08   902.5  722.61
#Mann= 3 , 0 , 0
       0      .1       0   446.2    .045       0   518.2      .1       0
Bank Sta=446.2,518.2
XS Rating Curve= 0 ,0
Exp/Cntr=0.3,0.1

Type RM Length L Ch R = 1 ,55287.6 ,592,573.7,555.1
XS GIS Cut Line= 3
     1472928.591       254825.26     1473019.736      255745.399
     1472937.271      257242.795
#Sta/Elev= 30
       0  894.99    78.7  892.23   108.2  888.61   147.6  879.78   196.7  863.29
   334.4  830.01   344.3  823.38   383.6  784.13   452.5  724.02   479.8694.1504
   491.8  688.76   501.7   688.5     541  688.86   550.8  691.49   609.9   700.1
   786.9  705.13   875.5  715.05   944.2  713.09   963.8  716.48   993.2  725.73
  1257.9   729.8  1297.1  732.65  1434.3   746.5  1532.4  759.57    1748   808.3
  1855.8  817.27  1924.4  818.69  2179.3  786.14  2365.5  778.14  2424.3  768.51
#Mann= 3 , 0 , 0
       0      .1       0   479.8    .045       0   550.8      .1       0
Bank Sta=479.8,550.8
XS Rating Curve= 0 ,0
Exp/Cntr=0.3,0.1

Type RM Length L Ch R = 1 ,54713.9 ,971.6,1010.3,1047.8
XS GIS Cut Line= 6
     1472781.505      254959.535     1472474.213      255652.243
     1472927.781      256002.523     1472854.806      257238.454
     1472390.396      258614.322     1473445.084      260888.628
#Sta/Elev= 30
       0  864.65   177.2  822.21   472.4  777.66   541.3  719.48   570.8  710.28
   679.1  757.22   777.2  759.24   931.1690.1602   963.6  688.31   990.9  690.83
  1330.9  725.44  1714.1  747.78  1940.1  785.68  2087.5  787.16  2382.3  767.98
    2726  780.68  2863.3     772  3187.1  791.04    3295  839.42  3589.4  891.46
  3981.9 1018.13  4483.2 1045.26  4650.3 1076.69  4797.8 1072.59  5023.9 1013.57
  5387.6 1027.88  5702.2 1005.43  5977.5 1017.81  6164.3 1050.04  6528.1 1074.58
#Mann= 3 , 0 , 0
       0      .1       0   931.1    .045       0   990.9      .1       0
Bank Sta=931.1,990.9
XS Rating Curve= 0 ,0
Exp/Cntr=0.3,0.1

Type RM Length L Ch R = 1 ,53703.6 ,837,860.6,883.9
XS GIS Cut Line= 6
     1472754.111      254929.426     1472423.382      255614.322
     1472038.052      256233.246     1471287.966      257103.906
     1470788.834      257407.725     1469512.792      259868.663
#Sta/Elev= 30
       0  863.38   243.8  807.19   497.3  767.19     585  711.22   702.1  751.13
   760.6   753.8   837.7  742.95   905.2  711.31  1051.1  695.96  1560.9  689.21
  1580.5   687.7  1659.1   688.9  1757.3  713.68  1835.9  711.21  1904.6  743.59
    2052  782.64  2543.1  866.33  2651.1  897.87  3304.3  994.14  4031.7 1004.96
  4159.5   980.7  4267.6  989.04  4375.8  977.69  4542.9  941.67  4611.7  951.37
  4719.8   988.9  4877.1 1005.25    5575 1005.58  5830.6    1044  6007.6 1052.94
#Mann= 3 , 0 , 0
       0      .1       0  1560.9    .045       0  1659.1      .1       0
Bank Sta=1560.9,1659.1
XS Rating Curve= 0 ,0
Exp/Cntr=0.3,0.1

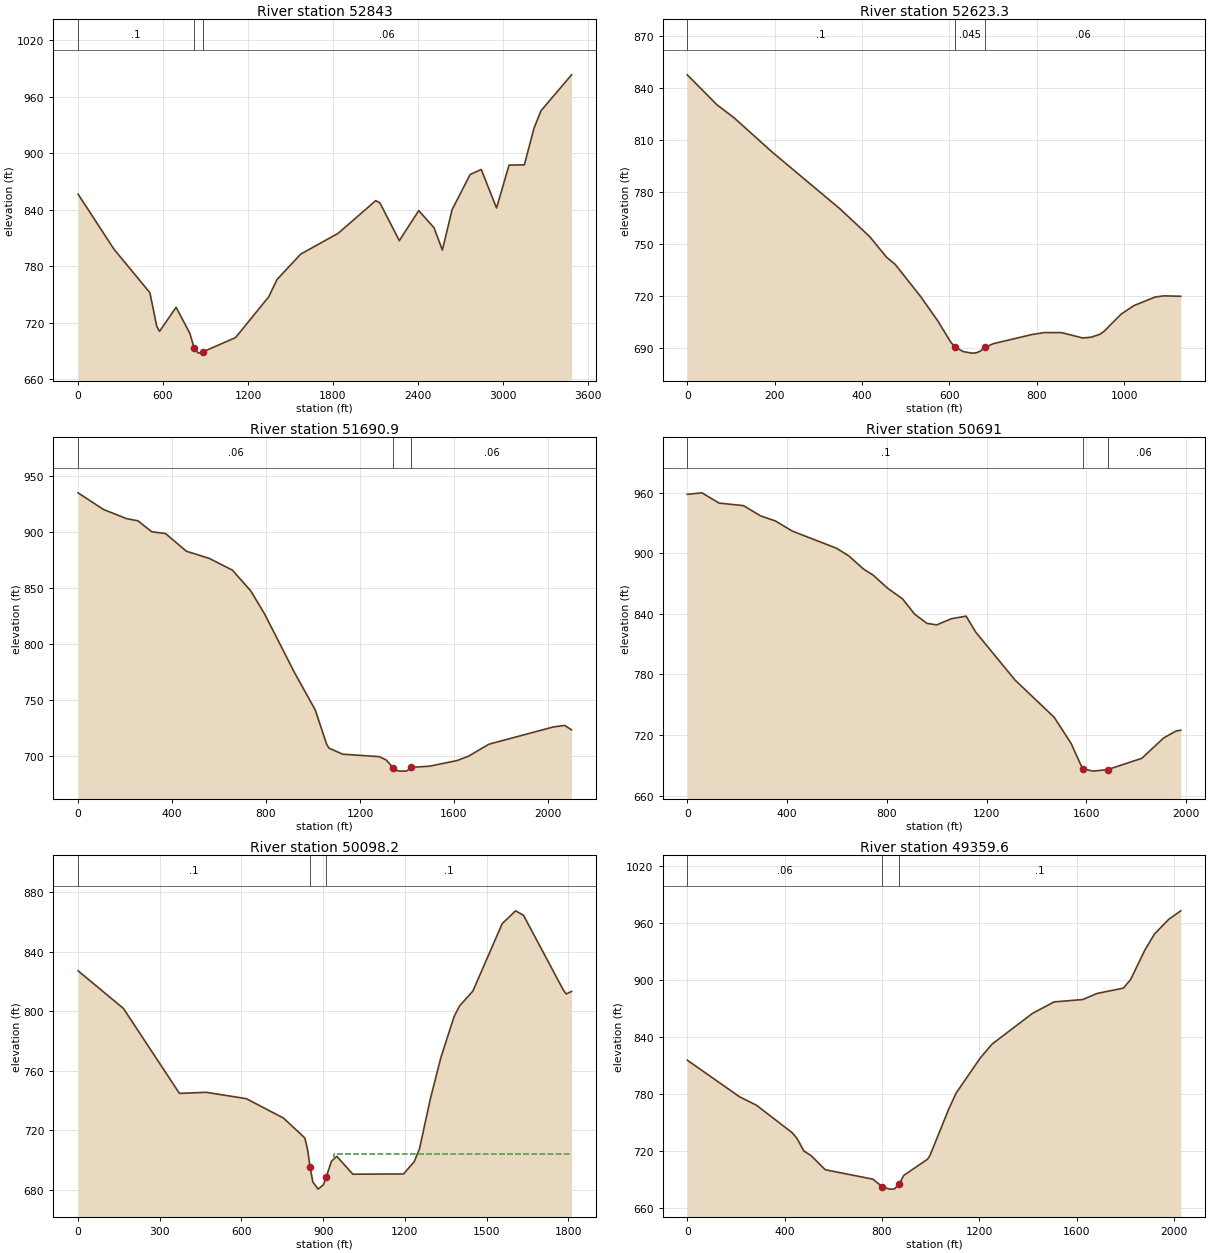
Type RM Length L Ch R = 1 ,52843   ,218.5,219.7,220.7
XS GIS Cut Line= 4
     1472713.796      254923.077     1472385.671      255532.452
     1471739.838      255428.285     1470791.707      257344.936
#Sta/Elev= 30
       0  856.44   253.4  798.02   506.9  751.88   555.6   716.2   575.1  710.78
   692.1  736.37   789.7  708.61     819  693.19   848.3   687.7   879.5 688.919
    1112   704.2  1346.3  747.49  1405.1  765.91  1571.9  792.81  1836.7  814.87
  2101.6  849.54    2131   847.3  2268.3   807.1  2405.6  838.98  2513.5  820.74
  2572.4  797.14  2641.1     840  2768.6  877.34    2847  882.64  2954.9  841.74
  3043.2  887.26  3151.1  887.54  3219.8  926.56  3268.8  944.98  3484.6  983.09
#Mann= 3 , 0 , 0
       0      .1       0     819    .045       0   879.5     .06       0
Bank Sta=819,879.5
XS Rating Curve= 0 ,0
Exp/Cntr=0.3,0.1

Type RM Length L Ch R = 1 ,52623.3 ,963.7,932.4,901.1
XS GIS Cut Line= 3
     1472666.921       254912.66     1472427.338      255324.118
     1471786.713       255193.91
#Sta/Elev= 30
       0  847.74      68  830.41   106.9  822.95   194.3   803.1   349.8   770.2
   417.8  754.15   456.7  742.15   476.1  738.11   534.7  719.39   573.7   705.4
     603  693.26   612.9690.2477   632.2  687.66   651.8   686.8   661.5  686.96
   671.3  687.98     681  690.07   700.5  692.25   788.4  697.51   817.6  698.69
   856.6  698.66   905.4  695.56     925  696.03   944.5  697.67   954.2   699.4
   993.2  709.32  1022.5  714.27  1071.3  719.25  1090.8  719.92  1129.8  719.68
#Mann= 3 , 0 , 0
       0      .1       0   612.9    .045       0     681     .06       0
Bank Sta=612.9,681
XS Rating Curve= 0 ,0
Exp/Cntr=0.3,0.1

Type RM Length L Ch R = 1 ,51690.9 ,1034.8,1000,962.7
XS GIS Cut Line= 4
      1472890.88      253495.993     1472099.213      254074.118
     1471786.713       254818.91     1471791.921       255131.41
#Sta/Elev= 30
       0  934.98   107.8  920.15   205.9  912.01   254.9     910   313.7  900.26
   372.5  898.63   460.7  882.95   558.8  876.47   656.8  866.04   735.2  847.49
     794  826.93   921.5  774.56  1009.5  741.37  1058.1  710.72  1067.9  707.33
  1126.3   701.9    1282  699.71  1311.2  696.78  1340.3   689.9  1350.1   687.6
  1369.5   686.8  1398.7  686.89  1418.2  690.18    1496  691.19  1612.8  696.21
  1661.5   700.1  1749.1  710.84  2022.4  726.16  2071.2  727.56  2100.5   723.6
#Mann= 3 , 0 , 0
       0     .06       0  1340.3    .045       0  1418.2     .06       0
Bank Sta=1340.3,1418.2
XS Rating Curve= 0 ,0
Exp/Cntr=0.3,0.1

Type RM Length L Ch R = 1 ,50691   ,570.4,592.8,615.2
XS GIS Cut Line= 3
     1471161.713       253475.16      1471265.88       254912.66
     1471760.671      255120.993
#Sta/Elev= 30
       0   958.3    58.8  959.79   127.5  949.64   225.5   947.1   294.1  936.98
     353  931.93   421.6  921.83   598.1  904.94   647.1  897.45   705.9  884.39
   745.2  878.26     804  865.15   862.8  854.82   911.8  839.56   960.8  830.51
  1000.1  829.03  1058.9  835.12  1117.7  837.66  1156.9  821.66  1313.8  774.42
  1470.6  737.55  1538.9  711.55  1577.9  690.17  1587.7  686.41  1626.7   684.2
  1685.3  685.72    1822   696.9  1909.8  717.07  1958.6  723.86  1978.1  724.76
#Mann= 3 , 0 , 0
       0      .1       0  1587.7    .045       0  1685.3     .06       0
Bank Sta=1587.7,1685.3
XS Rating Curve= 0 ,0
Exp/Cntr=0.3,0.1

Type RM Length L Ch R = 1 ,50098.2 ,720.4,738.6,756.1
XS GIS Cut Line= 2
     1470937.755      254501.202      1471297.13      256277.243
#Sta/Elev= 30
       0  827.24   166.5  801.93   372.2   744.8   470.2  745.52   617.1  741.28
   754.2  728.21   832.6  714.84   842.4  707.32   852.2  694.96   861.9  685.26
   881.5   680.4   901.1  683.41   910.9  688.42   930.5   699.2   950.1  702.47
  1008.9  690.44    1195   690.6  1234.1  698.82  1253.7  707.61  1292.9  740.65
  1332.1  768.86  1381.1  796.65  1400.6  803.61  1449.6  813.61  1557.4  858.98
  1606.4  867.59  1635.7  864.55  1782.6  814.05  1792.4  811.66    1812  813.38
#Mann= 3 , 0 , 0
       0      .1       0   852.2    .045       0   910.9      .1       0
#XS Ineff= 2 , 0
                          940.66           704.1
Permanent Ineff=
       F       F
Bank Sta=852.2,910.9
XS Rating Curve= 0 ,0
Exp/Cntr=0.3,0.1

Type RM Length L Ch R = 1 ,49359.6 ,553.7,549.3,545
XS GIS Cut Line= 3
     1470885.671      254532.452      1470265.88      255459.535
     1470088.796      256355.368
#Sta/Elev= 30
       0  815.58   215.2     777   283.7  768.28   430.4  739.44     450  733.66
   479.3  720.07   508.7  715.18   567.4  700.29     763  690.37   802.2  682.32
   831.5   679.9   851.1  679.97   870.6  685.25   890.2   694.4     988  711.45
   997.8  715.42    1076  764.86  1105.4  781.02  1203.6  817.62  1252.6  832.44
  1419.6  864.91  1507.9  876.87  1625.8  879.37  1684.7  885.77  1792.7  891.36
  1822.2  900.31  1881.1  931.47  1920.3  948.27  1979.2  963.78  2028.4  972.69
#Mann= 3 , 0 , 0
       0     .06       0   802.2    .045       0   870.6      .1       0
Bank Sta=802.2,870.6
XS Rating Curve= 0 ,0
Exp/Cntr=0.3,0.1

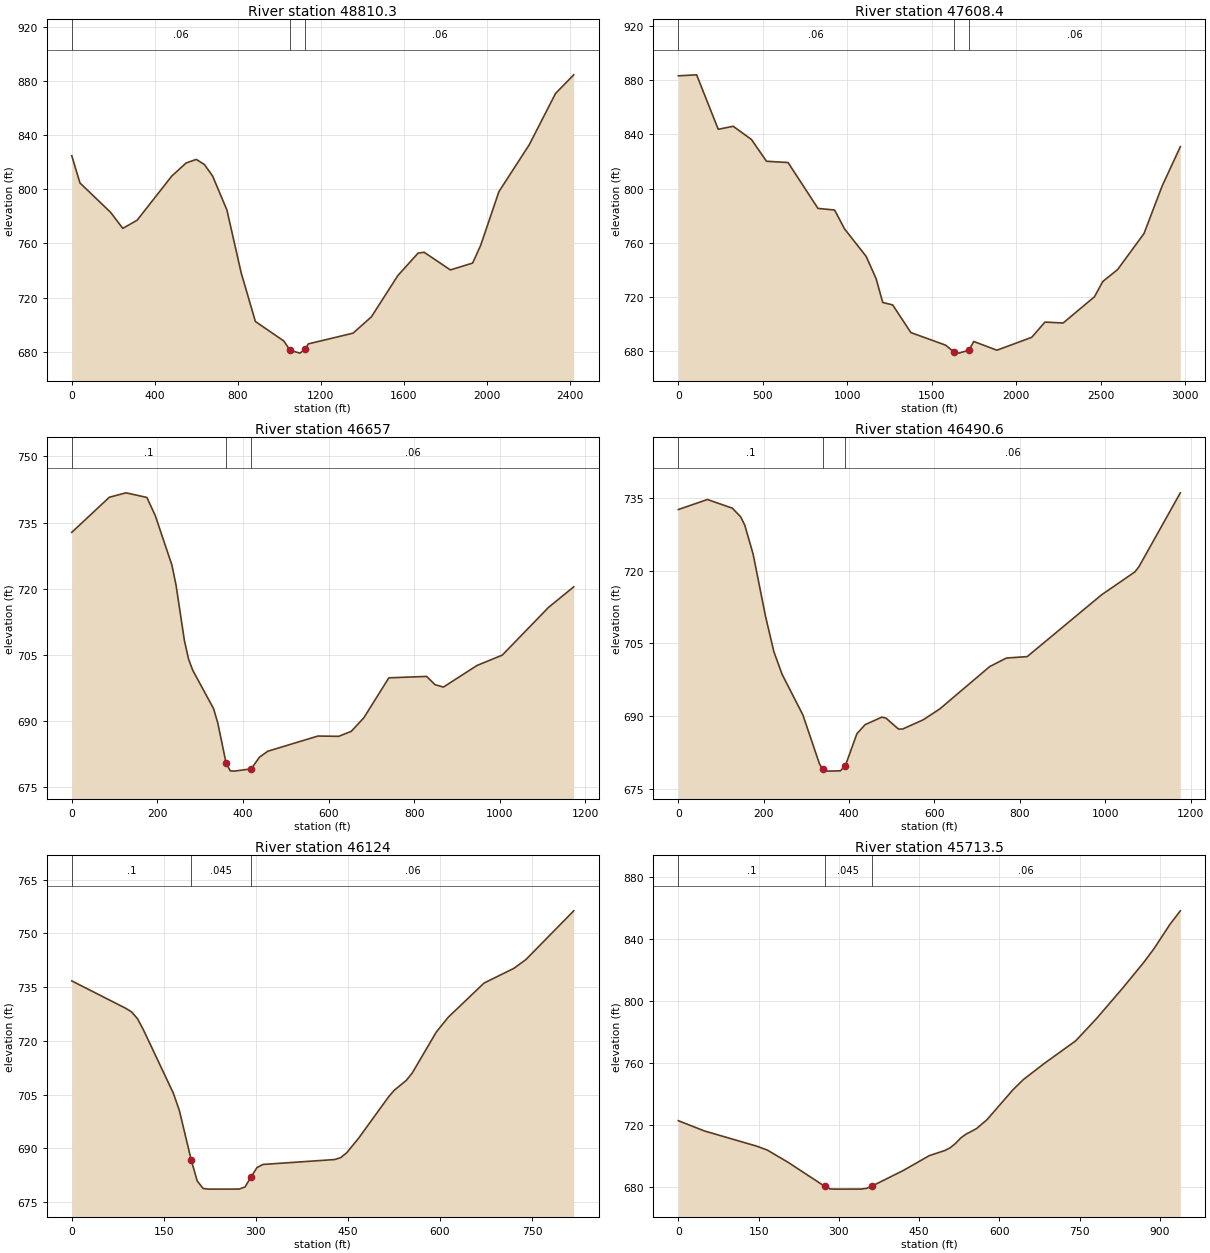
Type RM Length L Ch R = 1 ,48810.3 ,1220.3,1201.9,1175.5
XS GIS Cut Line= 4
     1470401.296      253860.577     1470161.713      254579.327
     1469786.713      255334.535      1469922.13      256141.827
#Sta/Elev= 30
       0  824.76    39.4  804.68     187  782.99     246  771.15   314.9  777.14
   482.1  809.74     551  819.37   600.2  822.02   639.6  818.22   678.9  809.76
   747.8  784.69   816.5  738.38   885.1  702.44  1022.4  688.03  1051.8  681.21
  1099.8   679.1 1124.69681.9814    1140  685.91  1355.7  693.83  1443.9  705.81
  1571.4  736.27    1669  752.84  1698.3  753.52    1825  740.49  1932.1  745.54
  1971.1  758.69  2058.8  798.22    2205  832.81  2331.7  870.66  2419.4  884.42
#Mann= 3 , 0 , 0
       0     .06       0  1051.8    .045       0 1124.69     .06       0
Bank Sta=1051.8,1124.69
XS Rating Curve= 0 ,0
Exp/Cntr=0.3,0.1

Type RM Length L Ch R = 1 ,47608.4 ,984.6,951.4,918
XS GIS Cut Line= 4
     1467937.755      253699.118      1468828.38      254397.035
     1469474.213      255308.493      1469828.38      255938.702
#Sta/Elev= 30
       0  883.28   108.2  884.01   236.1  843.81   324.7  846.04   432.9  836.27
   521.5  820.23   649.4  819.27   826.5  785.42   924.9  784.23   983.9  770.29
  1111.8     750  1170.7  733.57  1209.9  715.99  1268.7  714.19  1376.5  693.76
  1582.2  684.48  1631.2   679.5  1660.6   678.6  1719.4  680.73  1748.8  687.18
    1886  680.76  2091.8  690.26  2170.2  701.52  2277.9  700.84  2463.5  720.22
  2512.3  731.44  2600.3  740.28  2756.6  766.88    2864  801.97  2971.5  830.94
#Mann= 3 , 0 , 0
       0     .06       0  1631.2    .045       0  1719.4     .06       0
Bank Sta=1631.2,1719.4
XS Rating Curve= 0 ,0
Exp/Cntr=0.3,0.1

Type RM Length L Ch R = 1 ,46657   ,168.3,166.4,165
XS GIS Cut Line= 3
     1468500.255      255730.368     1469161.713      255355.368
     1469536.713      255527.243
#Sta/Elev= 30
       0  732.78    87.7  740.74   126.7  741.75   175.5   740.7     195  736.62
     234  725.36   243.7  720.79   263.2  708.23     273     704   282.7  701.49
   331.4  692.77   341.2  689.52   360.7   680.4   370.4  678.66   380.2   678.6
   419.2  679.12   438.7  681.77   458.2  683.12   575.2  686.56   623.9   686.5
   653.1  687.63   682.4  690.69   740.9  699.77   829.1  700.09   848.8  698.22
   868.4  697.67     947  702.58  1005.9  704.92  1113.9  715.74  1172.9  720.42
#Mann= 3 , 0 , 0
       0      .1       0   360.7    .045       0   419.2     .06       0
Bank Sta=360.7,419.2
XS Rating Curve= 0 ,0
Exp/Cntr=0.3,0.1

Type RM Length L Ch R = 1 ,46490.6 ,353.3,366.6,379.1
XS GIS Cut Line= 3
     1468567.963       255881.41     1469271.088      255464.743
     1469588.796       255631.41
#Sta/Elev= 30
       0  732.63    68.1   734.7   126.5  732.91     146  731.12   155.7  729.38
   175.1  723.45   204.3  710.55   223.8  703.28   243.2  698.57   291.9  690.18
   330.8  680.06   337.9679.0457   350.3   678.6   379.5  678.66   391.2679.7056
   418.4  686.34   437.8  688.21   476.8  689.75   486.5  689.55   515.7  687.29
   525.4  687.29   574.1  689.22     613  691.48   729.7  700.21   768.7  701.96
   817.3  702.25   991.8  715.03  1069.4  719.73  1079.1  720.81  1176.1  736.08
#Mann= 3 , 0 , 0
       0      .1       0   337.9    .045       0   391.2     .06       0
Bank Sta=337.9,391.2
XS Rating Curve= 0 ,0
Exp/Cntr=0.3,0.1

Type RM Length L Ch R = 1 ,46124   ,409.2,410.5,412.4
XS GIS Cut Line= 2
     1468635.671       256068.91      1469453.38      256048.077
#Sta/Elev= 30
       0  736.74    87.6  729.12    97.4  728.09   107.1  726.19   116.8  723.07
   165.5   705.4   175.3  700.57   194.8  686.65   204.5  680.86   214.2  678.77
     224   678.6   272.7  678.61   282.4  679.21   292.1  681.97   301.9  684.63
   311.6  685.49   428.5  686.86   438.2  687.39   447.9  688.73   467.4   692.8
   516.1  704.32   525.8  706.25   545.3  708.98     555  711.06     594  722.45
   613.5  726.59   671.9  736.14   720.6  740.25   740.1   742.7     818   756.3
#Mann= 3 , 0 , 0
       0      .1       0   194.8    .045       0   292.1     .06       0
Bank Sta=194.8,292.1
XS Rating Curve= 0 ,0
Exp/Cntr=0.3,0.1

Type RM Length L Ch R = 1 ,45713.5 ,485.8,517.2,547.4
XS GIS Cut Line= 2
     1468646.088      256454.327     1469583.588      256480.368
#Sta/Elev= 30
       0  722.68    48.8  716.07   146.5  706.27   166.1  703.78   205.2  695.85
   273.5   680.4   283.3  678.74   293.1   678.6   341.9  678.64   351.7  679.09
   361.5  680.51   420.1  690.57   468.9  700.18   498.2   703.5     508   705.3
   517.8     708   527.6  711.55   537.3  713.97   556.9  717.54   576.4  723.23
   625.2   742.6   644.8  749.23   683.9  759.62   742.5  774.15   781.6  788.59
   830.4  808.21   869.5  824.62     889  833.63   918.3  849.06   937.9  857.89
#Mann= 3 , 0 , 0
       0      .1       0   273.5    .045       0   361.5     .06       0
Bank Sta=273.5,361.5
XS Rating Curve= 0 ,0
Exp/Cntr=0.3,0.1