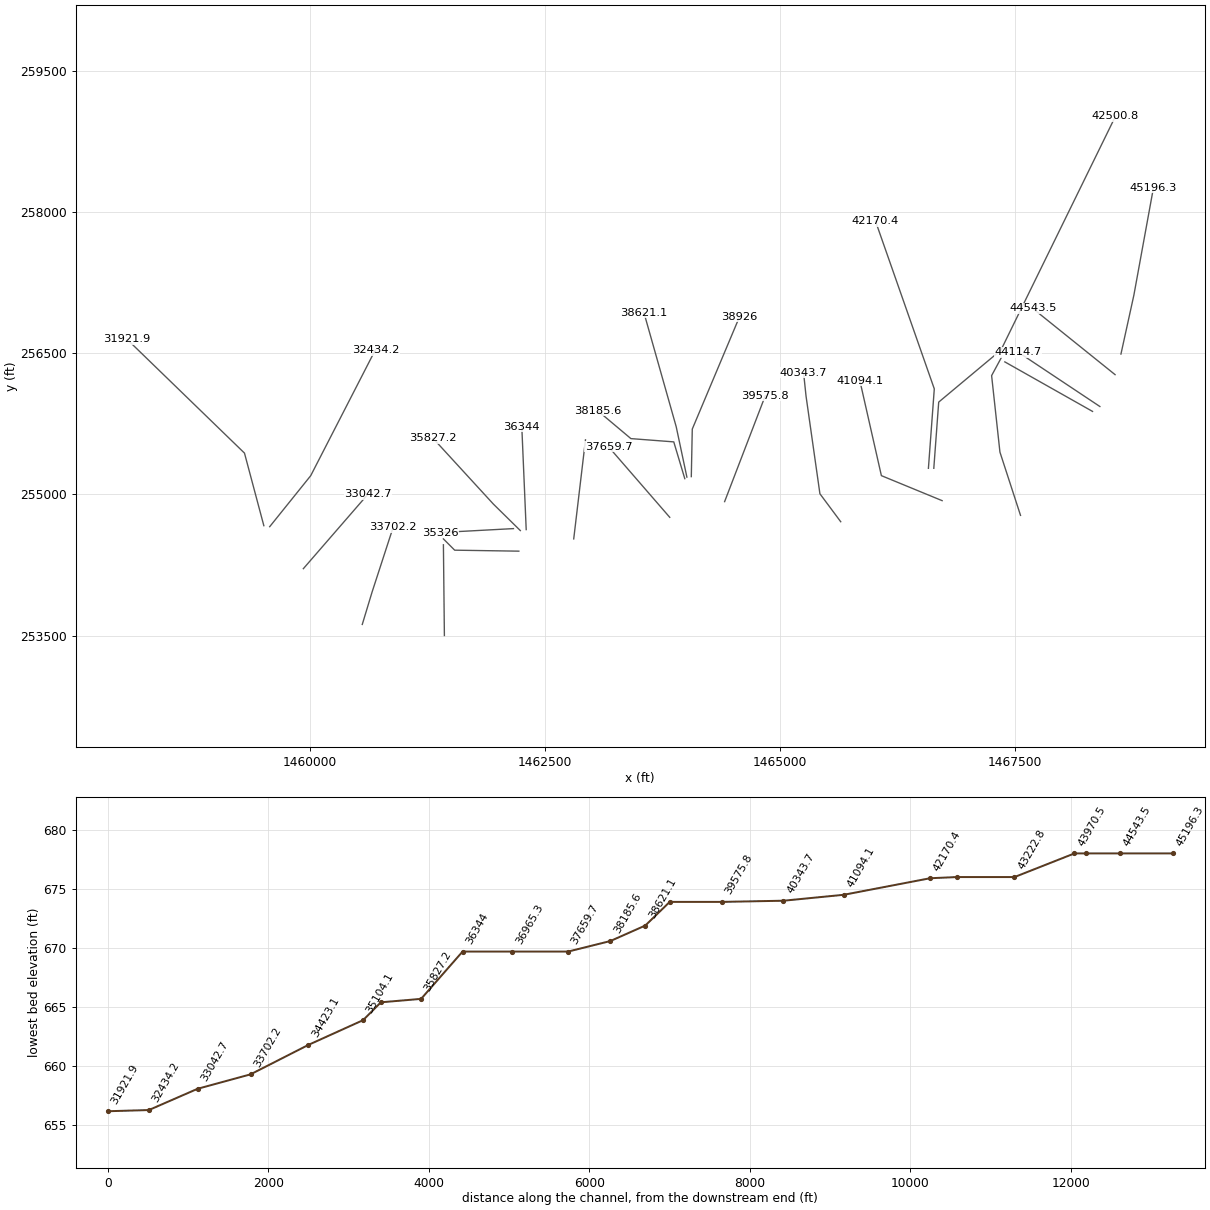
HEC-RAS study GSCR.prj: GSCR

--- GSCR.g01 (geometry) --- (continued)

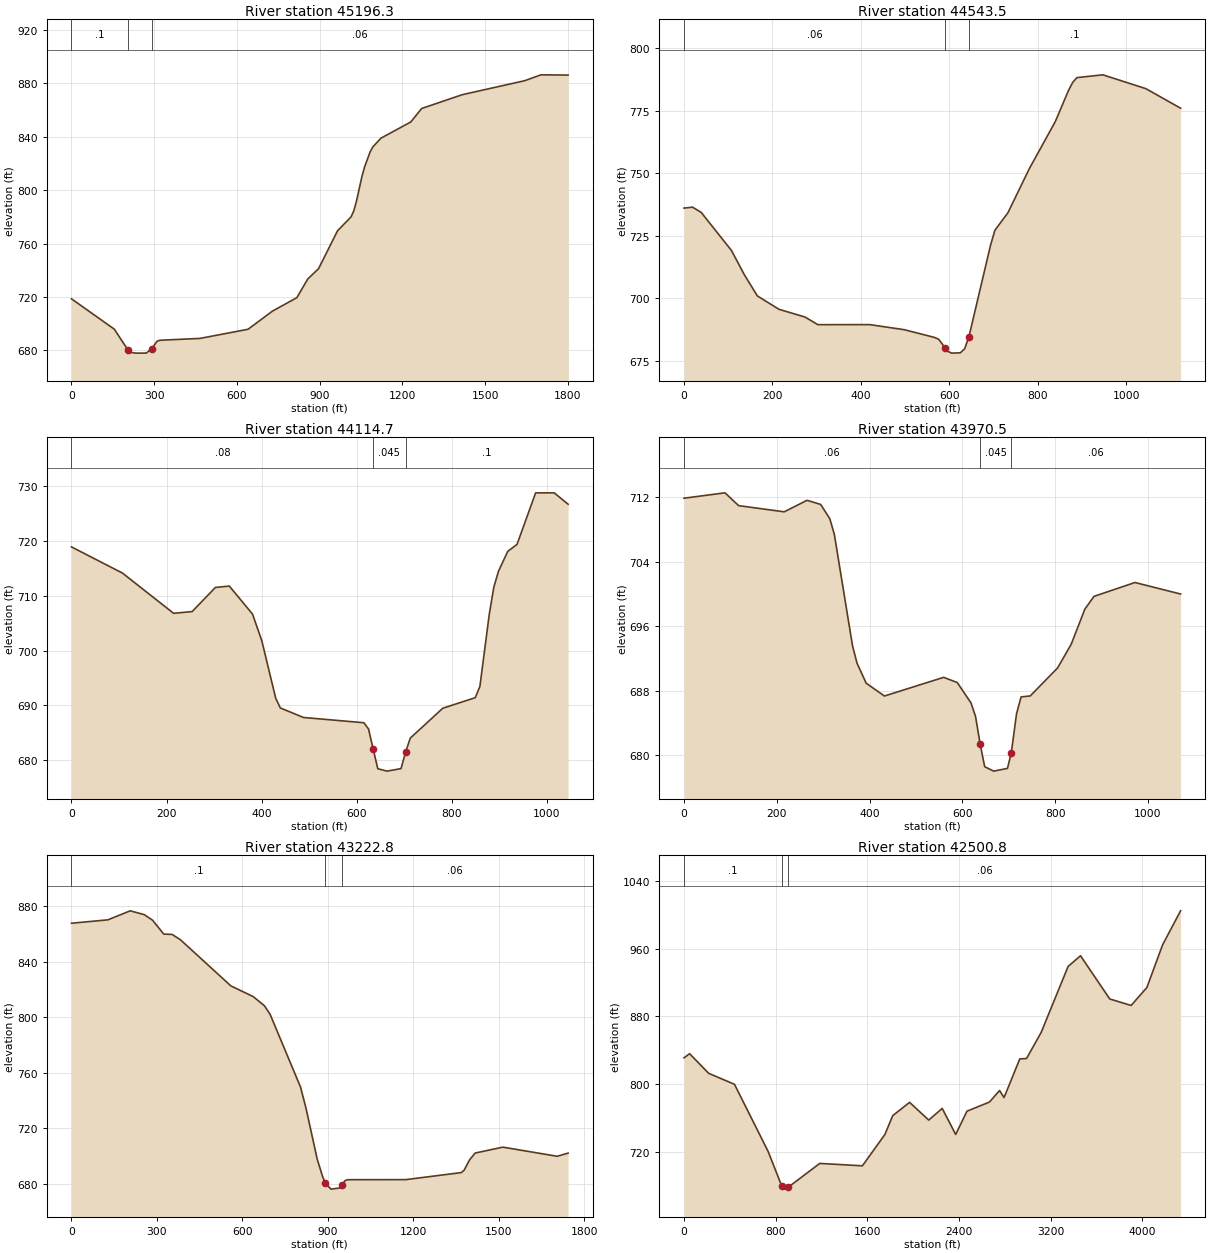
Type RM Length L Ch R = 1 ,45196.3 ,626.7,652.8,676.5
XS GIS Cut Line= 3
     1468625.255      256490.785     1468762.588      257116.002
     1468970.922      258257.495
#Sta/Elev= 30
       0  718.66   155.2  695.94   203.7   680.7   213.4  678.58   232.8     678
   271.6  678.04     291   681.4   310.4   686.9   320.1  687.63   465.5  689.01
   640.1  695.86   728.6  709.46   817.1  719.55   856.5  733.46   895.8  741.25
   964.6  769.62  1013.8  780.07  1023.6  784.57  1033.5  792.02  1053.1  810.29
    1063  817.62  1082.6  828.64  1092.5   832.4    1122  838.96  1230.1  851.08
  1269.5  861.17    1417  871.53  1643.1  881.99  1702.1  886.39  1800.5   886.2
#Mann= 3 , 0 , 0
       0      .1       0   203.7    .045       0     291     .06       0
Bank Sta=203.7,291
XS Rating Curve= 0 ,0
Exp/Cntr=0.3,0.1

Type RM Length L Ch R = 1 ,44543.5 ,426.6,428.7,430.8
XS GIS Cut Line= 2
     1468562.755      256272.035     1467687.755       256975.16
#Sta/Elev= 30
       0  736.03    19.5   736.4      39  734.29   107.4  719.06   136.6  709.31
   165.9  700.89   214.7  695.53   273.3  692.46   302.6  689.39   419.7  689.41
   497.8  687.38   566.1  684.29   575.9  683.52   589.8680.2029   595.4  678.78
   605.2     678   624.7  678.13   634.5  679.76   644.2  684.64     693  721.21
   702.8  727.17   732.1  734.13   780.9   751.9   839.4  770.68   868.7  782.92
   878.5  786.29   888.2  788.24   946.8  789.36  1044.4   783.8  1122.5     776
#Mann= 3 , 0 , 0
       0     .06       0   589.8    .045       0   644.2      .1       0
Bank Sta=589.8,644.2
XS Rating Curve= 0 ,0
Exp/Cntr=0.3,0.1

Type RM Length L Ch R = 1 ,44114.7 ,141.4,144.2,145.8
XS GIS Cut Line= 2
     1468401.296      255933.493     1467531.505      256511.618
#Sta/Elev= 30
       0  718.96   107.4  714.17   214.7  706.83   253.8  707.15   302.6  711.55
   331.9  711.81   380.7  706.69   400.2  701.84   429.5  691.31   439.2  689.54
     488   687.8   614.9  686.84   624.7   685.7   634.4  682.06   644.2  678.44
   663.7     678     693  678.46   702.8  681.52   712.5  684.03   780.9  689.49
   849.2  691.42   858.9  693.47   878.5  706.57   888.2   711.6     898  714.51
   917.5  718.15     937  719.42   976.1  728.83  1015.1  728.84  1044.4  726.76
#Mann= 3 , 0 , 0
       0     .08       0   634.4    .045       0   702.8      .1       0
Bank Sta=634.4,702.8
XS Rating Curve= 0 ,0
Exp/Cntr=0.3,0.1

Type RM Length L Ch R = 1 ,43970.5 ,770.4,747.7,725.9
XS GIS Cut Line= 2
     1468323.171       255881.41      1467390.88      256407.452
#Sta/Elev= 30
       0   711.9    88.4  712.57   117.8  710.98   216.1  710.21   265.2  711.64
   294.6  711.13   314.3  709.36   324.1  707.42   363.4  693.54   373.2  691.38
   392.8  688.92   432.1  687.33   559.8  689.65   589.2     689   618.7  686.47
   628.5   684.8   638.4  681.37   648.2  678.55   667.8     678   697.3  678.34
   705.5680.2477   716.9  685.13   726.7  687.22   746.4  687.34   805.3  690.81
   834.8  693.77   864.2  698.13   883.9  699.71   972.2  701.43  1070.5     700
#Mann= 3 , 0 , 0
       0     .06       0   638.4    .045       0   705.5     .06       0
Bank Sta=638.4,705.5
XS Rating Curve= 0 ,0
Exp/Cntr=0.3,0.1

Type RM Length L Ch R = 1 ,43222.8 ,744.1,721.9,699.7
XS GIS Cut Line= 4
     1467557.546      254777.243     1467338.796      255449.118
     1467250.255      256261.618     1467354.421      256454.327
#Sta/Elev= 30
       0  867.65   127.6  870.09   206.1  876.59   255.2  873.86   284.6  869.83
   323.8  859.82   353.3  859.58   382.7  855.68   559.4  822.48   637.9  814.76
   677.2  808.16   696.8  802.13   803.9  749.56   823.4  734.07   862.3  697.73
   881.7  684.85   891.5   680.2   910.9     676   940.1  676.77   949.8  679.11
   959.6  682.06   969.3   682.8  1173.6  682.85  1368.2  687.93    1378   689.6
  1397.4  697.16  1416.9  702.02  1514.2  706.26  1704.9  699.67    1743  701.96
#Mann= 3 , 0 , 0
       0      .1       0   891.5    .045       0   949.8     .06       0
Bank Sta=891.5,949.8
XS Rating Curve= 0 ,0
Exp/Cntr=0.3,0.1

Type RM Length L Ch R = 1 ,42500.8 ,302.7,330.4,358
XS GIS Cut Line= 4
     1466635.671      255277.243     1466687.755      255980.368
     1467349.213      256532.452     1468567.276      259017.044
#Sta/Elev= 30
       0  831.09      49  835.99   215.4   812.8   440.7  799.83   734.4  720.51
   851.9  680.09   891.1     676   910.7  678.34  1184.8  706.37  1556.8  703.53
  1753.1  740.47  1821.8  762.81  1968.9  778.51  2135.8  757.56  2253.5  771.37
  2371.2  740.58  2469.4  768.07  2665.6  778.86  2753.9   792.5  2793.2  784.16
  2930.6  829.84  2989.4  830.27    3117  861.11  3352.5  939.12  3460.4  951.69
  3715.6  900.63    3902  892.97  4039.4   914.1  4176.7  964.55  4333.7 1004.75
#Mann= 3 , 0 , 0
       0      .1       0   851.9    .045       0   910.7     .06       0
Bank Sta=851.9,910.7
XS Rating Curve= 0 ,0
Exp/Cntr=0.3,0.1

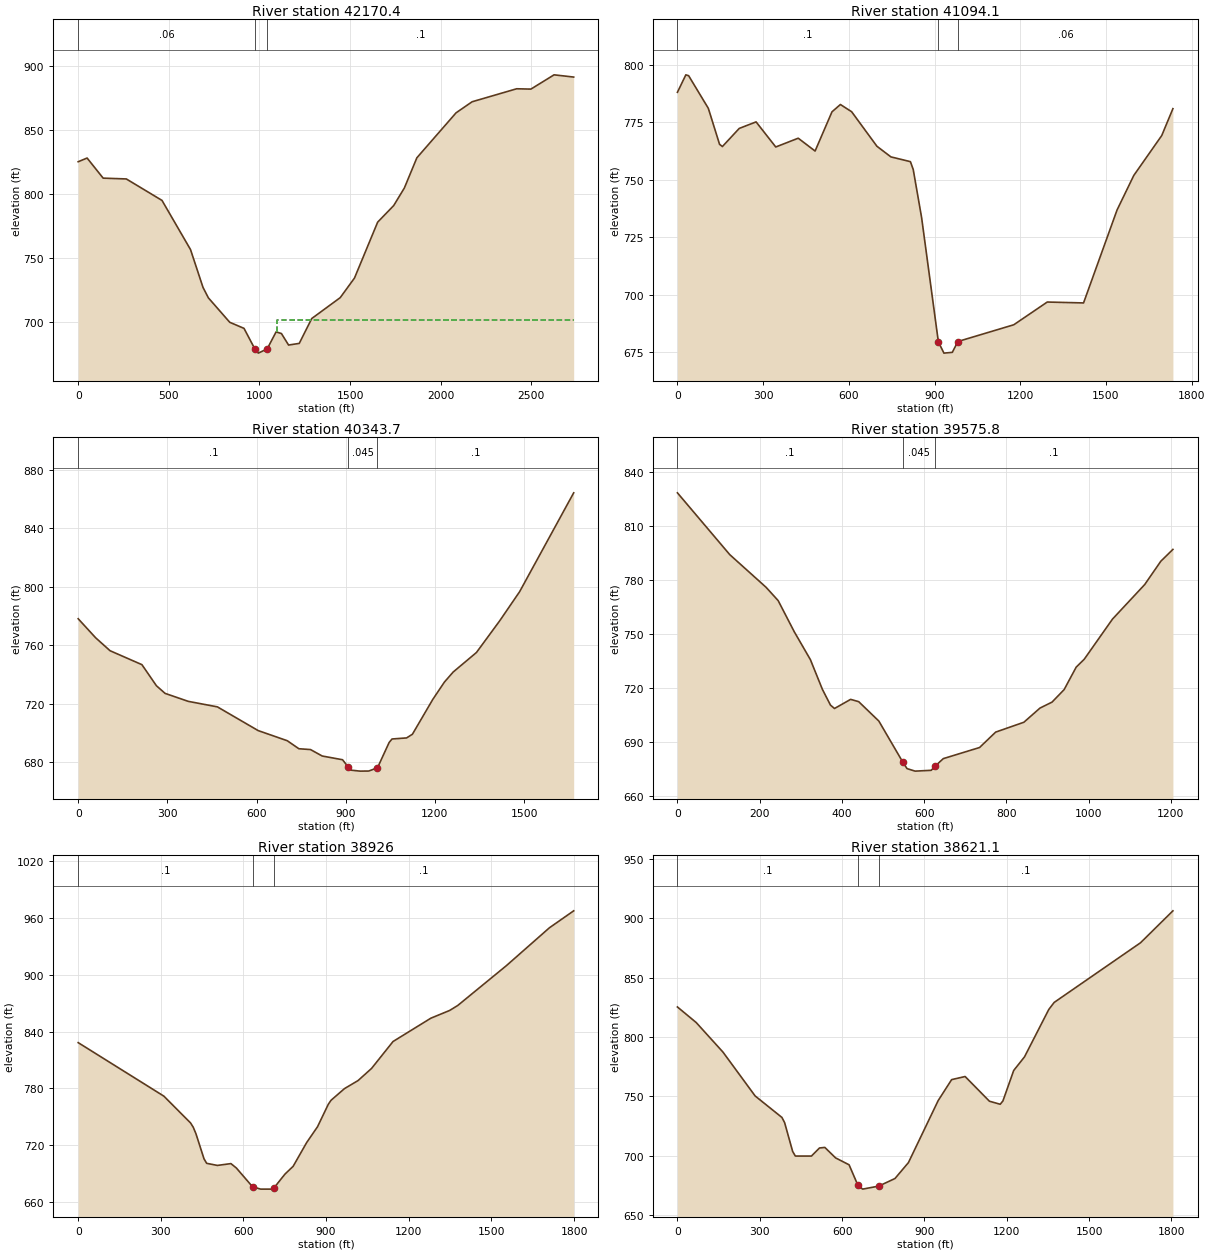
Type RM Length L Ch R = 1 ,42170.4 ,1078.3,1076.3,1073.3
XS GIS Cut Line= 3
      1466578.38      255277.243      1466640.88      256120.993
      1466015.88      257902.243
#Sta/Elev= 30
       0  825.23    49.2  828.11   137.7  812.43   265.6  811.79   462.4  795.05
   619.8  756.68   688.6   727.2   718.2  719.05   836.2  699.96   914.9  695.22
   973.9  679.39   993.5   675.9  1042.7  679.17  1091.9  692.47  1121.4  691.17
  1160.7  682.21  1219.7  683.49  1288.5  702.88  1445.8   719.2  1524.5   734.5
  1652.3  778.09  1740.8  791.03  1799.8   804.8  1868.6   828.3  2084.9  863.39
  2173.4  872.01  2419.2  882.15  2497.8  881.89  2625.6  893.03  2733.8  891.28
#Mann= 3 , 0 , 0
       0     .06       0   973.9    .045       0  1042.7      .1       0
#XS Ineff= 2 , 0
                         1096.51          701.79
Permanent Ineff=
       F       F
Bank Sta=973.9,1042.7
XS Rating Curve= 0 ,0
Exp/Cntr=0.3,0.1

Type RM Length L Ch R = 1 ,41094.1 ,752,750.4,748.3
XS GIS Cut Line= 3
     1466724.213      254933.493      1466078.38      255199.118
     1465849.213      256209.535
#Sta/Elev= 30
       0  788.04    29.5  795.65    39.3  795.26   108.2  781.07   147.5   765.4
   157.4  764.43   216.4  772.32   275.4  775.16   344.2  764.24   422.9  768.06
   481.9  762.47     541  779.54   570.5  782.73   609.8  779.59   698.3  764.56
   747.2  759.93   815.6  757.85   825.4  754.44   854.7  733.54   913.4  679.42
   932.9   674.5   962.2  674.84   981.8  679.56  1177.3  686.84  1294.6  696.74
  1421.6  696.35  1538.9  736.82  1597.6  751.88  1695.3  769.22  1734.4  780.92
#Mann= 3 , 0 , 0
       0      .1       0   913.4    .045       0   981.8     .06       0
Bank Sta=913.4,981.8
XS Rating Curve= 0 ,0
Exp/Cntr=0.3,0.1

Type RM Length L Ch R = 1 ,40343.7 ,778.6,768,755.9
XS GIS Cut Line= 4
     1465646.088      254709.535     1465424.915      255006.627
     1465277.345      256043.953     1465251.304      256291.349
#Sta/Elev= 30
       0  778.17    58.5   765.2   107.2  756.31   214.4  746.78   263.2  732.36
   292.4  727.14   370.4  721.69   468.3  717.93   605.4  701.72   703.3  694.79
   742.5   689.3   781.6  688.74   820.8  684.34   889.4  681.78     909  676.61
   918.8  674.64   948.1     674   977.5  674.07  1006.9  676.27    1046  693.56
  1055.8  695.97  1104.8   696.7  1124.4  699.23  1192.9  723.03  1232.1   734.9
  1261.5  741.75  1339.8   755.1  1418.2  776.81  1485.1  796.69  1666.9  864.25
#Mann= 3 , 0 , 0
       0      .1       0     909    .045       0  1006.9      .1       0
Bank Sta=909,1006.9
XS Rating Curve= 0 ,0
Exp/Cntr=0.3,0.1

Type RM Length L Ch R = 1 ,39575.8 ,649.7,649.7,648.1
XS GIS Cut Line= 2
     1464411.713      254923.077     1464844.005      256048.077
#Sta/Elev= 30
       0  828.65   127.4  794.26   215.6  776.13     245  768.73   284.2   751.4
   323.4  735.91   352.7  719.34   372.3   710.6   382.1  708.73   421.3   713.8
   440.9  712.53   489.9  701.75   548.7  678.72   558.5   675.3   578.1   673.9
   617.3  674.35   627.1  676.74   646.7  680.85   734.9  687.03   774.1   695.6
   842.7  701.08   881.8  708.95   911.2  712.28   940.6  719.23     970  731.74
   989.6  736.14  1058.2  758.43  1136.6  777.65  1175.8  790.62  1205.2   797.2
#Mann= 3 , 0 , 0
       0      .1       0   548.7    .045       0   627.1      .1       0
Bank Sta=548.7,627.1
XS Rating Curve= 0 ,0
Exp/Cntr=0.3,0.1

Type RM Length L Ch R = 1 ,38926   ,287.9,304.9,320.4
XS GIS Cut Line= 4
     1464057.546      255188.702     1464067.963       255693.91
      1464239.49      256101.285      1464569.88      256885.967
#Sta/Elev= 30
       0  828.28     311   771.9   408.1   743.6   417.9     739   427.6  732.21
   456.7  705.86   466.4  701.09   505.3  698.88   554.4   700.8   574.1  696.19
     633  676.36   662.5   673.9   701.8   673.9   711.6  675.52   750.9  689.81
   780.4  697.98   829.5  723.04   868.8  739.64     908  763.34   917.9  767.55
   966.9  779.88  1015.8  788.28  1064.8  801.05    1143  829.48  1280.1  854.03
  1348.6  862.22  1377.9  867.46  1554.1  909.34  1710.6  949.32  1798.7   967.2
#Mann= 3 , 0 , 0
       0      .1       0     633    .045       0   711.6      .1       0
Bank Sta=633,711.6
XS Rating Curve= 0 ,0
Exp/Cntr=0.3,0.1

Type RM Length L Ch R = 1 ,38621.1 ,407.8,435.5,462
XS GIS Cut Line= 3
     1464010.671      255183.493     1463897.137      255718.433
     1463554.255       256929.37
#Sta/Elev= 30
       0  825.32    68.4  812.21     166   787.3   283.2  750.36   380.8  732.27
   390.6  727.88   419.9  703.63   429.7  699.77   488.3  699.74   517.6  706.54
   537.1  707.03   576.4  698.19   625.5  692.39   656.8675.5747   674.7   671.9
   733.7  674.45   792.7  680.84   841.8  694.27     950  746.42   999.1  764.12
  1048.3  766.74  1136.8  745.94  1176.1  743.38    1186  746.16  1225.3  771.82
  1264.6  783.27  1353.1  823.19  1372.8  829.15  1687.4  879.39  1805.4  906.28
#Mann= 3 , 0 , 0
       0      .1       0   656.8    .045       0   733.7      .1       0
Bank Sta=656.8,733.7
XS Rating Curve= 0 ,0
Exp/Cntr=0.3,0.1

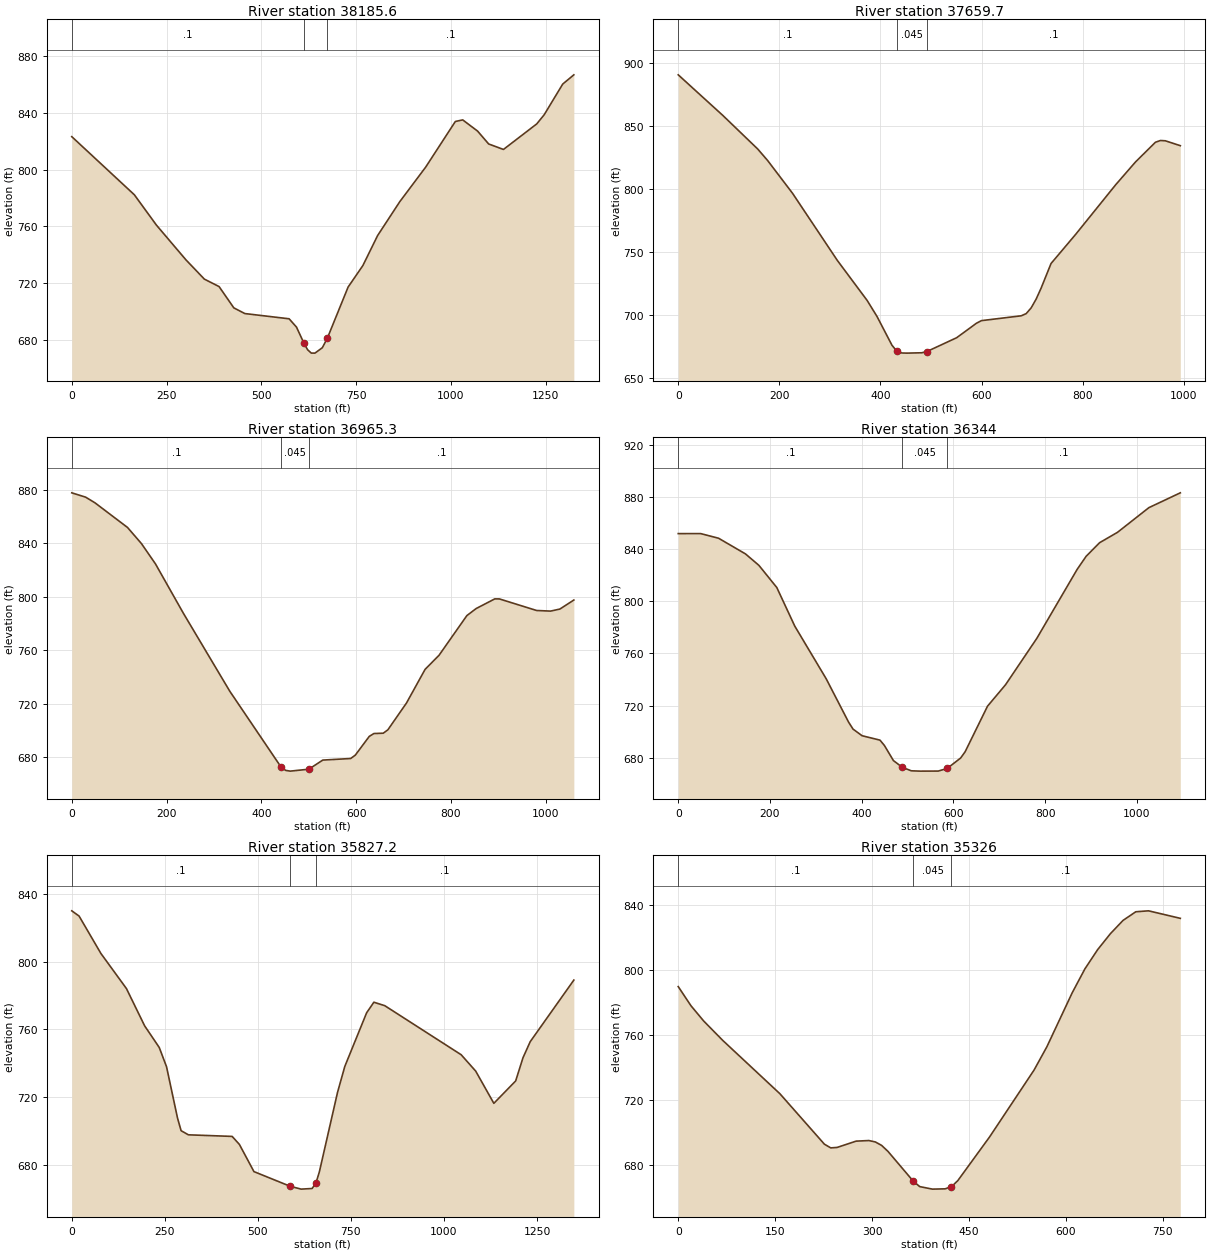
Type RM Length L Ch R = 1 ,38185.6 ,543.3,525.9,508
XS GIS Cut Line= 4
     1463988.283      255167.217     1463871.095      255557.842
     1463415.366      255592.565     1463063.804      255887.703
#Sta/Elev= 30
       0  823.32   165.1  782.29   223.3  760.89     301  736.42   349.6  722.81
   388.4  717.55   427.3  702.53   456.4   698.5   573.1  694.82   592.6  688.94
     612  677.72   621.8  673.01   631.5  670.63   641.2  670.59   660.7  674.41
     674 681.178   728.7  717.22   767.6  732.37   806.5  753.55   864.9  777.43
   933.2  801.82  1011.4  834.01  1030.9  835.14    1070  827.26  1099.3  818.16
  1138.3  814.29  1226.2  832.34  1245.8   838.8  1294.6  860.42  1323.9  866.94
#Mann= 3 , 0 , 0
       0      .1       0     612    .045       0     674      .1       0
Bank Sta=612,674
XS Rating Curve= 0 ,0
Exp/Cntr=0.3,0.1

Type RM Length L Ch R = 1 ,37659.7 ,713.1,694.4,675.5
XS GIS Cut Line= 2
      1463828.38       254756.41     1463177.338       255506.41
#Sta/Elev= 30
       0  890.56    88.5  858.23   157.3  831.66     177  822.48   226.2   796.5
   314.7   743.3   373.7  711.51   393.3  698.74   422.8  675.97   432.7   671.1
   442.5  669.81   452.3   669.7   481.8  669.98   491.7  670.93   550.7  681.91
     590  693.44   599.8  695.48   678.5  699.32   688.3  701.05   698.2  705.64
     708  712.56   717.8  721.24   737.5  740.82   786.7   764.2   865.3  803.29
   904.7  821.47     944  837.05   953.8  838.43   963.6  838.21   993.2  834.33
#Mann= 3 , 0 , 0
       0      .1       0   432.7    .045       0   491.7      .1       0
Bank Sta=432.7,491.7
XS Rating Curve= 0 ,0
Exp/Cntr=0.3,0.1

Type RM Length L Ch R = 1 ,36965.3 ,616.5,621.3,624.3
XS GIS Cut Line= 2
     1462807.546      254527.243     1462932.546      255579.327
#Sta/Elev= 30
       0  877.56    29.4  874.31      49  870.09   117.7  851.68   147.2  839.57
   176.6   824.5   235.4  787.68   333.5  729.35   441.4  672.87   451.3  670.25
   461.1   669.7   500.3  671.14   529.7  677.95   588.6  679.12   598.4  681.68
   627.8  695.64   637.6  697.78   657.3  698.02   667.1  700.58   706.3  720.54
   745.6   745.7     775  756.22   833.8  785.88   853.5  791.16   892.7  798.34
   902.5  798.31     981  789.67  1010.4  789.22    1030  790.74  1059.5  797.49
#Mann= 3 , 0 , 0
       0      .1       0   441.4    .045       0   500.3      .1       0
Bank Sta=441.4,500.3
XS Rating Curve= 0 ,0
Exp/Cntr=0.3,0.1

Type RM Length L Ch R = 1 ,36344   ,501.5,516.9,532.4
XS GIS Cut Line= 2
     1462302.338      254626.202     1462255.463      255719.952
#Sta/Elev= 30
       0   851.8    48.9  851.81      88  848.24   146.6  836.24   175.9  827.46
     215  810.43   254.1  780.88   322.6  740.52   371.4  707.31   381.2  701.91
   400.8  696.85   439.9  693.46   449.6  689.36   469.2   677.8   488.7  672.59
   508.3  669.94   527.8   669.7   566.9  669.74   586.5  671.76   615.8  679.75
   625.6  684.55   674.4  719.48   713.6  735.88     782  771.54   869.9  824.39
   889.5  834.42   918.8  844.82   957.9  852.79  1026.3   871.7  1094.8  883.06
#Mann= 3 , 0 , 0
       0      .1       0   488.7    .045       0   586.5      .1       0
Bank Sta=488.7,586.5
XS Rating Curve= 0 ,0
Exp/Cntr=0.3,0.1

Type RM Length L Ch R = 1 ,35827.2 ,480.8,501.2,519.4
XS GIS Cut Line= 3
     1462239.838      254615.785      1461953.38      254897.035
     1461312.755      255594.952
#Sta/Elev= 30
       0  830.09    19.6  827.01    78.3   804.9   146.9  784.16   195.8  762.14
     235  749.38   254.6  737.99     284  707.77   293.7  700.22   313.3  697.78
   430.8  696.84   450.3  692.12   489.4  676.05     587  667.36   616.3   665.7
   645.6  666.07   655.8669.1486   665.2  675.93     714  722.89   733.5  738.17
   792.1  769.85   811.6  776.11   840.9  774.06    1046   745.1  1085.1  735.42
  1133.9  716.38  1192.5   729.6  1212.1  743.25  1231.6   752.8  1348.8  789.18
#Mann= 3 , 0 , 0
       0      .1       0     587    .045       0   655.8      .1       0
Bank Sta=587,655.8
XS Rating Curve= 0 ,0
Exp/Cntr=0.3,0.1

Type RM Length L Ch R = 1 ,35326   ,223.4,221.9,220.9
XS GIS Cut Line= 2
     1462166.921      254636.618      1461390.88      254594.952
#Sta/Elev= 30
       0  789.95    19.7  778.17    39.4  768.78    68.9  756.86   157.4  724.06
   226.3  693.03   236.1  690.77   245.9  691.04   275.4  694.92   295.1  695.28
     305  694.43   314.8  692.31   324.6  688.65     364  670.22   373.8  666.97
   393.5  665.41   413.2  665.59     423  666.91   432.8  670.65     482  697.52
   550.9  738.68   570.6   752.9   609.9  786.17   629.6  800.89   649.3   812.7
     669  822.48   688.6  830.66   708.3  835.95     728  836.53   777.2  831.91
#Mann= 3 , 0 , 0
       0      .1       0     364    .045       0     423      .1       0
Bank Sta=364,423
XS Rating Curve= 0 ,0
Exp/Cntr=0.3,0.1

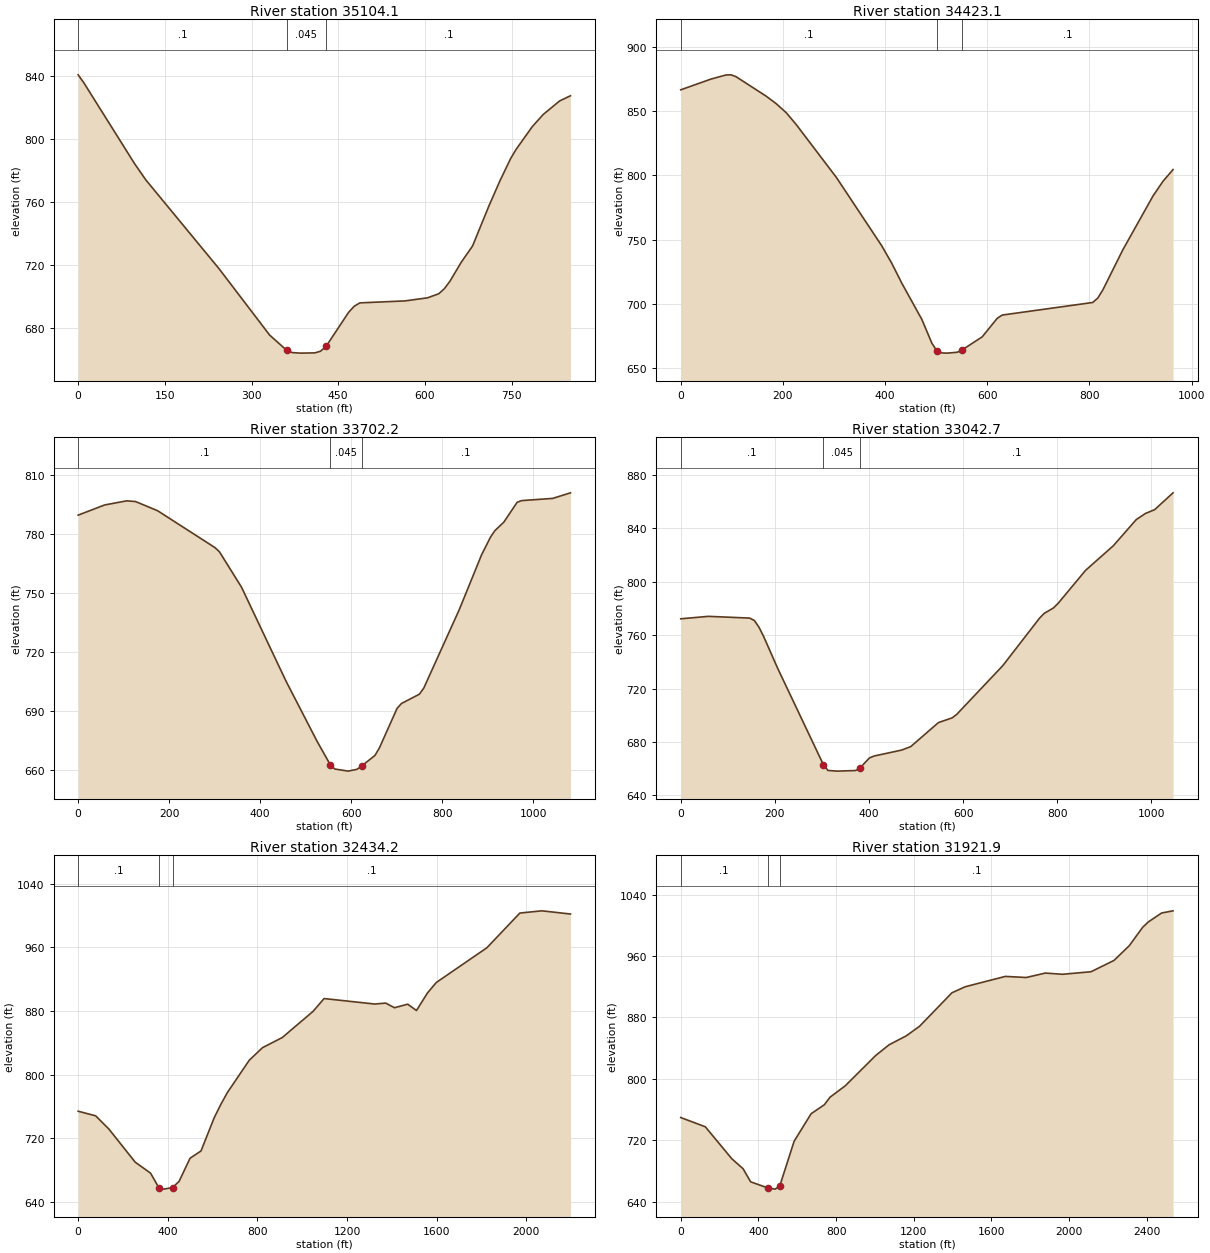
Type RM Length L Ch R = 1 ,35104.1 ,715.6,681,645.9
XS GIS Cut Line= 3
     1462224.213      254397.035     1461541.921      254407.452
      1461422.13      254527.243
#Sta/Elev= 30
       0  840.46     9.8  835.42    97.5  784.17     117  773.84   243.7  717.49
   331.4   675.3   360.7  665.73   370.4  664.23   385.1   663.9   409.4  664.06
   419.2  665.08   428.9  668.13   467.9  689.77   477.7  693.65   487.4  695.78
   565.4  697.02   604.4  698.98   623.9  701.55   633.6  704.78   643.4  709.58
   662.9  721.62   682.4  731.86   710.6  757.18   729.4  772.91   748.2  787.28
   757.7  793.15   785.9  807.66   804.7  815.32     833  823.88   851.8  827.18
#Mann= 3 , 0 , 0
       0      .1       0   360.7    .045       0   428.9      .1       0
Bank Sta=360.7,428.9
XS Rating Curve= 0 ,0
Exp/Cntr=0.3,0.1

Type RM Length L Ch R = 1 ,34423.1 ,727.8,721,713
XS GIS Cut Line= 2
     1461432.546      253501.202      1461422.13      254464.743
#Sta/Elev= 30
       0  866.66      59  874.99    88.5   878.2    98.3  878.32   108.2  876.88
   167.2  861.72   186.8   855.9   206.5  848.83   226.2  839.55   304.8   798.4
   393.3  745.38     413   731.7   432.6  716.28     472  687.97   491.6  669.47
   501.5  663.51   511.3  661.96   521.1  661.81   540.8  662.45   550.6  664.28
     590  674.45   619.5  688.92   629.3  691.43   806.3  701.21   816.1  704.56
   825.9   710.8   865.3  742.17   924.3  784.04   943.9  795.52   963.6  804.61
#Mann= 3 , 0 , 0
       0      .1       0   501.5    .045       0   550.6      .1       0
Bank Sta=501.5,550.6
XS Rating Curve= 0 ,0
Exp/Cntr=0.3,0.1

Type RM Length L Ch R = 1 ,33702.2 ,668.3,659.5,650.5
XS GIS Cut Line= 3
       1460559.5      253618.606     1460663.666      253962.356
     1460887.625      254649.856
#Sta/Elev= 30
       0  789.67    58.2  794.86   106.8  796.96   126.2  796.59   174.7  791.92
   300.9  773.12   310.6  771.01   359.2  752.95   456.9  705.16   525.3  674.47
   554.6  662.43   564.4  660.38   593.7  659.32   613.2  660.26     623   661.9
   652.3  667.28   662.1  671.09   701.2  691.34   710.9  693.79     750  698.48
   759.8  701.63     838  741.67   886.8  769.47   906.4  778.46   916.1  781.79
   935.7   786.1     965  796.23   974.8  797.08  1043.2   798.2  1082.2  801.04
#Mann= 3 , 0 , 0
       0      .1       0   554.6    .045       0     623      .1       0
Bank Sta=554.6,623
XS Rating Curve= 0 ,0
Exp/Cntr=0.3,0.1

Type RM Length L Ch R = 1 ,33042.7 ,607,608.4,609
XS GIS Cut Line= 2
     1459933.198      254211.054     1460618.961      255000.985
#Sta/Elev= 30
       0  772.22    58.7  774.06   146.6  772.75   156.4  770.95   166.2  765.95
     176  759.09   205.3  735.63   303.1  662.92   312.8  658.61   332.4   658.1
   371.5  658.54   381.3  660.64   400.8  667.93   410.6   669.4   469.3  673.87
   488.8   676.5   547.5  694.45   576.8  698.02   586.6  700.68   684.3  737.13
   762.6   772.8   772.3  776.28   791.9  780.34   801.7  783.73   860.3  808.56
     919  826.89   967.9  846.55   987.4  851.14    1007  853.99  1046.1   866.6
#Mann= 3 , 0 , 0
       0      .1       0   303.1    .045       0   381.3      .1       0
Bank Sta=303.1,381.3
XS Rating Curve= 0 ,0
Exp/Cntr=0.3,0.1

Type RM Length L Ch R = 1 ,32434.2 ,491,512.3,533.3
XS GIS Cut Line= 3
     1459575.559      254657.235     1460011.399      255198.734
     1460698.352      256534.405
#Sta/Elev= 30
       0  754.17    78.3  748.37   137.1  731.79   254.6  690.17   323.1  676.38
   362.2  657.11   381.8   656.3   421.1658.2568   450.4     666   499.3  695.07
   548.3  704.29     607  745.88   636.4  762.52   665.7  777.53   763.8  818.26
   822.7  833.99   911.1  846.75  1048.5  879.64  1097.6   895.7  1323.4  888.82
  1372.5     890  1411.7  884.16  1470.6  888.65  1509.9  880.68    1559  902.72
  1598.3  915.87    1824  959.47  1971.3  1003.1  2069.5  1005.9  2197.1 1001.89
#Mann= 3 , 0 , 0
       0      .1       0   362.2    .045       0   421.1      .1       0
Bank Sta=362.2,421.1
XS Rating Curve= 0 ,0
Exp/Cntr=0.3,0.1

Type RM Length L Ch R = 1 ,31921.9 ,373.6,378.5,382.6
XS GIS Cut Line= 3
     1459513.059      254667.651     1459307.267      255438.499
     1458059.463      256647.252
#Sta/Elev= 30
       0  749.45   126.5  737.42   262.7  695.83   321.1  682.71     360   665.7
   447.6   657.8   486.5   656.2   510.1660.4938   583.8  718.58   671.4  754.45
   739.5  766.14   768.7  775.97   846.9  790.75    1004  830.32  1072.7  844.22
    1161  855.83  1229.7  868.33  1396.6  912.01  1465.3  919.88  1671.4  933.31
  1779.4  931.89  1877.5  937.66  1965.8  936.07  2113.1  939.42  2230.8  954.09
  2309.4  973.25  2378.1  997.12  2407.5 1004.24  2476.2 1015.91  2535.1 1018.74
#Mann= 3 , 0 , 0
       0      .1       0   447.6    .045       0   510.1      .1       0
Bank Sta=447.6,510.1
XS Rating Curve= 0 ,0
Exp/Cntr=0.3,0.1