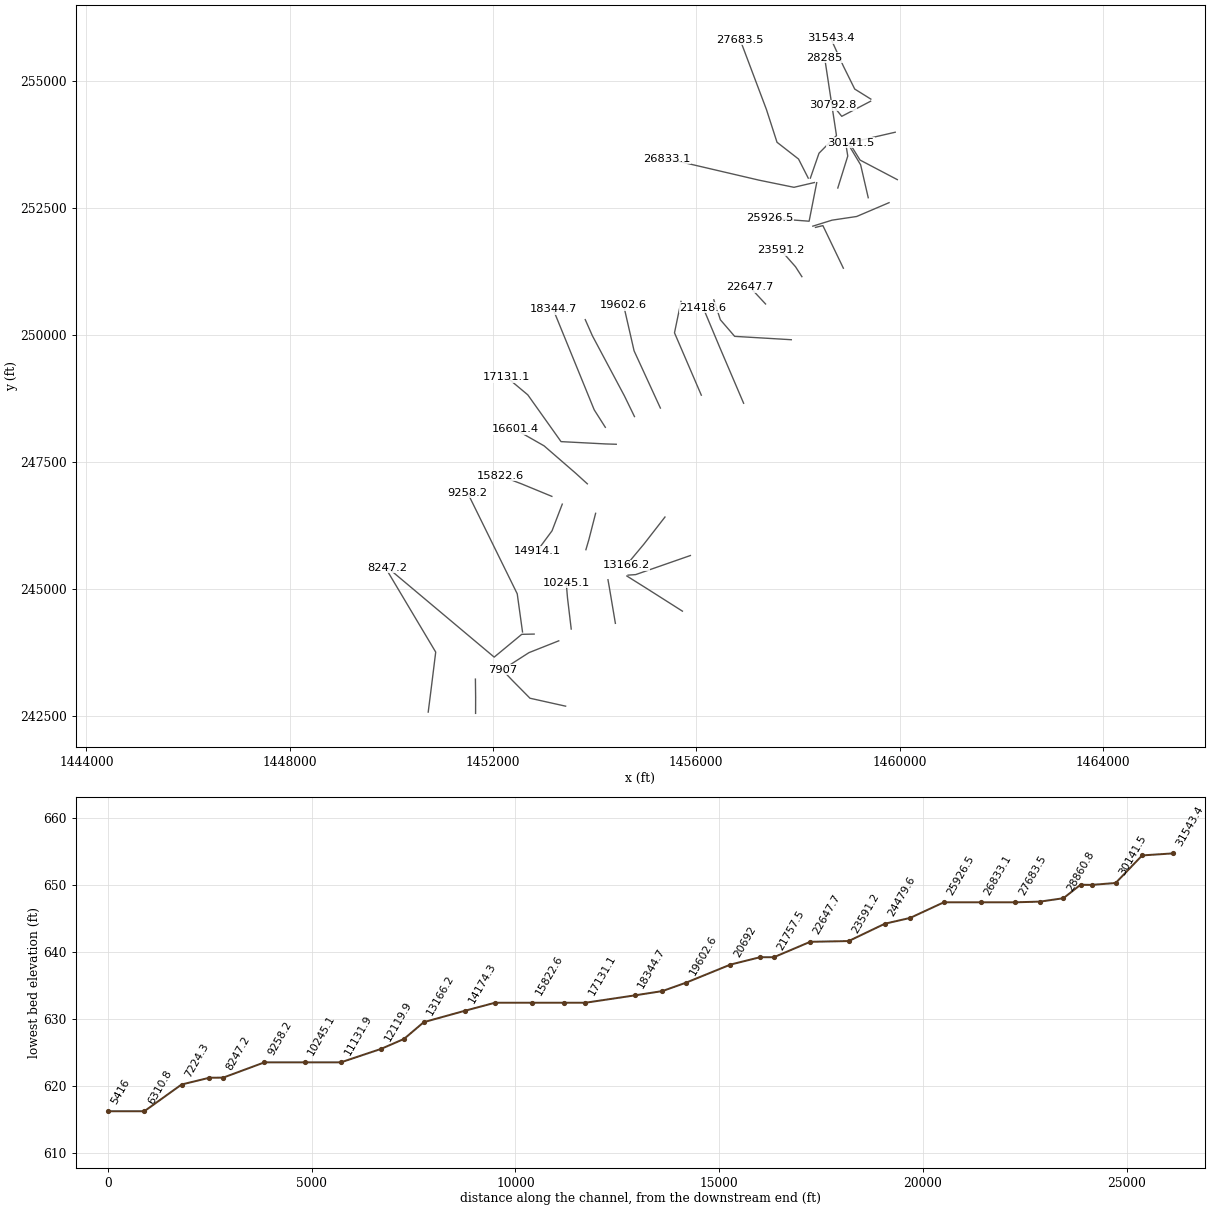
HEC-RAS study GSCR.prj: GSCR

--- GSCR.g01 (geometry) --- (continued)

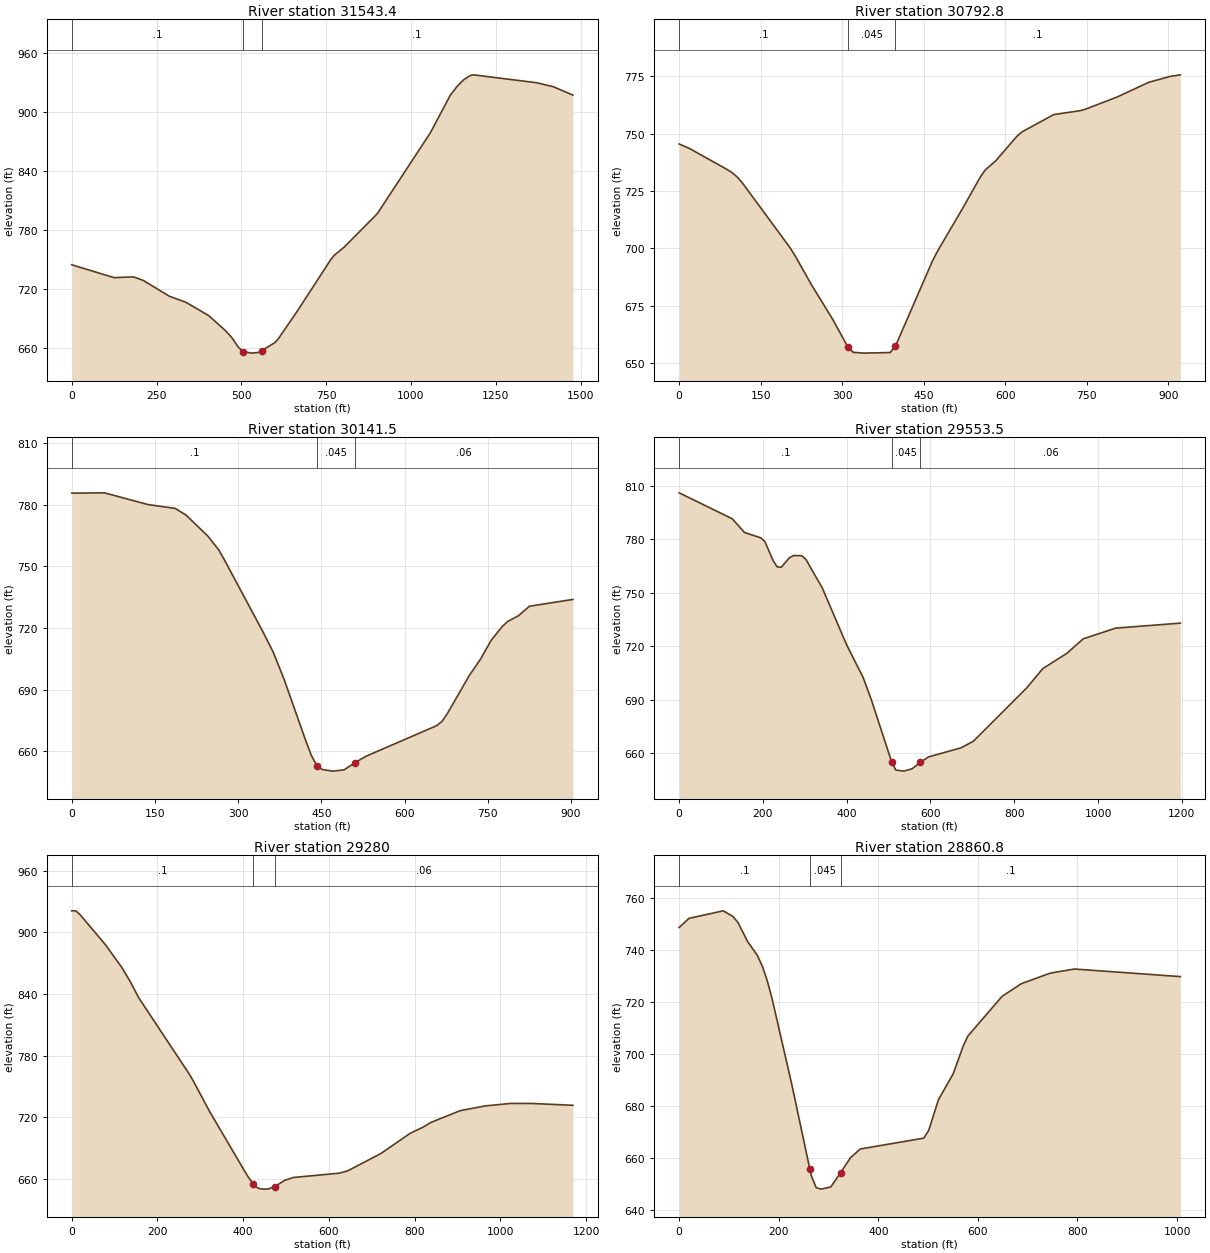
Type RM Length L Ch R = 1 ,31543.4 ,713.4,750.6,785.9
XS GIS Cut Line= 4
     1459434.934      254636.401     1459117.225      254834.318
     1458891.966      255288.333     1458645.401       255831.28
#Sta/Elev= 30
       0  744.64   124.8  731.53   182.4  732.32   211.2  728.66   287.9  712.57
   335.9  706.59   403.6  692.94   452.3  677.92   471.8  670.61   491.3  660.65
   505.9  656.26   530.3   654.7   549.8  655.34   559.5  657.04   598.5   665.3
   608.2  668.91   666.7  698.39   764.2  750.24   773.9  754.33   803.2  762.62
   900.7  796.58  1057.1  878.92  1115.8  917.14  1135.3  925.89  1154.8   932.8
  1174.4  937.22  1184.2  937.97  1369.9  929.94  1418.8  925.96  1477.4  917.39
#Mann= 3 , 0 , 0
       0      .1       0   505.9    .045       0   559.5      .1       0
Bank Sta=505.9,559.5
XS Rating Curve= 0 ,0
Exp/Cntr=0.3,0.1

Type RM Length L Ch R = 1 ,30792.8 ,657,651.4,645.3
XS GIS Cut Line= 3
     1459429.725      254594.735     1458862.017       254297.86
     1458684.934       254516.61
#Sta/Elev= 30
       0  745.51    19.4  743.49    87.4   734.5    97.1  733.08   106.8  731.12
   116.5  728.48   203.8   700.4   213.6   696.7   242.7  684.47   281.5  669.51
   310.6  656.99   320.3  654.75   339.7   654.4   388.3  654.66     398  657.49
   465.9  694.49   475.6  698.92   524.2  718.53   553.3  730.82     563  734.18
   582.4  738.16   621.2  748.82   630.9  750.79   689.2  758.32   737.7  760.01
   747.4  760.65   805.6  765.95   863.9  772.36   902.7  774.91   922.1  775.63
#Mann= 3 , 0 , 0
       0      .1       0   310.6    .045       0     398      .1       0
Bank Sta=310.6,398
XS Rating Curve= 0 ,0
Exp/Cntr=0.3,0.1

Type RM Length L Ch R = 1 ,30141.5 ,604.1,588,571.6
XS GIS Cut Line= 2
       1459914.1       253985.36     1459033.892      253782.235
#Sta/Elev= 30
       0  785.74    58.9   785.9   137.5  780.18   186.6   778.3   206.2  775.02
   245.5  764.78   265.1  758.04   274.9  753.37   343.7  718.65   363.3  708.19
   382.9   694.9   422.2  664.81     432  657.86   441.8  652.97   451.7  651.03
   471.3  650.28     491  650.93   510.6  654.38   530.2  657.51   657.9  672.45
   667.7  674.63   677.5  678.56   716.8  696.98   736.4   704.7   756.1  714.09
   775.7  720.69   785.5  723.18   805.2  726.02   824.8  730.62   903.3  733.96
#Mann= 3 , 0 , 0
       0      .1       0   441.8    .045       0   510.6     .06       0
Bank Sta=441.8,510.6
XS Rating Curve= 0 ,0
Exp/Cntr=0.3,0.1

Type RM Length L Ch R = 1 ,29553.5 ,292.7,273.5,254
XS GIS Cut Line= 3
     1459955.767      253053.068     1459221.392      253438.485
     1459028.684      253750.985
#Sta/Elev= 30
       0  806.04   126.8  791.48   156.1  783.79   195.2  780.78   204.9   778.6
   224.4  767.98   234.2   764.5   243.9  764.36   263.4  769.69   273.2  770.88
   292.7  770.79   302.5  768.75   341.5  752.78     400  720.72   439.1  702.56
   458.6  690.16   507.4  655.08   517.1  650.61   536.6     650   556.2  651.33
   575.7   654.9   595.2  657.96   673.2  663.09   702.5  666.78   829.4  696.59
     868  707.45     926  716.13   964.6  724.18  1041.9  730.17  1196.5  732.99
#Mann= 3 , 0 , 0
       0      .1       0   507.4    .045       0   575.7     .06       0
Bank Sta=507.4,575.7
XS Rating Curve= 0 ,0
Exp/Cntr=0.3,0.1

Type RM Length L Ch R = 1 ,29280   ,431,419.1,407.2
XS GIS Cut Line= 3
     1459383.284      252697.599     1459233.979      253343.433
     1458973.562       253777.46
#Sta/Elev= 30
       0  920.77     9.8  920.76    19.5  917.02      78  888.15     117  865.58
   136.5  851.98     156   836.4     273  762.69   282.7  755.94   321.7  725.48
   409.4  663.28   423.4654.9699   428.9  652.39   438.7  650.41   448.4  650.02
   458.2  650.15   473.4652.4944   497.2  658.62   516.6  661.34   623.9  665.52
   643.4  667.73   721.3   684.7   789.4  704.33   818.6  710.12   838.1  714.95
   906.2  726.38   964.6  730.98    1023  733.36  1071.7  733.39    1169  731.58
#Mann= 3 , 0 , 0
       0      .1       0   423.4    .045       0   473.4     .06       0
Bank Sta=423.4,473.4
XS Rating Curve= 0 ,0
Exp/Cntr=0.3,0.1

Type RM Length L Ch R = 1 ,28860.8 ,576,575.8,574.5
XS GIS Cut Line= 3
      1458784.29      252888.571     1458980.507      253517.044
     1458924.951      253860.794
#Sta/Elev= 30
       0  748.75    19.6  752.26    88.4  755.17   108.1  752.99   117.9  750.72
   137.6   743.3   157.2  737.96     167  733.87   176.9  728.27   186.7  721.27
     226  688.52   262.6655.5684   265.3  653.29   275.2  648.56     285  648.01
   304.6  648.87   324.3  654.38   343.9  660.07   363.6  663.46   491.3  667.64
   501.2  670.62   520.8  682.46   550.3  692.39     570  702.86   579.8  706.94
   648.6  722.26   687.4  727.13   745.4  731.18   793.8  732.76  1006.6  729.84
#Mann= 3 , 0 , 0
       0      .1       0   262.6    .045       0   324.3      .1       0
Bank Sta=262.6,324.3
XS Rating Curve= 0 ,0
Exp/Cntr=0.3,0.1

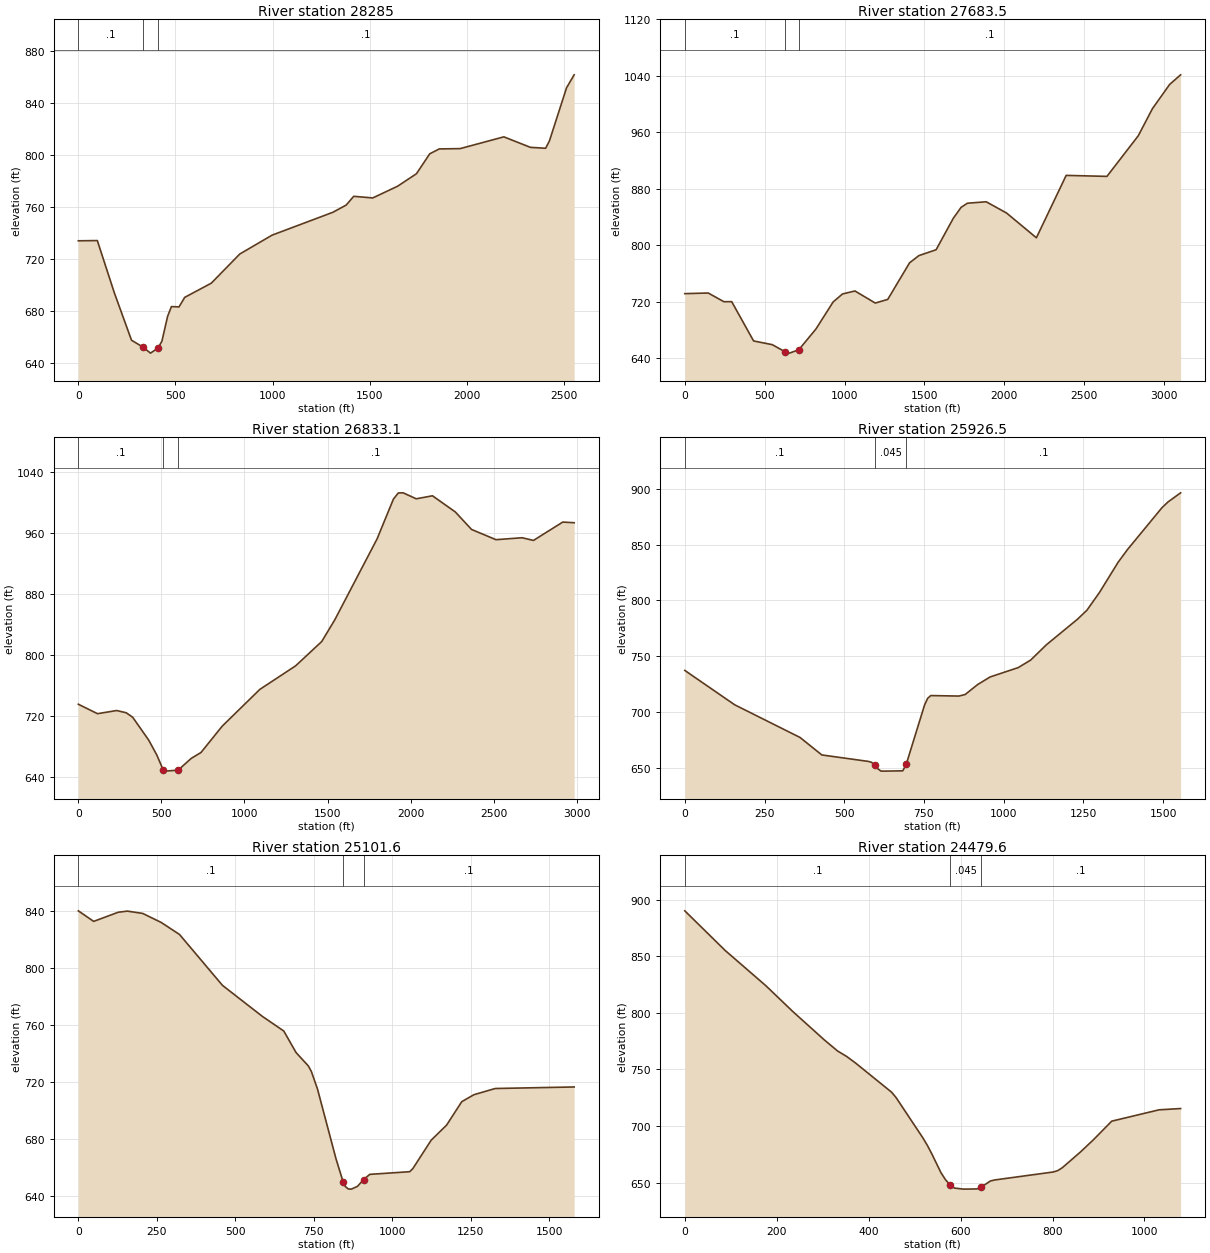
Type RM Length L Ch R = 1 ,28285   ,571.1,601.6,629.6
XS GIS Cut Line= 4
     1458244.395      253083.016     1458414.534      253572.599
     1458758.284      253919.821     1458525.645      255447.599
#Sta/Elev= 30
       0  734.04    97.8  734.22   185.8  693.76   273.8  657.43   332.5  652.17
   371.6   647.5   410.7  651.46   430.3  656.74   459.6  675.86   479.2  683.35
   518.3  683.11   547.6  690.46   684.4  701.39     831  723.85   997.1  738.39
  1310.1     756  1378.6  761.55  1417.7  768.32  1515.5  767.06  1642.7  776.03
  1740.5  785.71  1808.9  801.06  1857.8  804.83  1965.4  805.07  2190.4  814.13
  2327.3  806.04  2405.6  805.35  2425.1  811.04  2513.2  851.96  2552.3  861.92
#Mann= 3 , 0 , 0
       0      .1       0   332.5    .045       0   410.7      .1       0
Bank Sta=332.5,410.7
XS Rating Curve= 0 ,0
Exp/Cntr=0.3,0.1

Type RM Length L Ch R = 1 ,27683.5 ,841.1,850.3,857.4
XS GIS Cut Line= 5
     1458202.729      253083.016     1458011.757      253458.016
     1457588.145      253787.877     1457381.022      254428.973
     1456861.583      255806.106
#Sta/Elev= 30
       0  731.64   146.8  732.54   244.7  720.23   293.6  720.31   430.6  664.66
   547.7  659.37   625.8  649.54   655.1   647.4   713.7   652.2   821.1  681.66
   928.4  719.86     987  731.19  1065.1  735.43  1192.1  718.31  1270.2   723.5
  1406.9  775.37  1465.4  785.56  1572.9  793.82  1680.5  838.38  1729.6  853.92
  1768.8  859.73  1886.6  861.77  2014.1  845.81  2200.6  810.76    2387  899.15
  2642.1  897.73  2838.4  955.32  2926.7  993.59  3034.6 1027.99  3103.3 1041.58
#Mann= 3 , 0 , 0
       0      .1       0   625.8    .045       0   713.7      .1       0
Bank Sta=625.8,713.7
XS Rating Curve= 0 ,0
Exp/Cntr=0.3,0.1

Type RM Length L Ch R = 1 ,26833.1 ,870.6,906.6,942.2
XS GIS Cut Line= 4
     1458324.257       252996.21     1457921.479       252902.46
     1457236.952      253042.288     1455413.666      253467.565
#Sta/Elev= 30
       0  735.27   115.4  722.83   230.8  726.98   288.5  724.02     327   718.2
   423.4  688.22   472.6   668.5     512   648.3   521.8   647.4   600.5  648.67
   679.2  664.05   738.3  671.87   866.2   706.5  1092.5  754.74  1308.2  785.73
  1465.1  817.62  1543.5  846.07  1798.4  952.47  1896.4 1004.56  1925.8 1012.71
  1955.2 1012.88  2033.6 1005.02  2131.6 1008.99  2268.9  987.82  2366.9  964.77
  2513.9  951.34  2670.8   953.9  2739.4  950.36  2915.8  974.47  2984.4   973.6
#Mann= 3 , 0 , 0
       0      .1       0     512    .045       0   600.5      .1       0
Bank Sta=512,600.5
XS Rating Curve= 0 ,0
Exp/Cntr=0.3,0.1

Type RM Length L Ch R = 1 ,25926.5 ,851.9,824.9,795.5
XS GIS Cut Line= 3
     1458369.395      252992.738      1458220.09      252235.794
      1457438.84      252294.821
#Sta/Elev= 30
       0  737.46   156.3  706.75   361.4  677.51   429.7  661.88   576.2  656.07
     586  655.23   595.7  652.73   605.5  649.45   615.3  647.47     625   647.4
   683.6  647.67   694.6653.6108     752  706.62   761.8  712.56   771.5  714.97
   859.7  714.53   879.3  715.93   918.4  724.82   957.6  731.62  1045.8  739.99
  1084.9  746.76  1133.9  760.36  1231.8  783.32  1261.2  791.31  1300.4  807.13
  1359.1  834.23  1388.5   845.6  1496.2  882.88  1515.8   888.2    1555  896.28
#Mann= 3 , 0 , 0
       0      .1       0   595.7    .045       0   694.6      .1       0
Bank Sta=595.7,694.6
XS Rating Curve= 0 ,0
Exp/Cntr=0.3,0.1

Type RM Length L Ch R = 1 ,25101.6 ,650.4,622,592.7
XS GIS Cut Line= 4
     1459793.007      252600.377     1459155.295       252328.57
     1458671.479      252256.627     1458293.007      252138.571
#Sta/Elev= 30
       0  840.06    48.8  832.66   126.9  839.06   156.2  839.86     205  838.24
   263.6  831.95   322.2  823.49   458.9  787.85   585.8  766.14   654.2  755.85
   693.2  740.78   732.4  731.39   742.1  727.48   761.7  715.09   820.4  666.39
   843.1650.2051   849.7  646.98   859.5  645.19   869.3  645.07   888.9  647.02
   908.4  651.79     928  655.41  1055.2  657.29    1065  659.42  1123.7   679.4
  1172.6  689.92    1221  706.37  1259.7  711.23  1327.4  715.57  1578.8  716.65
#Mann= 3 , 0 , 0
       0      .1       0   843.1    .045       0   908.4      .1       0
Bank Sta=843.1,908.4
XS Rating Curve= 0 ,0
Exp/Cntr=0.3,0.1

Type RM Length L Ch R = 1 ,24479.6 ,881.8,888.4,894.3
XS GIS Cut Line= 3
     1458893.701      251312.183     1458490.923      252148.988
      1458345.09      252114.266
#Sta/Elev= 30
       0  890.06      88  854.98     176  824.03   234.6  801.24     303  776.21
   332.4  766.22   351.9  761.46   371.5  755.59   449.7  729.89   459.5  725.14
   518.1  689.38   527.9  682.69   537.7  675.08   557.2  658.78     567  652.59
   576.8  648.06   586.5  645.14   606.1   644.2   635.4  644.37   645.2  646.05
   664.8   651.4   674.5  652.32   801.6  659.34   811.4  660.58   821.2   663.1
   860.3  676.86   889.6  688.09   928.7  704.24  1031.8  714.27  1078.6  715.39
#Mann= 3 , 0 , 0
       0      .1       0   576.8    .045       0   645.2      .1       0
Bank Sta=576.8,645.2
XS Rating Curve= 0 ,0
Exp/Cntr=0.3,0.1

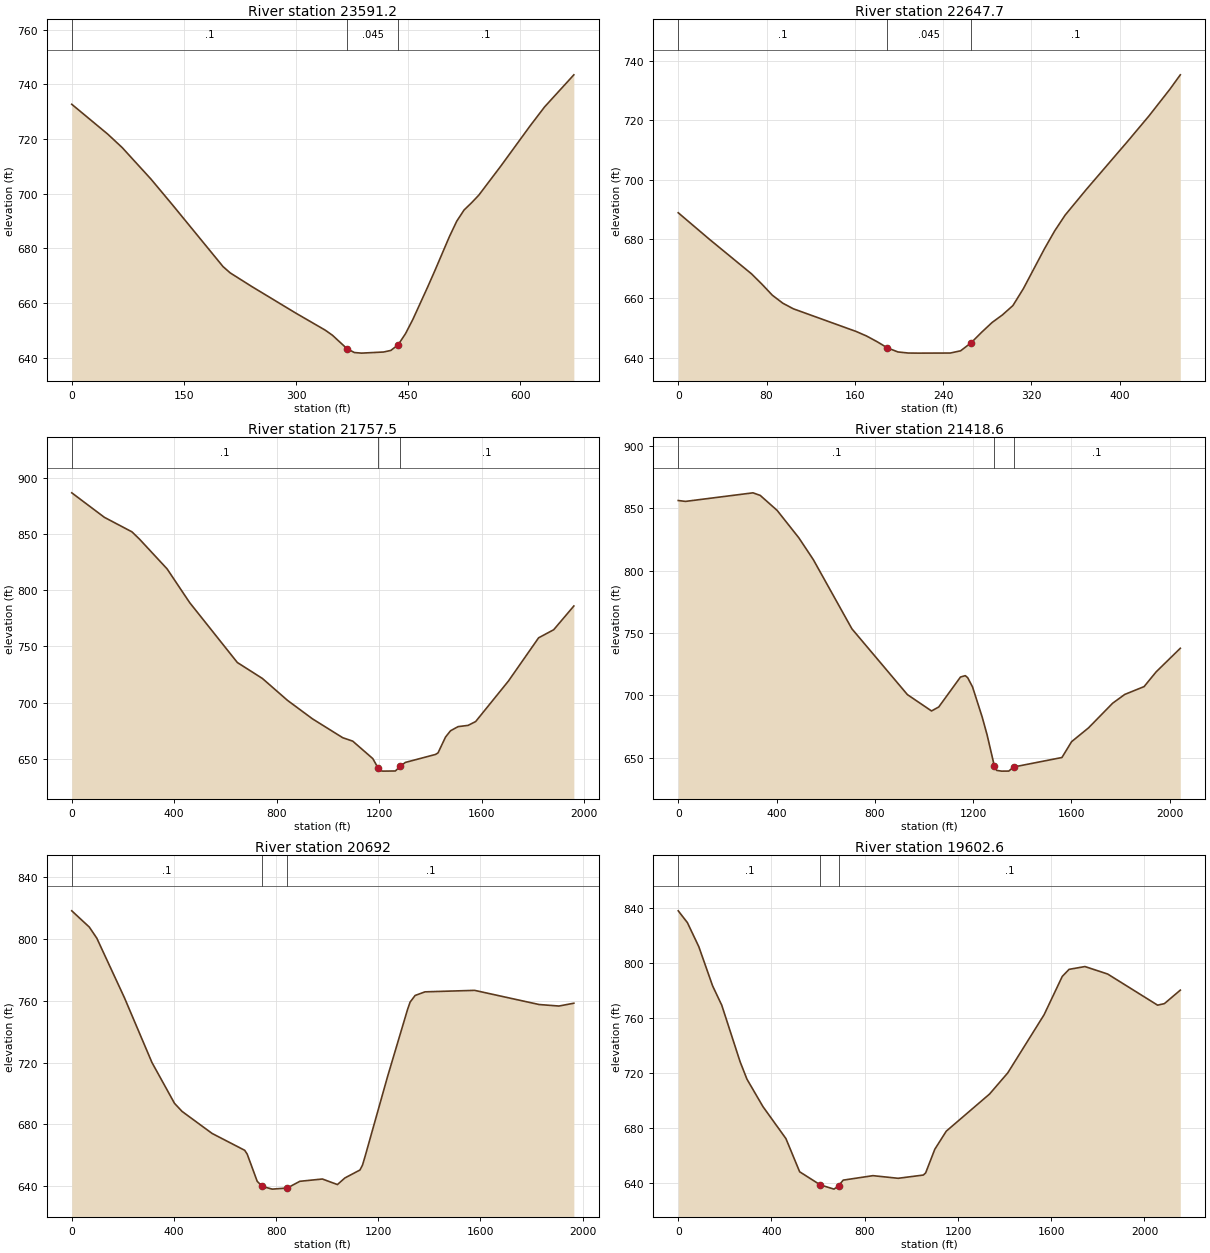
Type RM Length L Ch R = 1 ,23591.2 ,942.9,943.6,944
XS GIS Cut Line= 3
     1458077.729      251145.516     1457952.729       251339.96
     1457661.062      251669.821
#Sta/Elev= 30
       0  732.67    48.2  721.73    67.4  716.84     106  705.27   134.8  695.84
   202.3  673.28   211.9  670.97   240.9  665.96   299.6  656.26   338.8  650.05
   348.6  648.16   368.1  643.25   377.9  641.83   387.7  641.61   417.1  642.02
   426.8   642.6   436.6  644.69   446.4  648.75   456.2  653.95   475.8  665.69
   485.6  671.77   505.1  684.26   514.9   689.9   524.7  693.99   534.5  696.57
   544.3  699.39   573.6  709.97   612.8  724.69   632.3  731.69   671.5  743.45
#Mann= 3 , 0 , 0
       0      .1       0   368.1    .045       0   436.6      .1       0
Bank Sta=368.1,436.6
XS Rating Curve= 0 ,0
Exp/Cntr=0.3,0.1

Type RM Length L Ch R = 1 ,22647.7 ,890.7,890.2,888.9
XS GIS Cut Line= 3
     1457362.587      250608.591     1457207.673      250775.198
     1457052.758      250941.804
#Sta/Elev= 30
       0   688.8    28.4  679.82    66.4  668.22    75.8  664.76    85.3  661.01
    94.8  658.32   104.3  656.44   161.2   648.8   170.6  647.28   180.1  645.38
   189.6  643.26   199.1   641.9   208.5  641.53     218   641.5   246.5  641.53
   255.9  642.28   265.4  644.98   274.9  648.51   284.4  651.82   293.8  654.38
   303.3  657.53   312.8  663.24   331.8   676.6   341.2  682.72   350.7  688.04
   369.7   696.6   407.6  713.01   426.6  721.43   445.5   730.4     455  735.28
#Mann= 3 , 0 , 0
       0      .1       0   189.6    .045       0   265.4      .1       0
Bank Sta=189.6,265.4
XS Rating Curve= 0 ,0
Exp/Cntr=0.3,0.1

Type RM Length L Ch R = 1 ,21757.5 ,345.7,339,331.5
XS GIS Cut Line= 4
     1457869.395      249905.933     1456754.812      249971.905
     1456473.562      250298.294      1456345.09      250690.655
#Sta/Elev= 30
       0  886.56   127.3  864.79   235.1  851.86   264.4   845.4   372.2  818.96
   460.3  788.98   646.4  735.75   744.4  721.54   842.3  702.08   940.2   685.6
  1057.8  668.91    1097  665.84  1175.3  650.33  1194.9  642.42  1204.7  639.61
  1214.4   639.2  1263.4  639.33    1283  643.65  1302.6  646.95  1420.1  654.03
  1429.9   655.4  1459.3  669.52  1478.8  675.08  1508.2  678.74  1547.4  679.86
  1576.9  683.28  1704.7  719.24  1822.6  757.68  1881.6  764.88  1960.2  785.97
#Mann= 3 , 0 , 0
       0      .1       0  1194.9    .045       0    1283      .1       0
Bank Sta=1194.9,1283
XS Rating Curve= 0 ,0
Exp/Cntr=0.3,0.1

Type RM Length L Ch R = 1 ,21418.6 ,725.2,726.6,725.6
XS GIS Cut Line= 3
     1456930.991      248656.801     1456456.201      249767.044
     1456133.284      250537.877
#Sta/Elev= 30
       0  856.21    29.4  855.49   304.3  862.37   333.8  860.28   402.5  848.27
   490.9  826.26   549.8  808.78   706.8   753.3   932.6  700.56  1030.8  687.45
  1060.2  690.66  1148.6  714.65  1168.2  715.76    1178  714.11  1197.7  706.71
    1237  682.53  1256.7  668.45  1286.2  643.56    1296  639.79  1315.7   639.2
  1345.2  639.24  1364.8  642.51  1561.5  650.12  1600.8  662.83  1669.6  673.88
  1767.9  693.67  1817.1   700.7  1895.8  706.99  1944.9  718.81  2043.2  737.72
#Mann= 3 , 0 , 0
       0      .1       0  1286.2    .045       0  1364.8      .1       0
Bank Sta=1286.2,1364.8
XS Rating Curve= 0 ,0
Exp/Cntr=0.3,0.1

Type RM Length L Ch R = 1 ,20692   ,1089.1,1089.4,1087.7
XS GIS Cut Line= 3
     1456098.562      248815.655     1455570.784      250041.349
     1455699.257      250659.405
#Sta/Elev= 30
       0   818.3    68.7  807.78    98.1  800.57   206.1  762.07     314  720.08
   402.3  693.64   431.8  688.43   549.5  674.15   677.1  663.24   686.9  660.77
   726.1  643.15   745.8  639.87     785   638.1   843.9  638.83   892.9  643.16
   981.2  644.65  1040.1  641.06  1069.6  645.36  1128.4  650.48  1138.2  653.62
  1148.1   659.1  1236.4  710.95  1314.9  754.53  1324.7  759.19  1344.2  763.48
    1383  765.84  1577.3   766.8  1829.8  757.63  1907.5  756.65  1965.8  758.48
#Mann= 3 , 0 , 0
       0      .1       0   745.8    .045       0   843.9      .1       0
Bank Sta=745.8,843.9
XS Rating Curve= 0 ,0
Exp/Cntr=0.3,0.1

Type RM Length L Ch R = 1 ,19602.6 ,581.3,582.9,583.7
XS GIS Cut Line= 3
     1455293.007      248562.183     1454775.645      249687.183
     1454570.784      250579.544
#Sta/Elev= 30
       0  837.91    39.3  829.33    88.4  811.78   147.4  783.32   186.7  769.24
   265.3  728.15   294.8  715.42   363.6   695.4   461.9  672.19   520.9  648.02
   609.3   638.5   668.3   635.4   687.9  637.86   707.6  641.94   835.3   645.2
   943.4  643.28  1051.5  645.65  1061.4  647.23  1100.7  664.43  1149.8  677.57
  1335.7  704.63  1413.6  719.98  1569.4  762.28  1647.4  790.18  1676.6  795.32
  1744.8  797.36  1842.2  791.92  2056.4  769.26  2085.6  770.39  2153.8   780.2
#Mann= 3 , 0 , 0
       0      .1       0   609.3    .045       0   687.9      .1       0
Bank Sta=609.3,687.9
XS Rating Curve= 0 ,0
Exp/Cntr=0.3,0.1

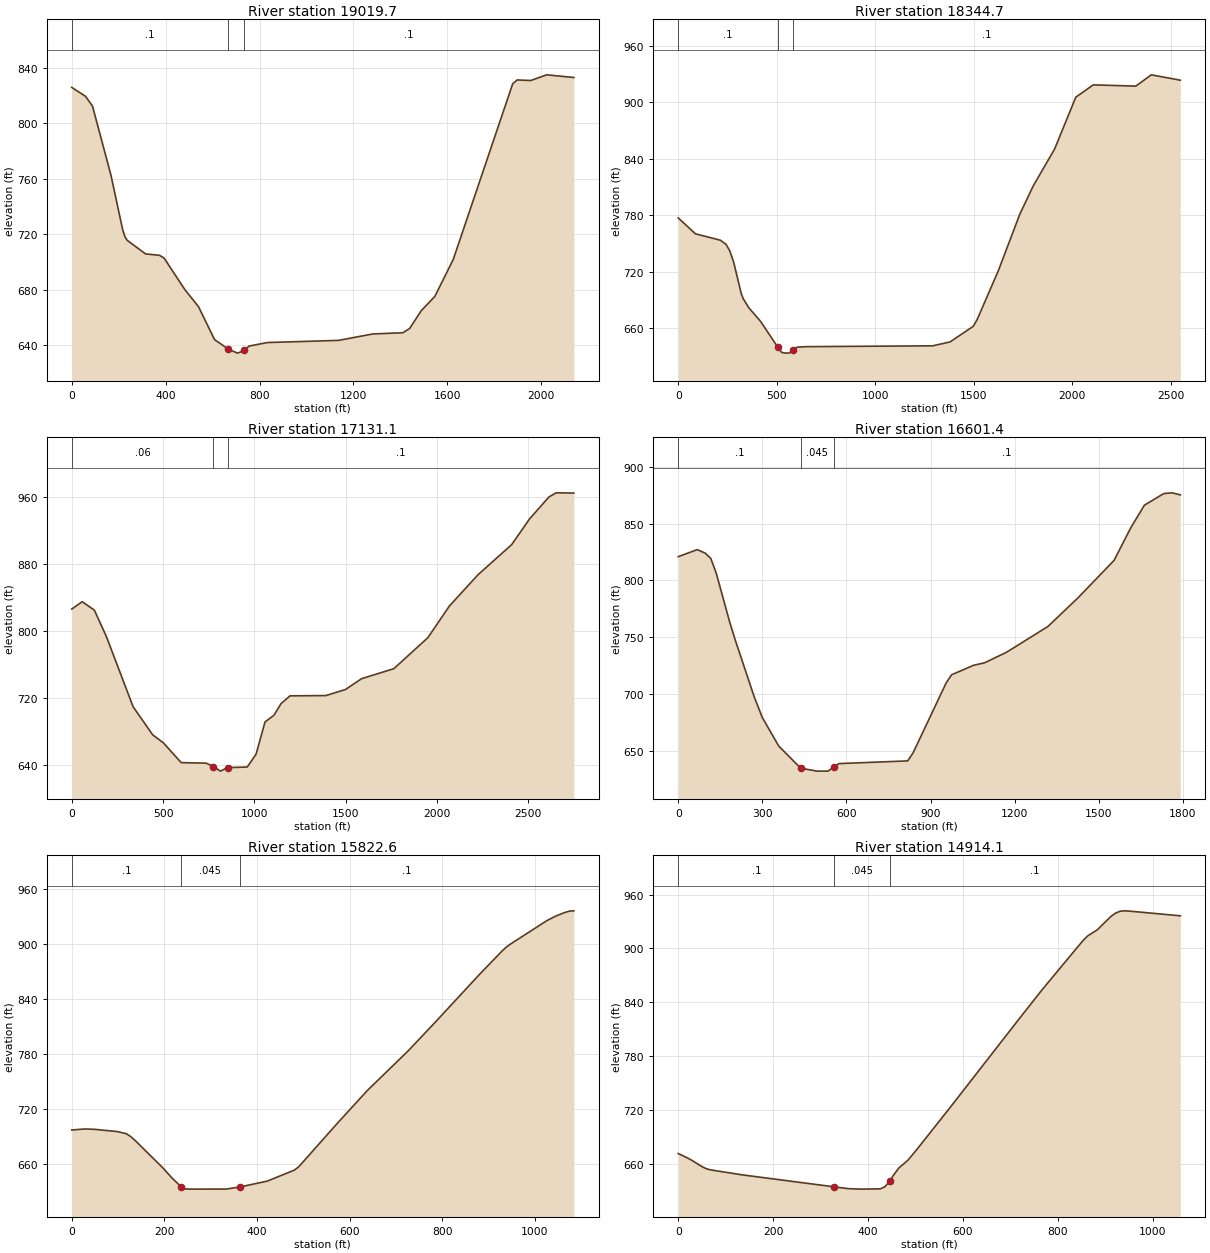
Type RM Length L Ch R = 1 ,19019.7 ,676.9,675,672.2
XS GIS Cut Line= 4
     1454783.458      248394.648     1454585.541      248800.898
     1453955.333       249983.19     1453814.708      250300.898
#Sta/Elev= 30
       0  826.01    58.9  819.54    88.4  812.46     167  762.62   216.1  723.84
     226  718.37   235.8  715.65   314.4  705.78   373.3   704.8     393  702.87
   481.2  680.15   539.9  667.71   608.4   643.9     667  637.05   706.2  634.14
   735.5  636.07   755.1  639.22   833.3  641.78  1136.4  643.34  1283.1  647.99
  1410.3  648.85  1439.6  651.91  1488.5  664.68  1547.2  675.15  1625.4  701.82
  1878.5  828.58  1897.8  831.38  1955.7  830.99  2023.3  835.09  2139.1  833.17
#Mann= 3 , 0 , 0
       0      .1       0     667    .045       0   735.5      .1       0
Bank Sta=667,735.5
XS Rating Curve= 0 ,0
Exp/Cntr=0.3,0.1

Type RM Length L Ch R = 1 ,18344.7 ,1187.6,1213.6,1237.1
XS GIS Cut Line= 3
     1454209.673       248183.71     1453990.923       248527.46
     1453180.991      250510.099
#Sta/Elev= 30
       0   777.1    87.3  760.23   213.4  753.47   242.5  749.09   261.9  741.99
   281.3  730.23   320.1  696.64   329.8  691.33   358.9  681.51   417.3  667.44
   505.7  639.74   525.3  634.26     545   633.5   564.6  633.65   584.3  637.19
   603.9  639.84   653.1  640.38  1291.6  641.26    1380  645.38  1497.9     662
  1517.6  669.12  1625.7  721.24  1733.7   780.8  1802.5  811.14  1910.6  850.13
  2018.6  905.34    2107   918.4  2323.2  917.08  2401.8  929.07  2549.1  923.37
#Mann= 3 , 0 , 0
       0      .1       0   505.7    .045       0   584.3      .1       0
Bank Sta=505.7,584.3
XS Rating Curve= 0 ,0
Exp/Cntr=0.3,0.1

Type RM Length L Ch R = 1 ,17131.1 ,544.6,529.7,514.6
XS GIS Cut Line= 5
     1454424.951      247850.377     1454206.201      247857.321
     1453338.145       247902.46     1452684.345      248821.665
     1452273.873      249164.613
#Sta/Elev= 30
       0  826.18    57.1  834.98   123.7  824.92   190.3  793.04   336.1  709.38
   443.5  675.81   502.1  666.21   599.8  642.55   736.5  641.94   775.6  637.93
   814.6   632.4   853.7  636.63   961.1  637.25    1010  652.72  1058.8  691.19
  1107.7  699.18  1146.9  713.18    1196   722.4  1392.2  722.76  1500.1  730.04
  1588.3  742.98  1764.9   754.9  1951.3  792.02    2069  829.78  2225.8  867.22
  2410.6   903.3  2507.8  933.85  2614.8  960.26  2653.7  965.18    2751  964.91
#Mann= 3 , 0 , 0
       0     .06       0   775.6    .045       0   853.7      .1       0
Bank Sta=775.6,853.7
XS Rating Curve= 0 ,0
Exp/Cntr=0.3,0.1

Type RM Length L Ch R = 1 ,16601.4 ,770.9,778.8,786
XS GIS Cut Line= 4
     1453855.507      247072.599      1453626.34      247280.933
     1453004.812      247819.127     1452431.895      248145.516
#Sta/Elev= 30
       0  820.87    67.8  827.08    96.8  823.87   116.1  819.33   135.5  806.48
   183.9  763.07   203.2  747.76     271  697.76     300  679.49   358.6  654.42
     437  634.96   495.7   632.4   534.8   632.4   554.4  636.08     574  639.02
   818.7  641.39   838.2  648.63   955.7  709.84   975.3  717.08  1053.6  725.42
  1092.7  727.58  1171.2  736.87  1318.9  759.52  1427.1  784.92    1555  817.64
  1614.1   846.1  1663.3  866.18  1732.2  876.32  1761.7  876.98  1791.2  875.16
#Mann= 3 , 0 , 0
       0      .1       0     437    .045       0   554.4      .1       0
Bank Sta=437,554.4
XS Rating Curve= 0 ,0
Exp/Cntr=0.3,0.1

Type RM Length L Ch R = 1 ,15822.6 ,872.6,908.5,944.3
XS GIS Cut Line= 3
      1453157.59      246826.071     1452567.312      247069.127
     1452150.645      247228.849
#Sta/Elev= 30
       0  696.93    29.5     698    49.1  697.64    98.2  695.18   117.8  692.84
   127.7  689.62   137.5  685.18   196.4   655.8   216.1   644.8   235.7  635.22
   245.5  632.59   255.3   632.4   333.9  632.48   363.4  634.77   422.3  641.13
   481.2   653.2     491  657.13   569.6  701.88   638.4  739.92   725.7  782.69
   783.9  813.74   880.9  866.64   929.4  892.01   939.1  896.53   948.8  900.01
  1026.4  925.26  1045.8  930.24  1065.2  934.14  1074.9  935.56  1084.6  935.92
#Mann= 3 , 0 , 0
       0      .1       0   235.7    .045       0   363.4      .1       0
Bank Sta=235.7,363.4
XS Rating Curve= 0 ,0
Exp/Cntr=0.3,0.1

Type RM Length L Ch R = 1 ,14914.1 ,737.1,739.8,742.3
XS GIS Cut Line= 3
     1453362.451      246673.294     1453161.062      246148.988
     1452865.923      245749.683
#Sta/Elev= 30
       0  672.01    19.4  667.12      29  664.34    48.4  657.94    58.1   655.3
    67.8  653.83   135.6  648.21   329.2  634.91   358.3  632.94   385.3   632.4
   426.1  632.72   435.8   635.1   445.4  641.15   455.1  648.94   464.8   655.8
   484.2  664.59   503.6  676.93   571.4  722.09   717.4     821   766.1   853.6
     844  903.09   853.7  909.09   863.5  914.22   882.9  920.64   912.2  935.76
   921.9  939.39   931.6  941.45   941.4  941.89   951.1  941.57  1058.2  936.34
#Mann= 3 , 0 , 0
       0      .1       0   329.2    .045       0   445.4      .1       0
Bank Sta=329.2,445.4
XS Rating Curve= 0 ,0
Exp/Cntr=0.3,0.1

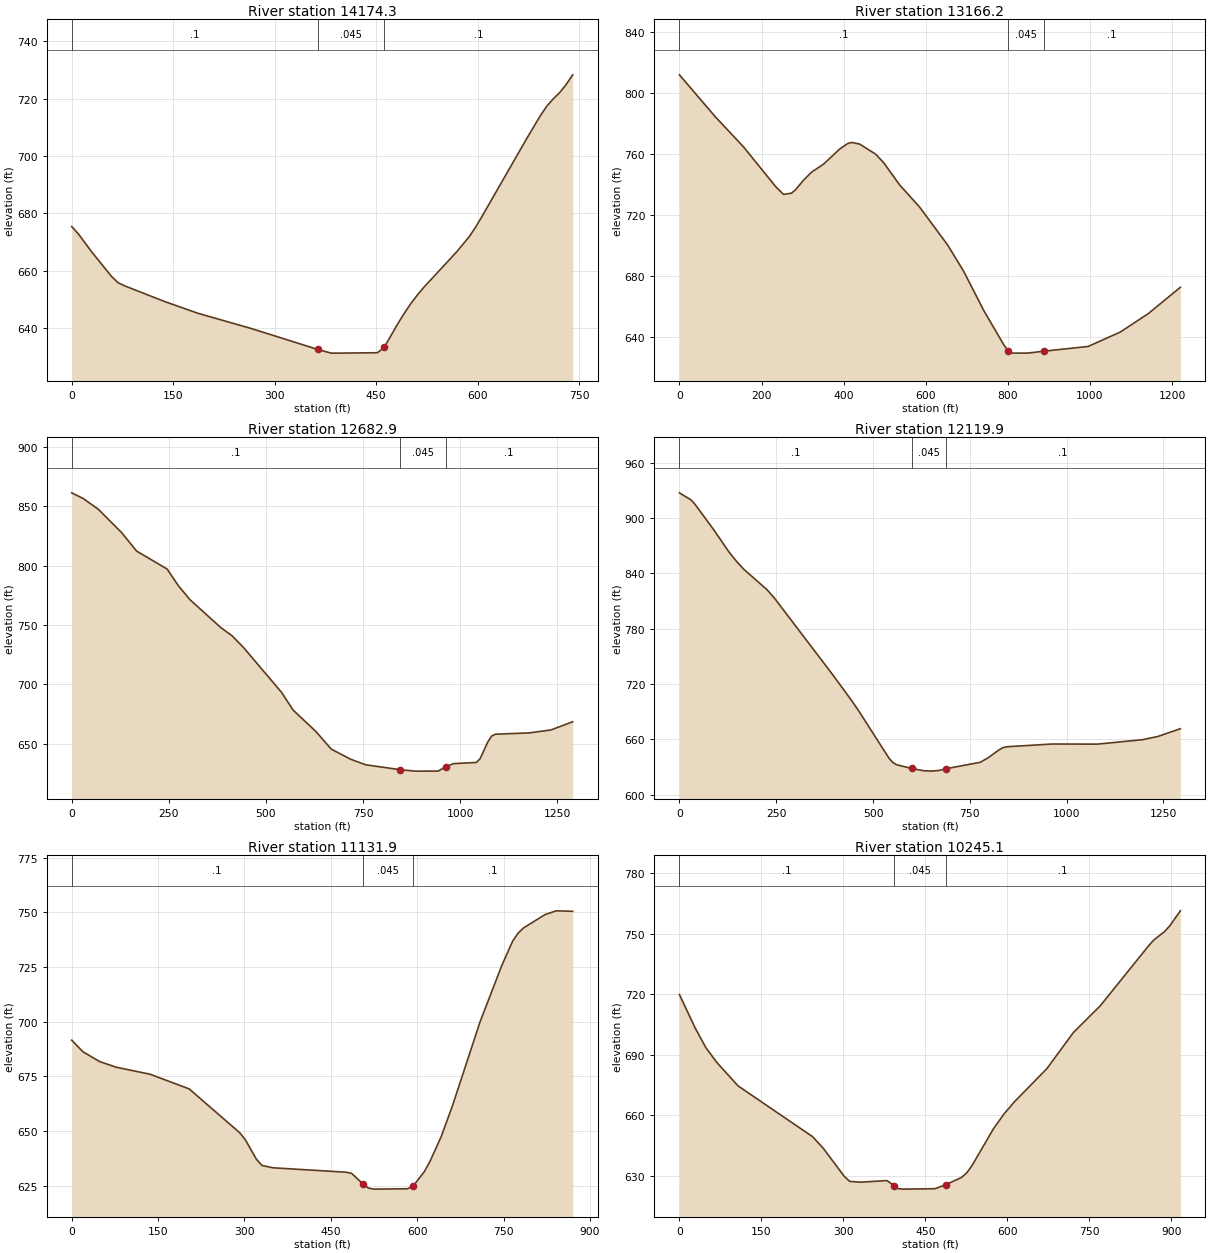
Type RM Length L Ch R = 1 ,14174.3 ,1017.2,1008,997.1
XS GIS Cut Line= 3
     1454018.701      246492.738     1453886.757      245978.849
     1453827.729       245777.46
#Sta/Elev= 30
       0  675.38     9.8  672.84    29.5  666.57      59  657.93    68.8  655.73
    78.6  654.66   137.6  649.19   186.7   645.1   265.3   639.8   363.5   632.5
   383.2  631.22     393   631.2     452  631.34   461.8  633.18   481.4  641.24
   491.3  645.02   501.1  648.45   510.9   651.5   520.7  654.25   568.7  666.49
   587.8  671.92   597.3  675.31   606.9  679.12   673.6  706.56   692.7   714.1
   702.3  717.45   711.8     720   721.3  722.18   730.9     725   740.4  728.36
#Mann= 3 , 0 , 0
       0      .1       0   363.5    .045       0   461.8      .1       0
Bank Sta=363.5,461.8
XS Rating Curve= 0 ,0
Exp/Cntr=0.3,0.1

Type RM Length L Ch R = 1 ,13166.2 ,493.8,483.3,468.8
XS GIS Cut Line= 3
     1455383.284      246419.821      1454970.09      245888.571
     1454619.395      245468.433
#Sta/Elev= 30
       0   811.9    87.8   784.3   156.1  764.69   234.1  738.76   253.6  733.52
   273.1  734.34   282.9   736.6   302.4   742.9   321.9  748.12   351.1  753.36
   390.2  763.21   409.7  766.83   419.4   767.6   438.9  766.54   477.9  759.92
   497.4  754.38   536.5  739.74   585.2   725.2   653.5  700.34   692.6  683.06
   741.4  657.43   790.3  634.91   800.1   631.2   809.8   629.5     849  629.53
     888  630.78   995.5  633.87  1073.7  643.27  1142.1  655.39  1220.3  672.64
#Mann= 3 , 0 , 0
       0      .1       0   800.1    .045       0     888      .1       0
Bank Sta=800.1,888
XS Rating Curve= 0 ,0
Exp/Cntr=0.3,0.1

Type RM Length L Ch R = 1 ,12682.9 ,583.4,563,542.5
XS GIS Cut Line= 3
     1455883.284      245662.877     1454806.895      245287.877
      1454657.59       245277.46
#Sta/Elev= 30
       0  861.22    29.5  856.45    68.8  847.32   127.7  828.01     167  812.23
   245.7  797.03   275.1  782.81   304.6  771.24   383.2  747.98   412.7  740.93
   442.2  731.08   540.4  693.19   569.9   678.4   628.9  660.24   668.2  645.51
   717.3  637.12   756.6  632.34     845  628.24   884.4     627   943.3  627.03
     963  630.73   982.6  633.31  1041.6  634.28  1051.4  637.53  1071.1  651.59
  1080.9  656.48  1090.7  658.07  1177.3  659.17  1233.4  661.64  1289.5  668.54
#Mann= 3 , 0 , 0
       0      .1       0     845    .045       0     963      .1       0
Bank Sta=845,963
XS Rating Curve= 0 ,0
Exp/Cntr=0.3,0.1

Type RM Length L Ch R = 1 ,12119.9 ,1006.9,988,968.5
XS GIS Cut Line= 3
     1455727.034      244569.127     1455004.812       245027.46
     1454633.284      245260.099
#Sta/Elev= 30
       0  927.36    29.5   919.8    39.3  915.48    88.5  887.36   127.8  863.33
   147.5  853.02   167.1   844.1   226.1  822.36   245.8  812.95   393.3   731.5
   442.4  703.44   462.1  691.48   540.8  639.83   550.6  635.11   560.4  632.53
   599.8  628.38   629.2  626.05   648.9  625.51   668.6  626.13   688.2  628.08
   776.7  635.09   796.4  639.74   825.9  648.73   835.7  650.98   845.6  651.95
   962.5  654.91  1079.4   654.8  1196.3  659.62  1235.3  663.08  1293.7   671.5
#Mann= 3 , 0 , 0
       0      .1       0   599.8    .045       0   688.2      .1       0
Bank Sta=599.8,688.2
XS Rating Curve= 0 ,0
Exp/Cntr=0.3,0.1

Type RM Length L Ch R = 1 ,11131.9 ,887.6,886.8,885.2
XS GIS Cut Line= 3
      1454407.59      244329.544     1454293.007      245010.099
     1454261.757      245187.183
#Sta/Elev= 30
       0  691.61    19.4  686.34    48.6  681.81    77.8   679.2   136.1  676.04
   204.1  669.31   291.6  649.33   301.3  646.18   320.8  637.14   330.5  634.32
   349.9  633.25   476.3  631.24     486  630.73   505.4  625.99   515.2  623.98
   524.9   623.5   583.2  623.67   592.9  624.87   612.4  631.51   622.1  636.13
   641.5   647.4     661  661.41   709.1  699.92   746.9  725.73   765.8  736.89
   775.3  740.57   784.8  742.96   822.6  749.11   841.6  750.75     870  750.53
#Mann= 3 , 0 , 0
       0      .1       0   505.4    .045       0   592.9      .1       0
Bank Sta=505.4,592.9
XS Rating Curve= 0 ,0
Exp/Cntr=0.3,0.1

Type RM Length L Ch R = 1 ,10245.1 ,986.4,986.9,987.1
XS GIS Cut Line= 3
     1453538.666      244217.565      1453465.75       244826.94
     1453439.708      245129.023
#Sta/Elev= 30
       0   719.9    29.2  703.13    48.7  693.48    68.2  686.36   107.2  674.67
   243.5  649.53     263  643.84     302  629.74   311.7  627.34   331.2  626.93
   379.9  627.73     393625.2548   399.4  623.79   409.2   623.5   467.6   623.7
   487.1  625.66   516.3  629.27     526   631.6   535.8  635.28   574.8   653.4
   594.2  660.78   613.7  666.92   672.4  683.14   721.3  701.15   770.2   714.3
   858.2  743.86     868  746.85   887.6  751.01   897.4  753.91   916.9  761.37
#Mann= 3 , 0 , 0
       0      .1       0     393    .045       0   487.1      .1       0
Bank Sta=393,487.1
XS Rating Curve= 0 ,0
Exp/Cntr=0.3,0.1

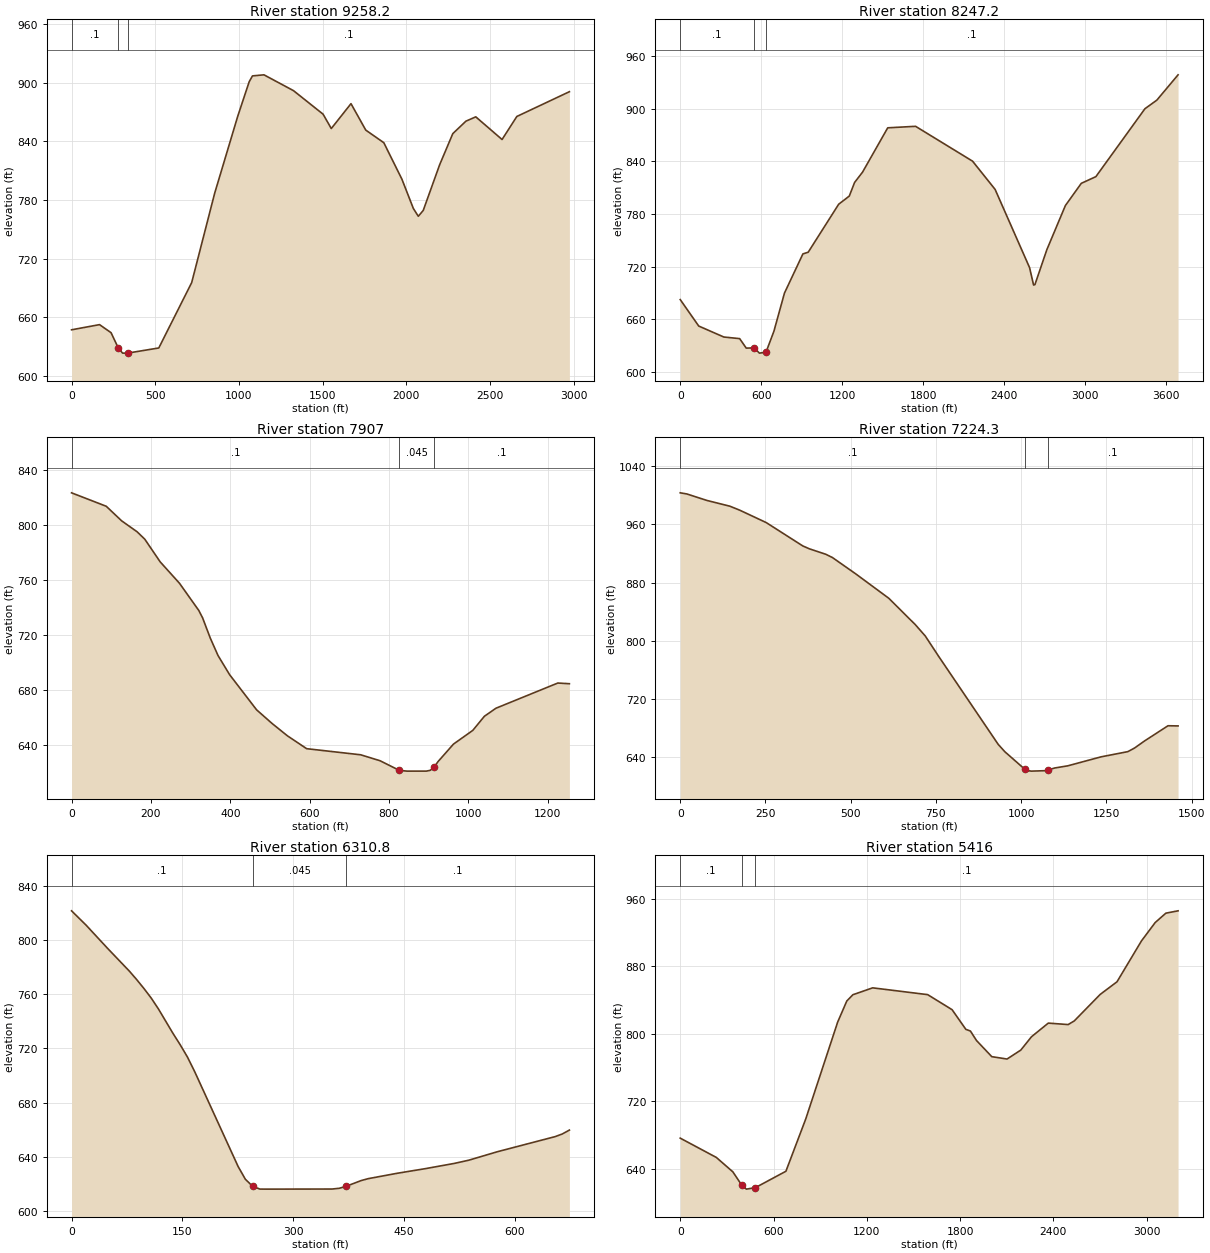
Type RM Length L Ch R = 1 ,9258.2  ,962.3,1011.1,1058.6
XS GIS Cut Line= 3
     1452580.333      244160.273     1452476.166      244910.273
        1451497.      246899.856
#Sta/Elev= 30
       0  647.36   167.2  652.64     236  644.41   278.4629.0361   304.8   623.5
   334.4   623.5   521.2  628.77   717.9  695.66   855.3  787.12   992.7  865.58
  1061.4  901.05    1081  907.02  1149.7  908.12  1326.3  891.92  1502.9  867.88
    1552  853.18  1669.7  878.65    1758   851.6  1865.9  838.69  1973.9  801.42
  2042.6  771.33    2072  763.46  2101.4  769.44  2199.5  816.18    2278  847.97
  2356.5  860.73  2415.4  865.14  2572.4  841.97  2660.7  865.53  2974.7  890.86
#Mann= 3 , 0 , 0
       0      .1       0   278.4    .045       0   334.4      .1       0
Bank Sta=278.4,334.4
XS Rating Curve= 0 ,0
Exp/Cntr=0.3,0.1

Type RM Length L Ch R = 1 ,8247.2  ,342.8,340.1,337.3
XS GIS Cut Line= 4
       1452809.5      244118.606     1452564.708      244113.398
     1452023.041      243665.481     1449924.083      245425.898
#Sta/Elev= 30
       0  682.29   137.1   652.1   322.9  639.59   440.1  637.76   488.9  626.95
   547.5  627.16   586.5  621.22   635.3  622.21   693.9   646.2     772   689.7
   908.7  734.41   947.7  736.29  1173.6  791.06  1252.1  800.36  1291.4  815.89
  1350.3  827.64  1536.8   878.2    1743  879.92  2165.3  840.14  2332.2  807.95
  2587.5   718.7  2616.9  698.94  2626.8  699.28  2715.1   739.1  2852.6  789.52
  2970.4  814.87  3078.4   822.5  3441.7  899.96  3530.1  909.79  3687.2  938.64
#Mann= 3 , 0 , 0
       0      .1       0   547.5    .045       0   635.3      .1       0
Bank Sta=547.5,635.3
XS Rating Curve= 0 ,0
Exp/Cntr=0.3,0.1

Type RM Length L Ch R = 1 ,7907    ,713.1,682.7,651.7
XS GIS Cut Line= 3
     1453293.007      243985.794     1452706.201      243753.155
     1452181.895      243416.349
#Sta/Elev= 30
       0  823.12    87.4  813.37   126.2   802.8   165.1  794.87   184.5  789.49
   223.4     773   271.9  757.52   320.5  737.82   330.2   732.4   349.6  717.69
     369  705.11   398.2   691.2   466.2   665.7     505  655.84   543.8  646.84
   592.4  637.48   728.6  633.05   777.3  628.74     826  621.74   845.4   621.2
   894.1  621.21   903.9  621.79   913.6   624.1   923.4   628.1   962.3   640.8
    1011  650.76  1040.2  660.99  1069.4  666.84  1225.2  685.11  1254.4  684.62
#Mann= 3 , 0 , 0
       0      .1       0     826    .045       0   913.6      .1       0
Bank Sta=826,913.6
XS Rating Curve= 0 ,0
Exp/Cntr=0.3,0.1

Type RM Length L Ch R = 1 ,7224.3  ,930.4,913.5,895.8
XS GIS Cut Line= 4
     1453428.423      242701.071     1452727.034      242857.321
     1452378.233      243209.991     1452208.769      243387.703
#Sta/Elev= 30
       0 1003.58    19.4 1002.02    77.7  993.16   145.7  985.14   174.8  979.62
   252.5  962.52   359.3  930.47   378.7  926.45   427.3  918.87   446.7  914.34
   514.7  891.96   611.8   858.3   689.4  822.03   718.6  806.44   757.5  778.65
   932.6  657.09     952  646.96  1010.4  622.89  1020.1  620.81  1029.8  620.19
  1068.7  620.76  1078.4  621.66  1097.9  624.47  1136.8   627.5  1234.2  639.85
  1312.8  647.02  1332.5  651.98  1361.9  661.76  1430.7   682.7  1460.2  682.46
#Mann= 3 , 0 , 0
       0      .1       0  1010.4    .045       0  1078.4      .1       0
Bank Sta=1010.4,1078.4
XS Rating Curve= 0 ,0
Exp/Cntr=0.3,0.1

Type RM Length L Ch R = 1 ,6310.8  ,897.9,894.8,891.5
XS GIS Cut Line= 3
     1451656.732      242559.509     1451657.714      242873.121
      1451653.26       243233.12
#Sta/Elev= 30
       0  821.42    19.6   810.9      49   793.6    78.4  776.85    88.2  770.67
      98   764.1   107.8  757.08   117.6  749.03   137.2  731.07     147  722.66
   156.8  713.62   166.6  702.84   225.4  632.87   235.2  623.46     245   618.3
   254.8  616.23   264.6   616.2   352.5  616.27   362.3  616.82     372  618.38
   391.5  622.44   401.2   623.9   440.1  627.84     479  631.33     518  635.17
   537.4  637.52   576.3   643.8   654.2   654.9   663.9  656.84   673.6  659.74
#Mann= 3 , 0 , 0
       0      .1       0     245    .045       0     372      .1       0
Bank Sta=245,372
XS Rating Curve= 0 ,0
Exp/Cntr=0.3,0.1

Type RM Length L Ch R = 1 ,5416    ,854.3,875.7,895.8
XS GIS Cut Line= 4
     1450724.394      242584.752     1450779.385      243016.382
        1450872.       243764.44      1449840.75      245493.606
#Sta/Elev= 30
       0  676.58   232.1  653.74   338.4  636.69   396.4  620.72   425.4   616.2
   484.1     618   679.8  637.39   807.1  699.17  1012.7  814.03  1071.4  838.98
  1110.6  846.42    1238  854.57  1591.6  846.52  1748.7   828.7  1837.1  805.42
  1866.5  803.44  1905.8  792.18    2004  773.07  2102.2  770.26  2190.6  780.86
  2259.4  796.66  2367.4   812.8  2495.1  811.08  2534.4  815.37  2701.3  846.79
  2809.4  861.74  2966.5  910.07  3054.9  931.87  3123.6     943  3202.2  945.78
#Mann= 3 , 0 , 0
       0      .1       0   396.4    .045       0   484.1      .1       0
Bank Sta=396.4,484.1
XS Rating Curve= 0 ,0
Exp/Cntr=0.3,0.1