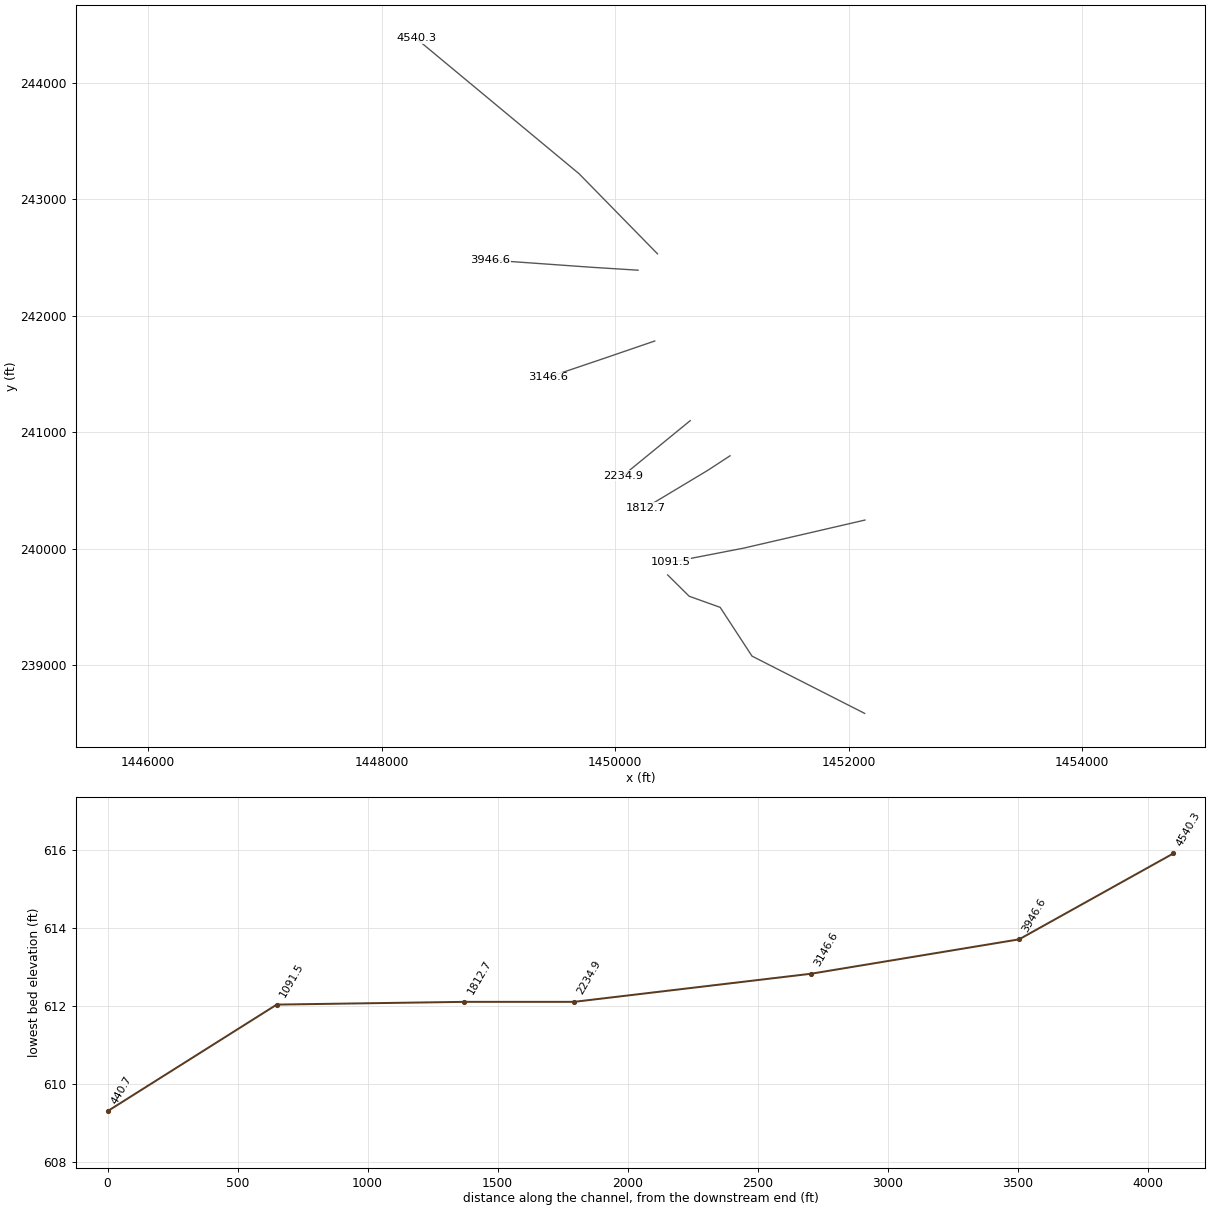
HEC-RAS study GSCR.prj: GSCR

--- GSCR.g01 (geometry) --- (continued)

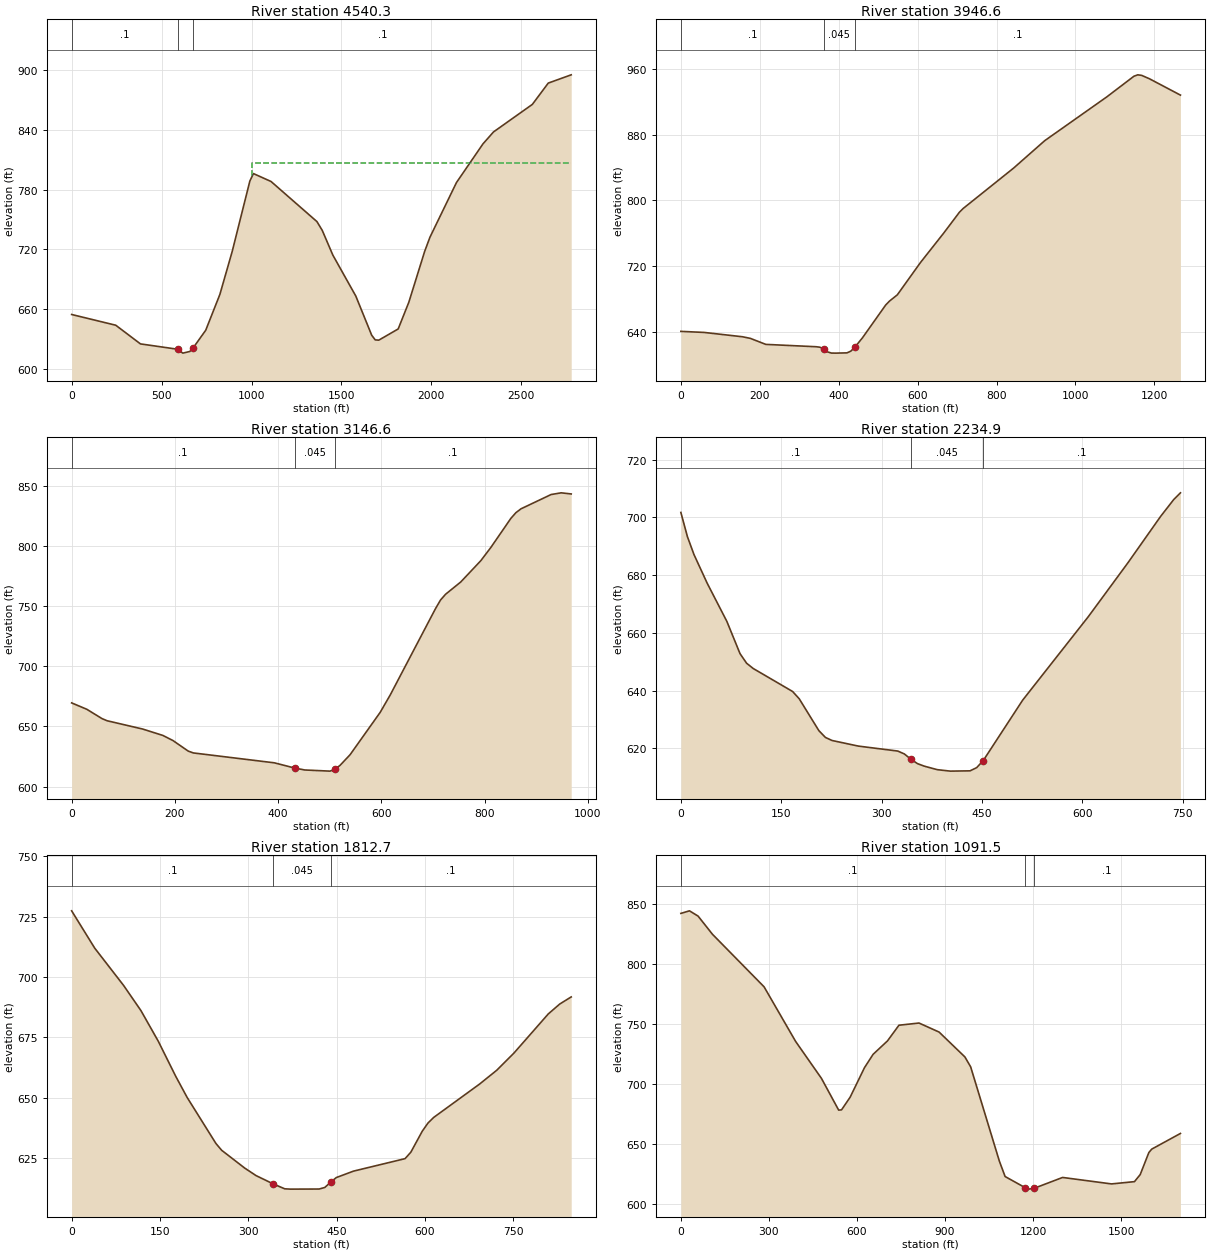
Type RM Length L Ch R = 1 ,4540.3  ,576.7,593.6,610.3
XS GIS Cut Line= 3
     1450361.583      242530.065     1449689.708      243217.565
     1448293.875      244379.023
#Sta/Elev= 30
       0   654.7   245.2  643.92   382.6  625.16   588.5  619.82     618   615.9
   657.2  617.56   676.8  621.49   745.5  638.93     824  674.84   892.6  718.02
   990.7  788.69  1010.4  796.21  1108.5  788.26  1363.7  747.96  1393.2  739.14
  1452.1  714.32  1579.7   673.2    1668  633.88  1687.6   629.2  1707.3  628.92
  1815.2  640.16  1874.1  666.84  1962.5   718.1  1991.9  732.33  2139.1  787.15
  2286.4  825.99  2345.3  838.04  2561.2   865.7  2649.5  887.07  2777.1  895.37
#Mann= 3 , 0 , 0
       0      .1       0   588.5    .045       0   676.8      .1       0
#XS Ineff= 2 , 0
                         1004.11          806.43
Permanent Ineff=
       F       F
Bank Sta=588.5,676.8
XS Rating Curve= 0 ,0
Exp/Cntr=0.3,0.1

Type RM Length L Ch R = 1 ,3946.6  ,791.1,800,809
XS GIS Cut Line= 3
     1450194.916       242389.44     1449794.621      242414.634
     1448931.859      242476.245
#Sta/Elev= 30
       0  640.22    58.7  638.94   156.5  633.63   176.1  631.68   215.2  624.36
   342.4   621.5   352.2  620.93     362  618.84   371.7   615.2   381.5  613.78
   391.3   613.7   420.8     614   430.6  616.06   440.4  620.65   460.1   632.3
     519  672.32   528.9  677.21   548.5  684.74   607.5  724.34   666.5  760.29
   705.8   785.4   715.6  790.11   843.4  839.34     922  872.67  1079.3  926.04
  1148.1  951.24  1157.9  952.97  1167.8  952.29  1187.4  948.18    1266  928.25
#Mann= 3 , 0 , 0
       0      .1       0     362    .045       0   440.4      .1       0
Bank Sta=362,440.4
XS Rating Curve= 0 ,0
Exp/Cntr=0.3,0.1

Type RM Length L Ch R = 1 ,3146.6  ,903.7,911.8,919.8
XS GIS Cut Line= 3
     1450338.109      241781.801     1449892.548      241628.743
     1449422.311      241469.301
#Sta/Elev= 30
       0  669.58    29.4  664.26    58.9  656.49    68.7  654.73   137.4  647.85
   176.7  642.51   196.3  638.25   225.7  629.51   235.6  627.96   392.6  619.73
   431.9   615.4   451.5  613.77   500.3  612.82   510.1  614.38   519.8  617.59
   539.3  626.47   597.7  661.77   617.2  676.29   704.8  748.05   714.5  755.17
   724.2  759.93   753.5  770.11   792.4  787.83   811.9  798.85   850.8  823.12
   860.6  827.86   870.3  831.02   928.7  842.92   948.2  844.33   967.6  843.39
#Mann= 3 , 0 , 0
       0      .1       0   431.9    .045       0   510.1      .1       0
Bank Sta=431.9,510.1
XS Rating Curve= 0 ,0
Exp/Cntr=0.3,0.1

Type RM Length L Ch R = 1 ,2234.9  ,425.5,422.2,419
XS GIS Cut Line= 2
     1450641.965      241098.207     1450064.708      240625.117
#Sta/Elev= 30
       0   701.7     9.8   693.3    19.6  687.11    39.3   677.2    68.7  663.97
    88.4  652.79    98.2  649.48     108  647.66     167  639.67   176.8  637.17
   206.2  626.12     216  623.77   225.9  622.71   265.2  620.77   324.1  619.05
   333.9  618.05   343.7  616.23   353.5   614.7   363.4  613.84     383  612.61
   402.6   612.1   432.1   612.2   441.9   613.3   451.7  615.73   510.7  636.69
   608.9  665.64   667.8  684.21   716.9  700.36   736.5  706.19   746.4  708.49
#Mann= 3 , 0 , 0
       0      .1       0   343.7    .045       0   451.7      .1       0
Bank Sta=343.7,451.7
XS Rating Curve= 0 ,0
Exp/Cntr=0.3,0.1

Type RM Length L Ch R = 1 ,1812.7  ,728.2,721.2,712.9
XS GIS Cut Line= 3
     1450982.677      240796.558     1450793.875       240672.86
      1450260.02      240351.679
#Sta/Elev= 30
       0  727.37    39.2  711.92    88.3  696.46   117.8  686.02   147.2  673.35
   176.6  658.94   196.3  650.04   245.2  630.98   254.9  628.19   293.9  620.84
   313.3   617.7   342.5  614.26     362  612.23   371.7   612.1   420.4  612.14
   430.1  612.79   439.9  614.95   449.6  616.89   478.8  619.55   566.4  624.72
   576.2  627.38   595.6  636.06   605.4  639.48   615.1   641.8     693  655.61
   722.2  661.34   751.4  668.45   809.8  684.68   829.3  688.78   848.7  691.71
#Mann= 3 , 0 , 0
       0      .1       0   342.5    .045       0   439.9      .1       0
Bank Sta=342.5,439.9
XS Rating Curve= 0 ,0
Exp/Cntr=0.3,0.1

Type RM Length L Ch R = 1 ,1091.5  ,676.1,650.8,622.5
XS GIS Cut Line= 3
     1452138.141      240245.256     1451099.864      240004.457
     1450474.864      239882.929
#Sta/Elev= 30
       0  842.52    29.3  844.68    58.7  840.27   107.6   825.1   283.6  781.15
   391.1   735.5   479.1  704.62   537.8  678.08   547.6   678.3   576.9   688.9
   625.8  713.58   655.2  724.74     704   735.9   743.2  749.04   811.6  750.88
     880  743.33     968  722.54   987.6  714.26  1085.4  635.47    1105  622.57
  1173.6  613.22  1183.4  612.03  1202.2612.5609  1300.9  621.79  1467.4  616.39
  1545.8  618.28  1565.4  624.19  1594.8  642.57  1604.6  645.46  1702.5  658.57
#Mann= 3 , 0 , 0
       0      .1       0  1173.6    .045       0  1202.2      .1       0
Bank Sta=1173.6,1202.2
XS Rating Curve= 0 ,0
Exp/Cntr=0.3,0.1

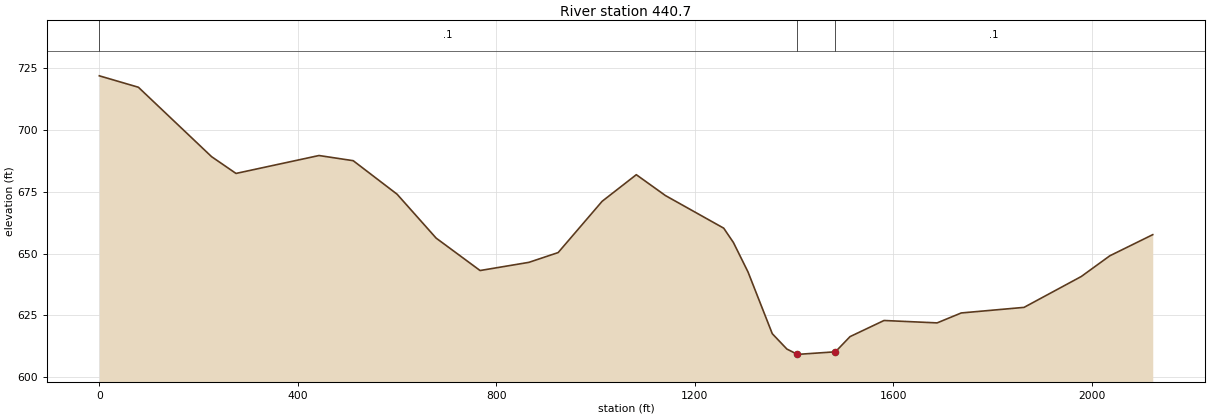
Type RM Length L Ch R = 1 ,440.7   ,460.8,440.7,420.5
XS GIS Cut Line= 5
     1452135.537      238586.402     1451171.127      239077.721
     1450898.558      239496.124     1450632.933       239591.61
     1450448.823      239774.422
#Sta/Elev= 30
       0  721.92    78.7   717.3   226.3   689.2   275.5  682.42   442.8  689.67
   511.7  687.58   600.2  674.01   678.9  656.25   767.5  643.13   865.9  646.44
   924.9   650.4  1013.5  671.14  1082.4  681.91  1141.1  673.47  1258.6  660.27
  1278.2  654.45  1307.6  642.54  1356.5  617.56  1385.9  611.36  1405.5  609.37
  1415.2   609.3  1483.8  610.24  1513.2  616.38  1581.7  622.91  1688.8  621.94
  1737.4  625.96    1864  628.22  1979.3  640.71  2036.9  649.09  2123.4  657.64
#Mann= 3 , 0 , 0
       0      .1       0  1405.5    .045       0  1483.8      .1       0
Bank Sta=1405.5,1483.8
XS Rating Curve= 0 ,0
Exp/Cntr=0.3,0.1

Chan Stop Cuts=-1
Use User Specified Reach Order=0
Composite Channel Slope=5